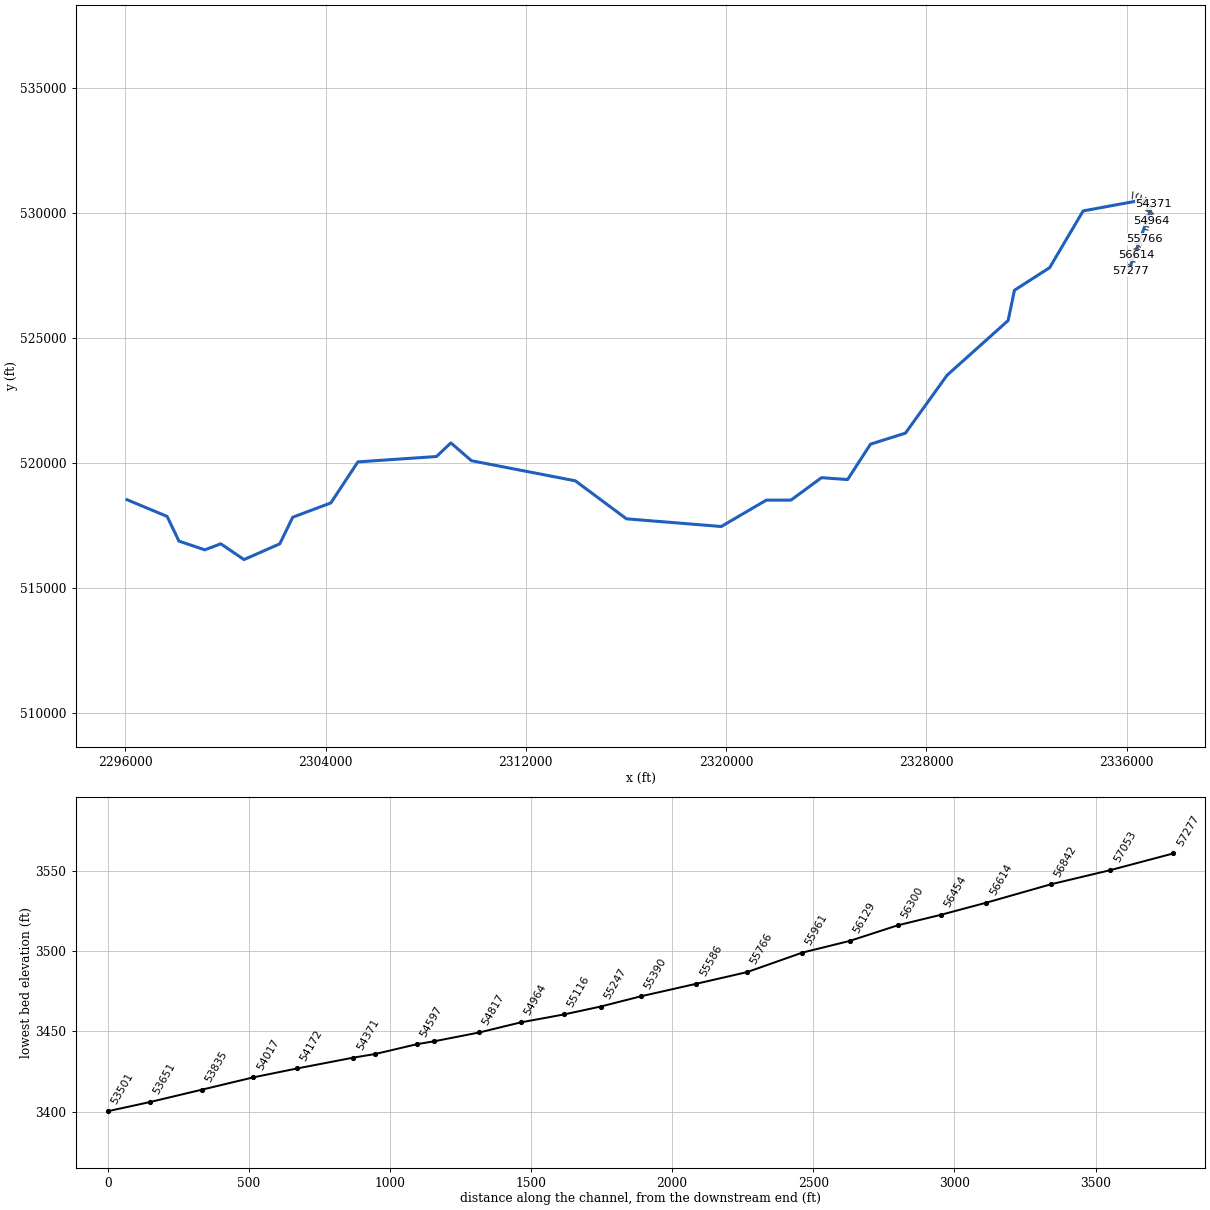
--- NRTHFRK.prj (project) ---

Proj Title=NRTHFRK
Current Plan=p01
Default Exp/Contr=0,0
English Units
Geom File=g01
Flow File=f01
Plan File=p01
Background Map Layer=FWY
BEGIN DESCRIPTION:
----------MODEL BY WOOD PLC 2021----------
Stream Name: North Fork (Elleber Run from XS 56300 to upstream extent)
Flood Zone: Detailed from confluence with Deer Creek to XS 27835; Approximate elsewhere
Pocahontas County, WV
HEC-RAS Version: RAS 6.1
Vertical Datum: NAVD88
Projection: NAD 1983 StatePlane West Virginia S FIPS 4702 (US Feet)
Terrain: 1-meter LIDAR (FEMA Region III 3DEP collected 2016-2018)
Land Use: 2019 NLCD
Hydrologic Method:
WV SIR2010-5033 regression equations
Model Notes:
!!!!!!Note KWSELs, channel burning, coincident peaks, split flow, etc. and other notable or exceptional situations
END DESCRIPTION:
DSS File=dss
DSS Export Rating Curves= 0
DSS Export Rating Curve Sorted= 0
DSS Export Volume Flow Curves= 0
DXF OffsetX= 0
DXF OffsetY= 0
DXF ScaleX= 0
DXF ScaleY= 0

--- NRTHFRK.p01 (plan) ---

Plan Title=Floodplain
Program Version=6.10
Short Identifier=Floodplain
Geom File=g01
Flow File=f01
Subcritical Flow
K Sum by GR= 0
Std Step Tol= 0.01
Critical Tol= 0.01
Num of Std Step Trials= 20
Max Error Tol= 0.3
Flow Tol Ratio= 0.001
Split Flow NTrial= 30
Split Flow Tol= 0.02
Split Flow Ratio= 0.02
Log Output Level= 0
Friction Slope Method= 1
Unsteady Friction Slope Method= 2
Unsteady Bridges Friction Slope Method= 1
Parabolic Critical Depth
Global Vel Dist= 0 , 0 , 0
Global Log Level= 0
CheckData=True
Encroach Param=-1 ,0,0, 2
Encroach River=NRTHFRK
Encroach Reach=Main
Encroach Node=28309
       1     198     375
Encroach Node=27856
       1   323.8     446
Encroach Node=27643
       1   226.5     355
Encroach Node=27431
       1   230.6     304
Encroach Node=27100
       1    85.5   143.3
Encroach Node=26885
       1   119.6  248.47
Encroach Node=26489
       1  226.91   371.7
Encroach Node=26025
       1     192     270
Encroach Node=25692
       1   134.7   180.4
Encroach Node=25374
       1  242.63   320.7
Encroach Node=25084
       1     400     500
Encroach Node=24852
       1     466   711.5
Encroach Node=24618
       1   429.9   722.7
Encroach Node=24099
       1  386.78  618.31
Encroach Node=23687
       1  454.13  716.58
Encroach Node=23366
       1     765     917
Encroach Node=23129
       1   789.5  894.25
Encroach Node=22656
       1     735     810
Encroach Node=22313
       1  611.04  688.96
Encroach Node=22159
       1   474.8  554.94
Encroach Node=21798
       1  375.58     537
Encroach Node=21466
       1   291.8     370
Encroach Node=20977
       1   232.8     390
Encroach Node=20590
       1  325.03  496.81
Encroach Node=20171
       1   393.8  518.07
Encroach Node=19598
       1   158.2     360
Encroach Node=19387
       1   154.3     360
Encroach Node=19206
       1   175.2     518
Encroach Node=19037
       1     223     562
Encroach Node=18857
       1     197  628.22
Encroach Node=18759
       1   181.5   624.6
Encroach Node=18566
       1   172.5  691.28
Encroach Node=18140
       1  741.54  1193.2
Encroach Node=17906
       1     821    1132
Encroach Node=17393
       1     876    1146
Encroach Node=17200
       1     759    1039
Encroach Node=16872
       1  736.61   902.8
Encroach Node=16743
       1   641.7  787.48
Encroach Node=16490
       1     345     580
Encroach Node=16263
       1     250     337
Encroach Node=15947
       1     475     569
Encroach Node=15509
       1     517     640
Encroach Node=15375
       1     568     699
Encroach Node=15095
       1     620     900
Encroach Node=15014
       1  729.73     964
Encroach Node=14897
       1     747    1008
Encroach Node=14562
       1     568     824
Encroach Node=14383
       1   624.8   784.1
Encroach Node=14139
       1   628.2     751
Encroach Node=13858
       1     250     450
Encroach Node=13737
       1     330     570
Encroach Node=13365
       1  540.18  721.05
Encroach Node=13122
       1   895.1  1058.6
Encroach Node=12628
       1   743.9   885.9
Encroach Node=12366
       1  756.18   865.7
Encroach Node=12157
       1  719.51   807.3
Encroach Node=11926
       1  374.08  537.92
Encroach Node=11622
       1   385.6   522.7
Encroach Node=11296
       1  355.51   578.3
Encroach Node=10716
       1     584   629.4
Encroach Node=10545
       1     962 1027.68
Encroach Node=10421
       1   882.6  999.28
Encroach Node=10209
       1   882.4    1005
Encroach Node=9658
       1     780  906.16
Encroach Node=9042
       1 1045.48 1355.58
Encroach Node=8579
       1  1055.2  1338.8
Encroach Node=7745
       1  1152.2  1621.5
Encroach Node=7014
       1  567.45  758.45
Encroach Node=6620
       1   389.5  753.93
Encroach Node=6378
       1   195.1   559.2
Encroach Node=6057
       1   160.7   600.7
Encroach Node=5592
       1   172.4   431.8
Encroach Node=5363
       1   176.7  439.44
Encroach Node=4964
       1     460   770.5
Encroach Node=4743
       1     197     490
Encroach Node=4589
       1   227.7   537.4
Encroach Node=4310
       1   163.6  441.71
Encroach Node=4040
       1  568.49     815
Encroach Node=3559
       1   337.7   530.7
Encroach Node=2946
       1   506.7   710.2
Encroach Node=2656
       1  796.04     865
Encroach Node=2488
       1   862.1   962.2
Encroach Node=2232
       1   940.4    1035
Encroach Node=2001
       1    1105    1215
Encroach Node=1702
       1    1230  1386.6
Encroach Node=1440
       1 1201.45    1415
Encroach Node=930
       1    1305    1650
Encroach Node=458
       1    1355    1598
Encroach Node=291
       1    1548  1758.8
Encroach Node=51
       1    1608    2120
Encroach Node=41
       1    2157  2653.2
Computation Interval=0.1SEC
Output Interval=1SEC
Instantaneous Interval=Max Profile
Mapping Interval=1HOUR
Computation Time Step Use Courant=        0
Computation Time Step Use Time Series=    0
Computation Time Step Count To Double=0
Computation Time Step Max Doubling=0
Computation Time Step Max Halving=0
Computation Time Step Residence Courant=0
Run HTab= 0
Run UNet= 0
Run Sediment= 0
Run PostProcess= 0
Run WQNet= 0
Run RASMapper=-1
UNET Theta= 0
UNET Theta Warmup= 0
UNET ZTol= 0
UNET ZSATol= 0
UNET MxIter= 0
UNET Max Iter WO Improvement= 0
UNET MaxInSteps= 0
UNET DtIC= 0
UNET DtMin= 0
UNET MaxCRTS= 0
UNET WFStab= 0
UNET SFStab= 0
UNET WFX= 1
UNET SFX= 1
UNET Gravity=32.174
UNET 1D Methodology=Finite Difference
UNET DSS MLevel= 1
UNET Pardiso=0
UNET DZMax Abort= 0
UNET Use Existing IB Tables= 0
UNET Froude Reduction=False
UNET Froude Limit= 0
UNET Froude Power= 0
UNET D1 Cores= 0
UNET WindReference=Eulerian
UNET WindDragFormulation=Hsu (1988)
UNET D2 Coriolis=0
UNET D2 Cores= 0
UNET D2 Theta= 1
UNET D2 Theta Warmup= 1
UNET D2 Z Tol= 0.01
UNET D2 Volume Tol= 0.01
UNET D2 Max Iterations= 20
UNET D2 Equation= 0
UNET D2 RampUpFraction=0.1
UNET D2 TimeSlices= 1
UNET D2 Turbulence Formulation=Non-Conservative (original)
UNET D2 Eddy Viscosity=0.3
UNET D2 Transverse Eddy Viscosity=0.1
UNET D2 Smagorinsky Mixing=0
UNET D2 BCVolumeCheck=0
UNET D2 Cores=0
UNET D2 SolverType=PARDISO (Direct)
UNET D2 Minimum Iterations= 2147483647
UNET D2 Maximum Iterations= 2147483647
UNET D2 Restart Number= 10
UNET D2 Relaxation Coeff=1.3
UNET D2 SOR Precondition Iterations= 10
UNET D2 ILUT Maximum Fill= 8
UNET D2 ILUT Tolerance=1E-08
UNET D1D2 MaxIter= 0
UNET D1D2 ZTol=0.01
UNET D1D2 QTol=0.1
UNET D1D2 MinQTol=1
Write IC File= 0
Write IC File at Fixed DateTime=0
Write IC File at Sim End=0
Echo Input=False
Echo Parameters=False
Echo Output=False
Write Detailed= 0
HDF Write Warmup=0
HDF Write Time Slices=0
HDF Flush=0
HDF Compression= 1
HDF Chunk Size= 1
HDF Spatial Parts= 1
HDF Use Max Rows=0
HDF Fixed Rows= 1
Calibration Method= 0
Calibration Iterations= 20
Calibration Max Change=0.05
Calibration Tolerance=0.2
Calibration Maximum=1.5
Calibration Minimum=0.5
Calibration Optimization Method= 1
WQ AD Non Conservative
WQ ULTIMATE=-1
WQ Max Comp Step=1HOUR
WQ Output Interval=15MIN
WQ Output Selected Increments= 0
WQ Output face flow=0
WQ Output face velocity=0
WQ Output face area=0
WQ Output face dispersion=0
WQ Output cell volume=0
WQ Output cell surface area=0
WQ Output cell continuity=0
WQ Output cumulative cell continuity=0
WQ Output face conc=0
WQ Output face dconc_dx=0
WQ Output face courant=0
WQ Output face peclet=0
WQ Output face adv mass=0
WQ Output face disp mass=0
WQ Output cell mass=0
WQ Output cell source sink temp=0
WQ Output nsm pathways=0
WQ Output nsm derived pathways=0
WQ Create Restart=0
WQ Fixed Restart=0
WQ System Summary=0
WQ Write To DSS=0
Sorting and Armoring Iterations= 10
XS Update Threshold= 0.02
Bed Roughness Predictor= 0
Hydraulics Update Threshold= 0.02
Energy Slope Method= 1
Volume Change Method= 1
Sediment Retention Method= 0
Sediment TS Multiplier= 1
Warm Up Method= 0
XS Weighting Method= 0
Number of US Weighted Cross Sections= 1
Number of DS Weighted Cross Sections= 1
Upstream XS Weight=0
Main XS Weight=1
Downstream XS Weight=0
Number of DS XS's Weighted with US Boundary= 1
Upstream Boundary Weight= 1
Weight of XSs Associated with US Boundary= 0
Number of US XS's Weighted with DS Boundary= 1
Downstream Boundary Weight= 0.5
Weight of XSs Associated with DS Boundary= 0.5
Percentile Method= 0
Sediment Output Level= 3
Mass or Volume Output= 0
Output Increment Type= 1
Profile and TS Output Increment= 1
Transport Output Increment 1
XS Output Flag= 0
XS Output Increment= 10
Read HDF5 Sediment Hotstart= 0
Sediment Hotstart Type= 0
Write Gradation File= 0
Read Gradation Hotstart= 0
Write HDF5 File= 1
Write Binary Output= 1
Write DSS Sediment File= 0
DSS Sediment Output Type= 1
SV Curve= 0
Specific Gage Flag= 0
Subcell Erosion Methods= 0
Subcell Deposition Methods= 0
Advection Scheme= 1
Matrix Solver= 0
Implicit Weighting Factor= 1
Maximum Outer Loop Convergence Iterations= 5
Convergence Maximum Absolute= 0.001
Convergence RMSE= 0.0001
Grain Fractions Max Abs Error= 0.001
Max Subgrid Regions= 1
Max Subgrid Length Scale= 3.402823E+38
Initial Layer Thickness= 3.402823E+38
Min Layer Thickness= 3.402823E+38
Max Layer Thickness= 3.402823E+38
Number of Layers= 5

--- NRTHFRK.f01 (steady flow) ---

Flow Title=Flow
Program Version=6.10
Number of Profiles= 7
Profile Names=01pct,FW,10pct,04pct,02pct,0_2pct,01plus
River Rch & RM=NRTHFRK,Main            ,57277
     590     590     312     415     500     824     873
River Rch & RM=NRTHFRK,Main            ,54658
     883     883     475     626     751    1220    1310
River Rch & RM=NRTHFRK,Main            ,53501
    1200    1200     653     857    1020    1660    1780
River Rch & RM=NRTHFRK,Main            ,52838
    1340    1340     731     957    1140    1840    1980
River Rch & RM=NRTHFRK,Main            ,48232
    1520    1520     834    1090    1300    2090    2250
River Rch & RM=NRTHFRK,Main            ,42571
    2150    2150    1200    1550    1840    2930    3180
River Rch & RM=NRTHFRK,Main            ,38133
    2620    2620    1470    1900    2250    3560    3880
River Rch & RM=NRTHFRK,Main            ,32742
    3060    3060    1730    2230    2630    4150    4530
River Rch & RM=NRTHFRK,Main            ,26025
    3460    3460    1960    2520    2970    4670    5110
River Rch & RM=NRTHFRK,Main            ,7014
    4370    4370    2500    3200    3760    5870    6460
Boundary for River Rch & Prof#=NRTHFRK,Main            , 1
Up Type= 0
Dn Type= 3
Dn Slope=0.00813
Boundary for River Rch & Prof#=NRTHFRK,Main            , 2
Up Type= 0
Dn Type= 3
Dn Slope=0.00813
Boundary for River Rch & Prof#=NRTHFRK,Main            , 3
Up Type= 0
Dn Type= 3
Dn Slope=0.00813
Boundary for River Rch & Prof#=NRTHFRK,Main            , 4
Up Type= 0
Dn Type= 3
Dn Slope=0.00813
Boundary for River Rch & Prof#=NRTHFRK,Main            , 5
Up Type= 0
Dn Type= 3
Dn Slope=0.00813
Boundary for River Rch & Prof#=NRTHFRK,Main            , 6
Up Type= 0
Dn Type= 3
Dn Slope=0.00813
Boundary for River Rch & Prof#=NRTHFRK,Main            , 7
Up Type= 0
Dn Type= 3
Dn Slope=0.00813
DSS Import GetInterval= 0
DSS Import GetPeak= 0
DSS Import FillOption= 0

--- NRTHFRK.g01 (geometry) ---

Geom Title=Geometry
Program Version=6.10

River Reach=NRTHFRK         ,Main
Reach XY= 30
     2336076.974       527674.48     2336968.338      530144.599
     2336726.824      530535.252     2334261.519      530080.777
     2332925.839      527814.175     2331518.666      526909.968
     2331265.457      525698.616      2328829.34      523515.584
     2327163.825      521196.874     2325767.598      520757.073
     2324853.005      519341.334     2323811.557      519416.845
     2322592.439      518520.603     2321605.345      518518.683
     2319806.312       517464.73     2316020.106      517771.643
     2313978.348      519290.873     2309829.196      520094.826
     2309004.542      520807.646     2308431.711      520262.555
     2305292.218      520048.496     2304209.738      518405.415
     2302689.314      517836.685     2302172.507      516773.475
     2300742.268      516142.362     2299814.741       516773.93
     2299177.328      516531.851     2298143.419      516881.731
     2297671.364       517867.86     2296069.201       518535.92

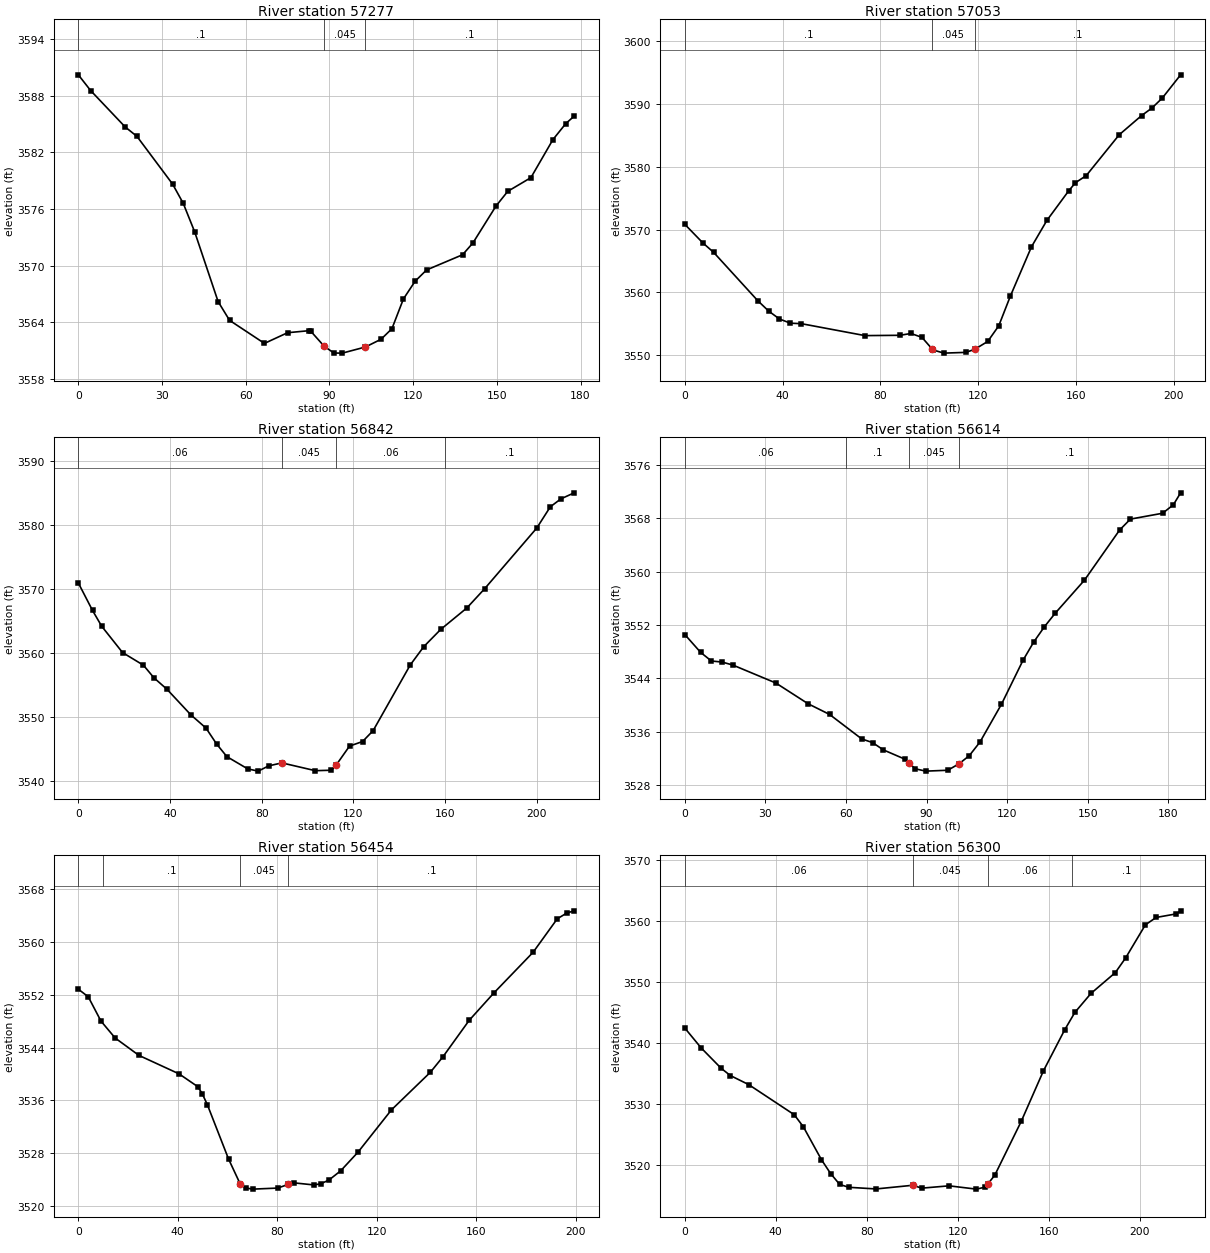
Type RM Length L Ch R = 1 ,57277   ,223.6,223.6,223.6
XS GIS Cut Line= 2
     2335991.972      527718.675     2336163.055        527670.8
#Sta/Elev= 30
       0 3590.19     4.4 3588.53    16.8 3584.67      21 3583.68    33.8 3578.62
    37.6 3576.59    41.7 3573.57    50.1 3566.19    54.2 3564.21    66.7 3561.77
      75  3562.9    82.5 3563.11    83.3 3563.06    88.1 3561.47    91.6 3560.75
    94.6 3560.74   102.9 3561.39   108.5 3562.21   112.4 3563.33   116.5 3566.47
   120.7 3568.35   124.8 3569.54   137.7 3571.15   141.4 3572.39   149.7 3576.31
   153.9 3577.86   162.2 3579.31   170.1 3583.34   174.7 3585.03   177.7 3585.82
#Mann= 3 ,-1,0
       0      .1       0    88.1    .045       0   102.9      .1       0
Bank Sta=88.1,102.9
XS Rating Curve= 0 ,0
Exp/Cntr=0.3,0.1

Type RM Length L Ch R = 1 ,57053   ,214.1,211.1,211.1
XS GIS Cut Line= 2
      2336085.61      527937.633      2336266.55      527846.107
#Sta/Elev= 30
       0 3570.85     7.4 3567.88    11.8 3566.38    29.8  3558.7    34.3 3557.03
    38.7 3555.77    43.2  3555.1    47.7 3555.02    73.7 3553.12      88 3553.17
    92.5 3553.46      97 3552.84     101 3551.06   101.5 3550.84     106 3550.33
   114.9 3550.45   118.5 3550.92   123.9 3552.19   128.4 3554.67   133.2 3559.45
   141.8 3567.27   148.1 3571.47     157 3576.17   159.8 3577.48   164.2 3578.61
   177.7 3585.12   186.8 3588.16   191.1 3589.38   195.3 3590.96   202.8 3594.66
#Mann= 3 ,-1,0
       0      .1       0     101    .045       0   118.5      .1       0
Bank Sta=101,118.5
XS Rating Curve= 0 ,0
Exp/Cntr=0.3,0.1

Type RM Length L Ch R = 1 ,56842   ,218,228,237.2
XS GIS Cut Line= 2
     2336135.206      528140.632     2336325.298      528037.373
#Sta/Elev= 30
       0 3570.96     6.2 3566.65    10.2 3564.18    19.3 3560.06    28.4 3558.08
      33  3556.1    38.7  3554.3    49.1  3550.3    55.7 3548.23    60.3 3545.75
    64.8 3543.76    73.9 3541.84    78.5 3541.49      83 3542.31    88.8 3542.78
   103.4 3541.56   110.4 3541.63   112.4  3542.4   118.3 3545.41     124 3546.13
   128.6 3547.83   144.8 3558.12   150.7 3560.99   158.1 3563.69   169.5 3567.05
   177.3 3570.08     200 3579.57   205.9 3582.89   210.5 3584.13   216.3 3585.08
#Mann= 4 ,-1,0
       0     .06       0    88.8    .045       0   112.4     .06       0
     160      .1       0
Bank Sta=88.8,112.4
XS Rating Curve= 0 ,0
Exp/Cntr=0.3,0.1

Type RM Length L Ch R = 1 ,56614   ,172.6,160.3,147
XS GIS Cut Line= 2
     2336210.304      528302.563     2336394.921      528299.434
#Sta/Elev= 30
       0 3550.56     5.9 3547.88     9.9 3546.59    13.9 3546.43    17.9 3545.98
    33.9 3543.29    45.9 3540.18    53.9 3538.58    65.9  3534.9    69.9 3534.36
    73.9 3533.27    81.9 3531.88    83.6 3531.25    85.8 3530.43    89.7 3530.08
    97.9 3530.21   102.1 3531.18   105.9 3532.39   109.9 3534.44   117.9 3540.11
   125.9 3546.68   129.9 3549.43   133.9 3551.73   137.9 3553.75   148.8 3558.71
   161.9 3566.23   165.9 3567.86   177.9 3568.74   181.9 3570.01   184.6  3571.8
#Mann= 4 ,-1,0
       0     .06       0      60      .1       0    83.6    .045       0
   102.1      .1       0
Bank Sta=83.6,102.1
XS Rating Curve= 0 ,0
Exp/Cntr=0.3,0.1

Type RM Length L Ch R = 1 ,56454   ,132.3,153.8,169.7
XS GIS Cut Line= 2
     2336265.063      528498.913     2336421.518      528375.314
#Sta/Elev= 30
       0 3552.83       4 3551.67     9.1    3548    14.8 3545.44    24.4  3542.8
    40.5 3540.01      48 3538.08    49.8 3537.03    51.9 3535.33    60.4 3527.13
    65.1 3523.34    67.3 3522.73    70.2 3522.56    80.2 3522.72    84.5 3523.29
    86.7 3523.51    94.6  3523.2    97.4 3523.35   100.8 3523.94   105.5 3525.33
   112.5 3528.17   125.9 3534.55   141.6 3540.26   146.7 3542.63   157.2 3548.12
   167.1 3552.25   182.9 3558.42   192.6 3563.48   196.4 3564.35   199.4 3564.69
#Mann= 4 ,-1,0
       0     .06       0      10      .1       0    65.1    .045       0
    84.5      .1       0
Bank Sta=65.1,84.5
XS Rating Curve= 0 ,0
Exp/Cntr=0.3,0.1

Type RM Length L Ch R = 1 ,56300   ,181,170.4,154
XS GIS Cut Line= 3
     2336304.177       528559.93     2336444.204      528568.535
     2336513.826      528534.115
#Sta/Elev= 30
       0 3542.38     7.2 3539.12      16 3535.78      20  3534.6    28.1 3533.11
    48.1 3528.18    52.1 3526.21    60.1 3520.79    64.1 3518.54    68.1 3516.75
    72.1 3516.28    84.1 3516.01   100.2 3516.61   104.2 3516.14   116.2 3516.52
   128.2 3515.98   132.2 3516.32   133.3 3516.85   136.3 3518.27   147.9 3527.07
   157.7 3535.38     167 3542.07   171.5 3544.94   178.6 3548.06   189.3 3551.47
   193.8 3553.86   202.5 3559.29   207.2  3560.5   216.1 3561.09     218 3561.59
#Mann= 4 ,-1,0
       0     .06       0   100.2    .045       0   133.3     .06       0
   170.3      .1       0
Bank Sta=100.2,133.3
XS Rating Curve= 0 ,0
Exp/Cntr=0.3,0.1

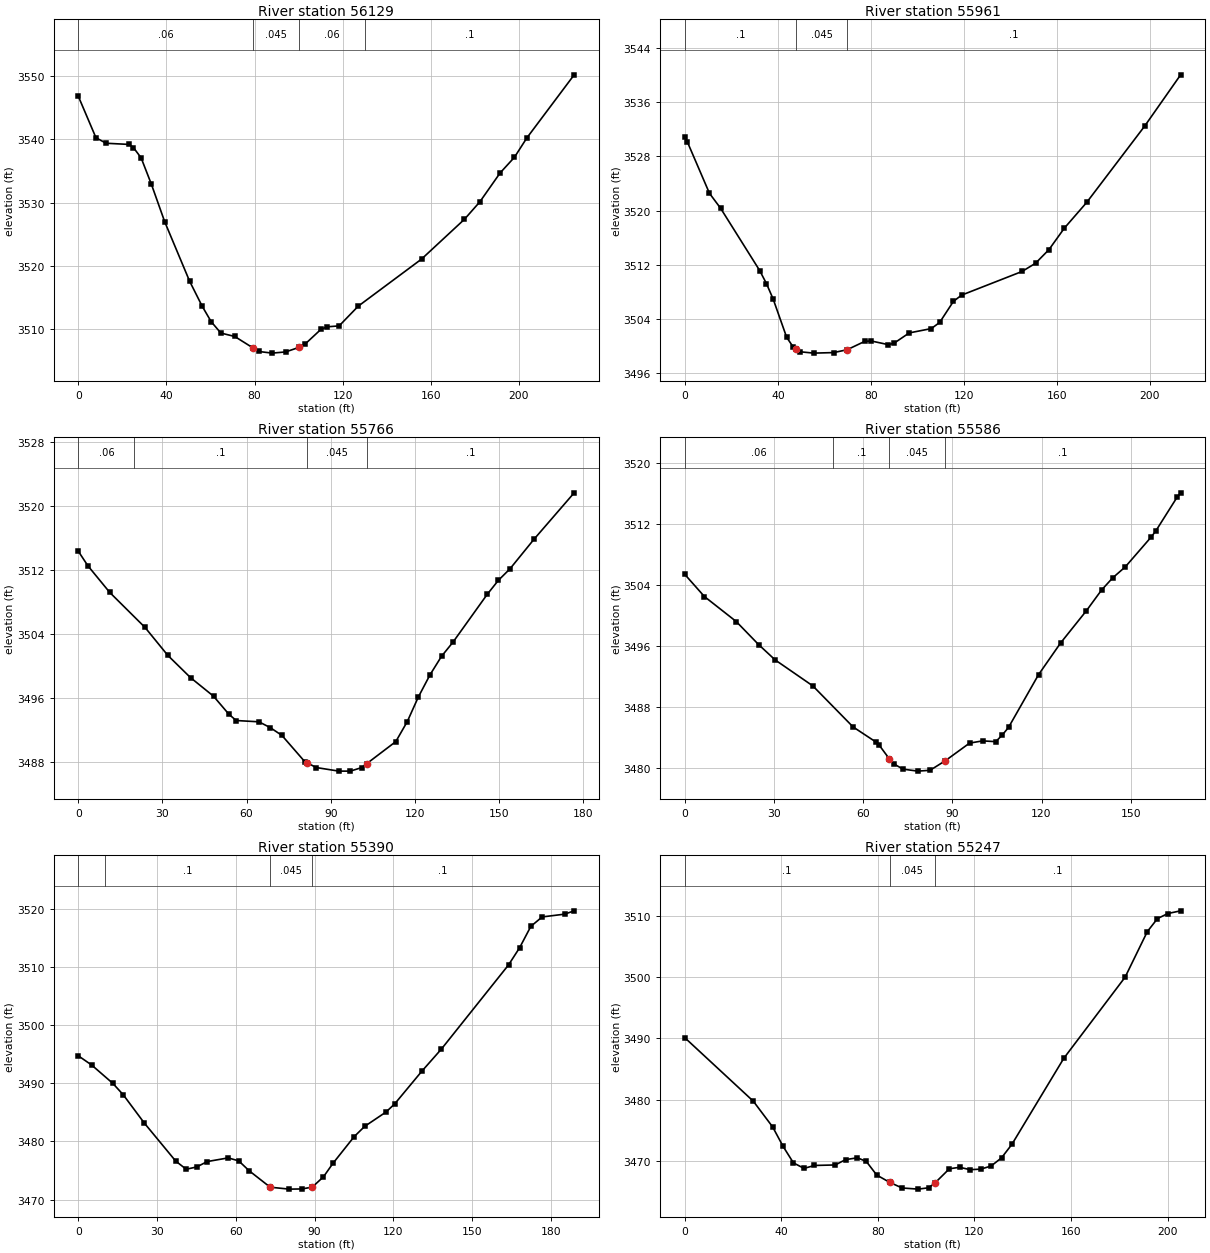
Type RM Length L Ch R = 1 ,56129   ,174.9,168,162.3
XS GIS Cut Line= 2
      2336370.67      528778.966     2336540.423      528631.117
#Sta/Elev= 30
       0  3546.8       8 3540.26    12.6 3539.39    23.2  3539.2      25 3538.71
    28.5 3537.09    33.2 3532.89    39.2 3527.01    50.5 3517.63    56.2 3513.68
    60.3 3511.23    64.7 3509.43      71 3508.89    79.3 3507.08    81.9 3506.52
      88 3506.26    94.1 3506.45   100.2 3507.17   102.8 3507.64   110.1    3510
   112.9 3510.41   118.4 3510.56   127.1 3513.68   155.8  3521.1   175.3 3527.39
   182.3 3530.15   191.5 3534.71     198 3537.18   203.6 3540.22   225.1 3550.19
#Mann= 4 ,-1,0
       0     .06       0    79.3    .045       0   100.2     .06       0
     130      .1       0
Bank Sta=79.3,100.2
XS Rating Curve= 0 ,0
Exp/Cntr=0.3,0.1

Type RM Length L Ch R = 1 ,55961   ,177.4,195,210.6
XS GIS Cut Line= 2
     2336484.491      528914.064     2336600.658      528735.237
#Sta/Elev= 30
       0 3530.78     1.1 3530.12    10.6 3522.54    15.4 3520.33    32.2 3511.15
    35.1 3509.23      38 3506.94    43.8  3501.3    46.7 3499.83   47.76 3499.56
    49.6 3499.17    55.4 3498.97      64 3499.05    69.8 3499.47    77.4 3500.71
    80.2 3500.76    87.5 3500.22      90 3500.44    96.5 3501.95     106 3502.59
   109.6  3503.5   115.5  3506.6     119 3507.52     145 3511.01   150.8 3512.22
   156.6 3514.24   163.2  3517.4   172.8 3521.19   197.7 3532.43   213.2 3540.01
#Mann= 3 ,-1,0
       0      .1       0   47.76    .045       0    69.8      .1       0
Bank Sta=47.76,69.8
XS Rating Curve= 0 ,0
Exp/Cntr=0.3,0.1

Type RM Length L Ch R = 1 ,55766   ,184.7,180.2,175.5
XS GIS Cut Line= 2
     2336552.783      528990.805     2336726.682      528959.123
#Sta/Elev= 30
       0 3514.33     3.4 3512.52    11.2 3509.19    23.8 3504.81    31.9 3501.33
      40 3498.55    48.2 3496.23    53.7 3493.97    56.3 3493.19    64.4 3493.03
    68.5 3492.29    72.6 3491.33    80.7 3488.07    81.7 3487.89    84.8 3487.32
    92.9 3486.87      97 3486.87     101 3487.31   102.9 3487.82   113.2 3490.56
   117.3 3493.06   121.2  3496.1   125.4  3498.9   129.5 3501.21   133.6 3502.98
   145.8 3508.95   149.8 3510.71   153.9 3512.13   162.5 3515.84   176.8 3521.63
#Mann= 4 ,-1,0
       0     .06       0      20      .1       0    81.7    .045       0
   102.9      .1       0
Bank Sta=81.7,102.9
XS Rating Curve= 0 ,0
Exp/Cntr=0.3,0.1

Type RM Length L Ch R = 1 ,55586   ,189.2,196.6,205.8
XS GIS Cut Line= 2
     2336620.371      529178.081     2336773.149      529111.197
#Sta/Elev= 30
       0 3505.36     6.6 3502.46    17.3 3499.19    24.8 3496.18    30.4 3494.16
    43.1 3490.75    56.6 3485.39    64.3 3483.41    65.3 3483.05    68.8 3481.21
    70.4 3480.53    73.4 3479.86    78.4  3479.6    82.5 3479.71    87.6 3480.95
    95.8 3483.27   100.2 3483.56   104.6 3483.46   106.8 3484.33   108.9 3485.32
     119 3492.23   126.4 3496.37   135.1  3500.6   140.2 3503.31   143.9 3504.89
   148.2 3506.35     157  3510.3   158.5 3511.08   165.7 3515.52   166.8 3516.04
#Mann= 4 ,-1,0
       0     .06       0      50      .1       0    68.8    .045       0
    87.6      .1       0
Bank Sta=68.8,87.6
XS Rating Curve= 0 ,0
Exp/Cntr=0.3,0.1

Type RM Length L Ch R = 1 ,55390   ,148.9,142.2,133.5
XS GIS Cut Line= 3
     2336659.094      529333.675     2336779.485      529337.899
     2336843.553      529313.962
#Sta/Elev= 30
       0 3494.71     5.1 3493.12    13.1 3489.99    17.1 3488.02    25.1 3483.17
    37.1 3476.61    41.1 3475.21    45.1  3475.6    49.1 3476.53    57.1 3477.16
    61.1 3476.65    65.1 3474.94    73.1 3472.12    80.4 3471.79    85.1 3471.82
    89.1 3472.13    93.4 3473.91      97 3476.22   105.1 3480.82   109.1 3482.58
   117.2 3485.04   120.5 3486.43   130.9 3492.08   138.3 3495.86   163.9 3510.34
   168.1 3513.28   172.4 3516.97   176.7 3518.59   185.3 3519.07   188.9 3519.64
#Mann= 4 ,-1,0
       0     .06       0      10      .1       0    73.1    .045       0
    89.1      .1       0
Bank Sta=73.1,89.1
XS Rating Curve= 0 ,0
Exp/Cntr=0.3,0.1

Type RM Length L Ch R = 1 ,55247   ,129.2,131,132.8
XS GIS Cut Line= 2
     2336682.327      529508.278     2336873.123      529432.241
#Sta/Elev= 30
       0 3490.12    28.4 3479.76    36.4 3475.57    40.7 3472.41      45 3469.71
    49.4 3468.81    53.7 3469.29    62.3 3469.37    66.6 3470.24    71.5 3470.54
    75.2 3469.94    79.5 3467.73    84.8 3466.55      90 3465.62    96.7 3465.43
     101 3465.65   103.6 3466.42   109.6 3468.75   113.9 3468.99   118.2  3468.6
   122.6 3468.69   126.9  3469.2   131.2 3470.53   135.5 3472.73     157 3486.76
   182.4 3499.99   191.6 3507.42   195.8 3509.54   200.1 3510.37   205.4 3510.81
#Mann= 3 ,-1,0
       0      .1       0    84.8    .045       0   103.6      .1       0
Bank Sta=84.8,103.6
XS Rating Curve= 0 ,0
Exp/Cntr=0.3,0.1

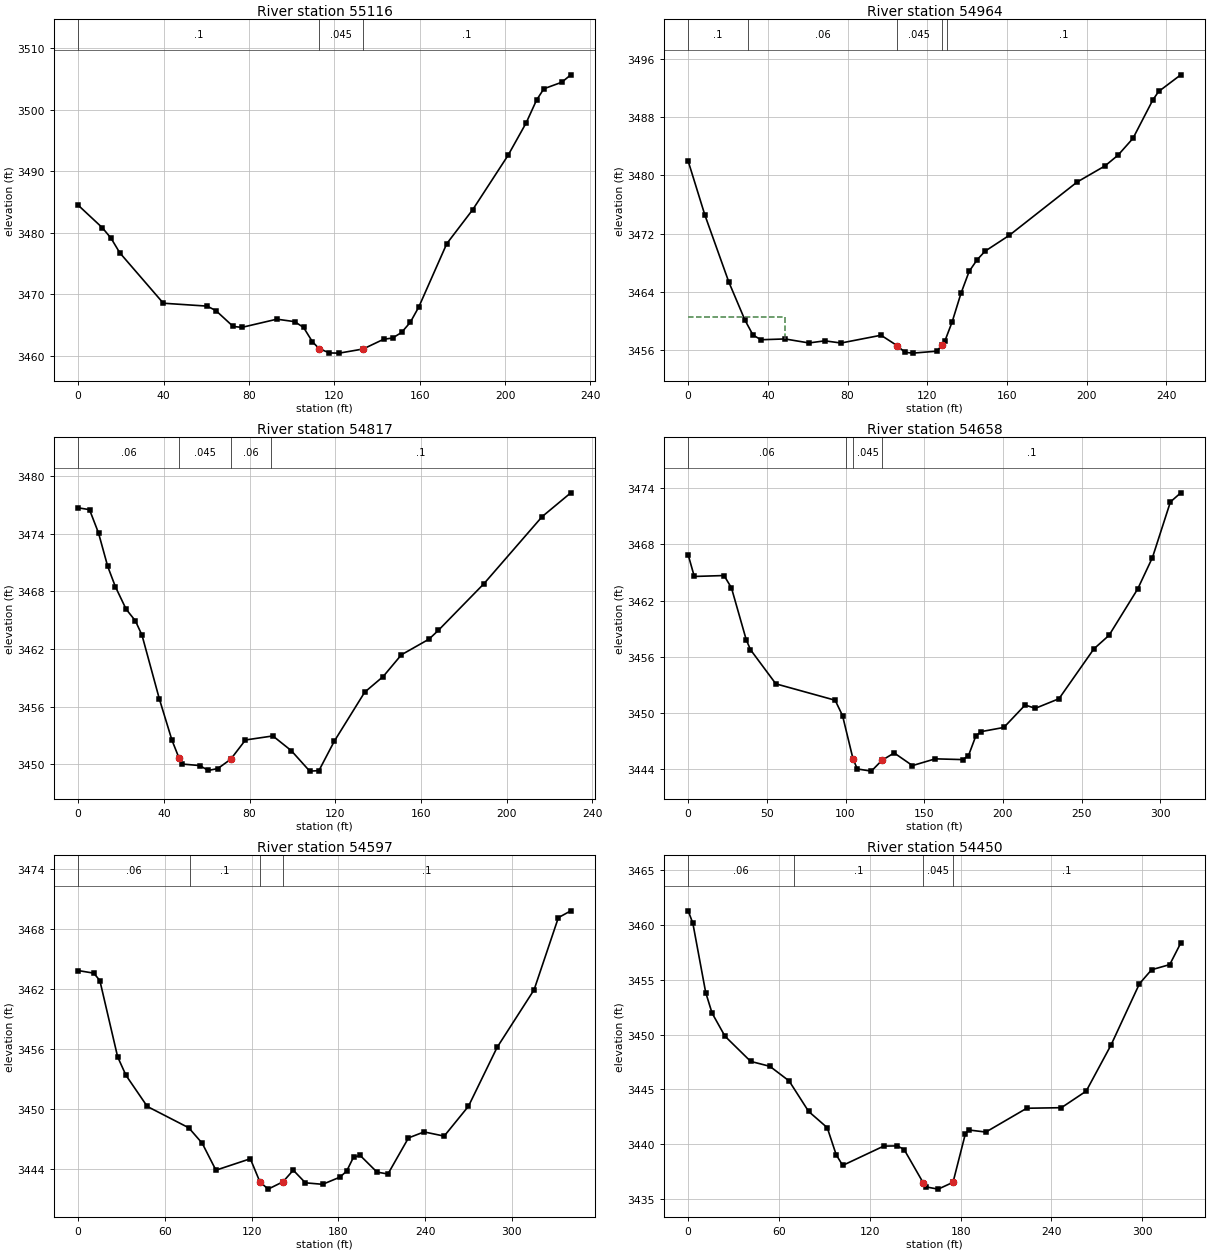
Type RM Length L Ch R = 1 ,55116   ,148.3,152.5,156.3
XS GIS Cut Line= 3
     2336697.112      529583.611     2336790.046      529603.324
     2336920.294      529564.602
#Sta/Elev= 30
       0 3484.49    11.3 3480.84    15.4 3479.13    19.5 3476.76    39.9 3468.58
    60.4 3468.11    64.5 3467.39    72.6 3464.81    76.7 3464.66    93.1 3465.99
   101.4 3465.59   105.6 3464.65   109.7 3462.35   112.8 3461.23   117.7 3460.51
   122.3 3460.48   133.5 3461.15   143.1 3462.73   147.3 3462.93   151.5 3463.83
   155.6 3465.48   159.6 3467.98   172.7 3478.25   184.9 3483.79   201.4 3492.58
   209.9 3497.86   214.8 3501.58   218.2 3503.39   226.6 3504.45   230.8 3505.65
#Mann= 3 ,-1,0
       0      .1       0   112.8    .045       0   133.5      .1       0
Bank Sta=112.8,133.5
XS Rating Curve= 0 ,0
Exp/Cntr=0.3,0.1

Type RM Length L Ch R = 1 ,54964   ,153.3,146.8,141.1
XS GIS Cut Line= 3
     2336735.835       529753.99     2336885.796      529739.909
     2336968.873      529690.625
#Sta/Elev= 30
       0 3481.96     8.4 3474.53    20.4 3465.33    28.5 3460.09    32.5 3458.05
    36.5 3457.39    48.6  3457.5    60.6 3456.95    68.6 3457.24    76.7 3456.94
    96.8 3458.01   104.8 3456.59   108.8 3455.66   112.8 3455.55   124.9 3455.82
   127.2 3456.65   128.9 3457.27   132.5 3459.87   136.9 3463.77     141 3466.79
     145 3468.39     149 3469.57   161.1 3471.74   195.2 3479.08   209.2  3481.3
   215.7 3482.77   223.2 3485.08   233.2 3490.38   236.1 3491.53   247.2 3493.82
#Mann= 5 ,-1,0
       0      .1       0      30     .06       0   104.8    .045       0
   127.2     .06       0     130      .1       0
#XS Ineff= 2 , 0
            48.4 3460.52
Permanent Ineff=
       F       F
Bank Sta=104.8,127.2
XS Rating Curve= 0 ,0
Exp/Cntr=0.3,0.1

Type RM Length L Ch R = 1 ,54817   ,163.3,159.2,155.4
XS GIS Cut Line= 2
     2336775.261      529906.767     2336989.995      529824.394
#Sta/Elev= 30
       0 3476.68     5.3 3476.49     9.5 3474.06    13.8 3470.58    17.4 3468.46
    22.4 3466.13    26.7 3464.93    29.8 3463.43    37.9  3456.8    43.8  3452.5
      47  3450.7    48.4 3450.03    56.7 3449.87    60.8 3449.36    65.2 3449.56
    71.2 3450.52    78.1 3452.53    90.9 3452.95    99.5 3451.42   108.1 3449.29
   112.4 3449.34   119.6 3452.41   133.8 3457.51   142.4 3459.13   150.9 3461.39
   163.8 3463.02   168.1 3463.92   189.5  3468.8   216.6 3475.76     230 3478.24
#Mann= 4 ,-1,0
       0     .06       0      47    .045       0    71.2     .06       0
      90      .1       0
Bank Sta=47,71.2
XS Rating Curve= 0 ,0
Exp/Cntr=0.3,0.1

Type RM Length L Ch R = 1 ,54658   ,61.2,60.9,60.5
XS GIS Cut Line= 3
     2336780.826      530098.068     2336954.088      529990.548
     2337019.564      529903.247
#Sta/Elev= 30
       0 3466.88     3.9 3464.57    22.8 3464.67    27.5 3463.36    36.9 3457.82
    39.6 3456.76    55.7 3453.12    93.4 3451.37    98.1 3449.72   104.8 3445.08
   107.5 3444.04   116.4 3443.81   123.1 3444.96   130.9 3445.75   142.5  3444.4
     157 3445.12   174.5 3445.04   178.1 3445.46   182.8 3447.57   186.1 3448.02
   200.6 3448.47   214.1 3450.86   220.6 3450.51   235.6 3451.53   257.8 3456.85
   267.4 3458.29   285.6 3463.23     295 3466.59   306.4 3472.52     313 3473.49
#Mann= 4 ,-1,0
       0     .06       0     100      .1       0   104.8    .045       0
   123.1      .1       0
Bank Sta=104.8,123.1
XS Rating Curve= 0 ,0
Exp/Cntr=0.3,0.1

Type RM Length L Ch R = 1 ,54597   ,113.1,147.4,166.5
XS GIS Cut Line= 4
2336785.59476063530103.588483838 2336861.1642588 530120.73450443
2337007.22295274530026.7489100722337065.64643031529958.799865502
#Sta/Elev= 30
       0 3463.83    10.8 3463.57      15 3462.83    27.3 3455.22    33.1 3453.37
    47.8 3450.27    76.5 3448.14    85.8  3446.6    95.3 3443.91   119.1 3445.05
   125.7 3442.75   131.4 3442.02  141.69 3442.75   148.8 3443.91   157.2 3442.65
   169.1  3442.5     181 3443.21   185.7 3443.81   190.5 3445.21   195.1 3445.38
   206.7 3443.72   214.3 3443.53   228.5 3447.13   239.3 3447.73   253.2 3447.31
     270 3450.29   289.8 3456.16   315.4 3461.91   332.2 3469.11   340.8 3469.79
#Mann= 4 ,-1,0
       0     .06       0   77.49      .1       0   125.7    .045       0
  141.69      .1       0
Bank Sta=125.7,141.69
XS Rating Curve= 0 ,0
Exp/Cntr(USF)=0,0
Exp/Cntr=0.3,0.1

Type RM Length L Ch R = 1 ,54450   ,67.9,78.5,85.5
XS GIS Cut Line= 4
2336793.21521423530137.880525023 2336864.3394478530162.646999212
2337015.47844413530240.756648577 2337095.4932069530238.851535178
#Sta/Elev= 30
       0 3461.28     3.1 3460.15    11.6 3453.83    15.8 3451.96    24.3 3449.86
    41.3 3447.56      54 3447.11    66.7 3445.78    79.6    3443    91.9 3441.52
    97.8 3439.06   102.1 3438.08   129.2 3439.84   138.2 3439.86   142.7 3439.53
  155.21 3436.52   157.2 3436.12   165.2 3435.92     175 3436.54   183.2 3440.98
   185.4 3441.31   196.7 3441.12   223.7 3443.29   246.6 3443.34     263 3444.85
   279.4 3449.05   298.2 3454.64   306.2 3455.91   318.2 3456.38   325.5 3458.35
#Mann= 4 ,-1,0
       0     .06       0      70      .1       0  155.21    .045       0
     175      .1       0
Bank Sta=155.21,175
XS Rating Curve= 0 ,0
Exp/Cntr(USF)=0,0
Exp/Cntr=0.3,0.1

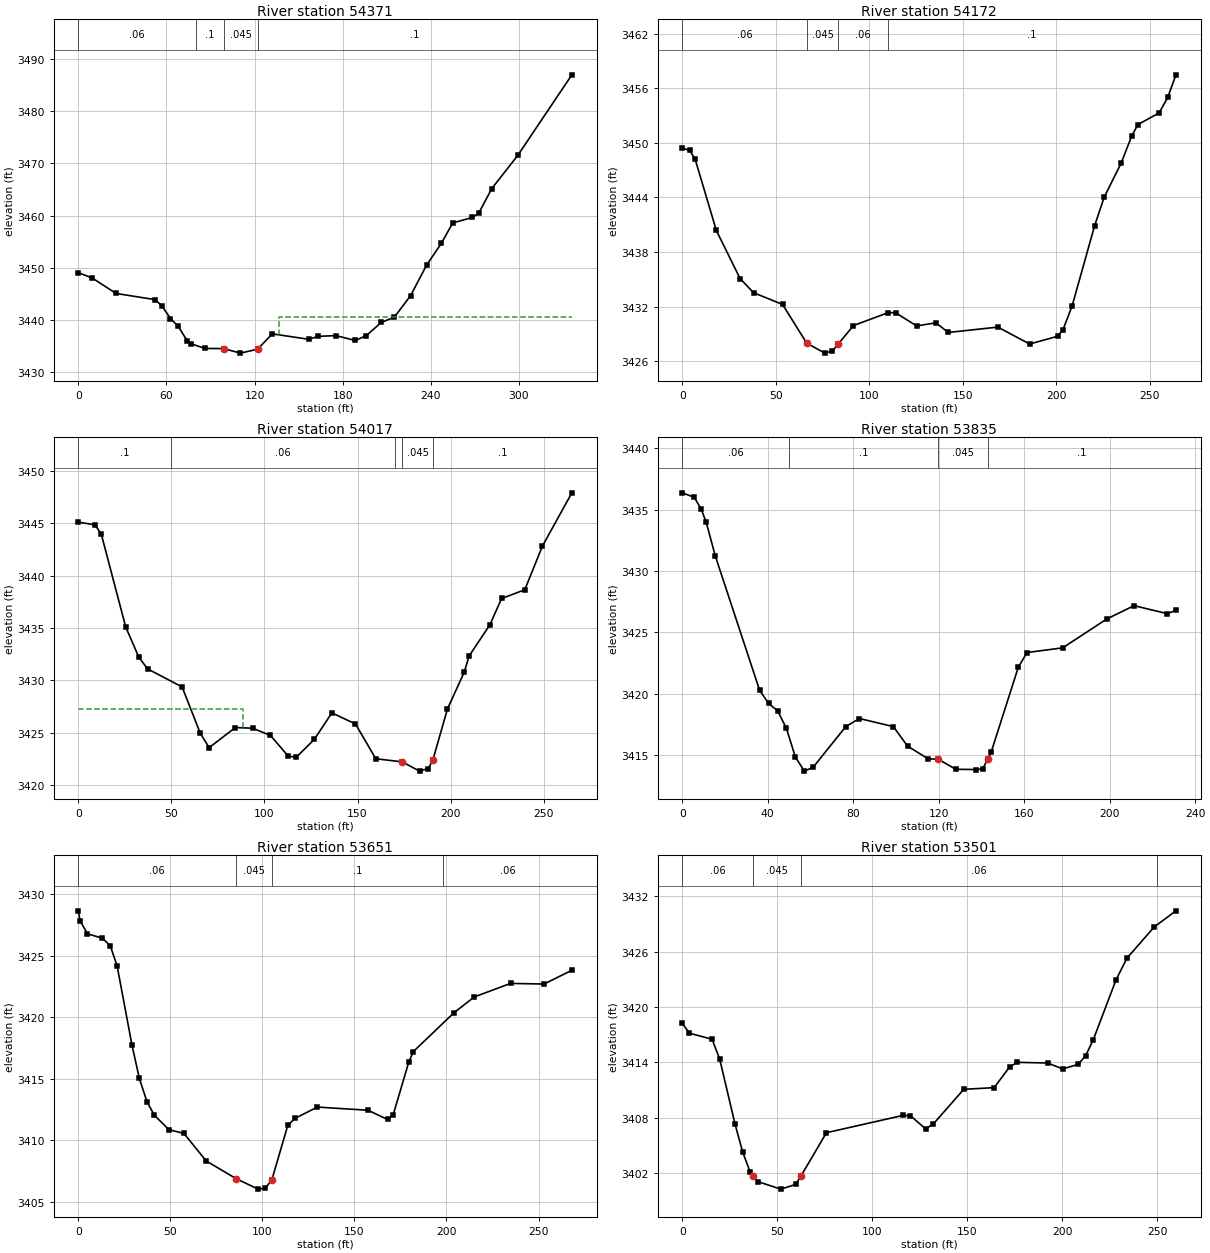
Type RM Length L Ch R = 1 ,54371   ,201,199.5,198.2
XS GIS Cut Line= 3
     2336811.167       530170.082336902.33296919530273.565163028
      2337081.52       530358.06
#Sta/Elev= 30
       0 3449.06     9.5 3448.03    25.7 3445.07    52.1 3443.89    56.8 3442.75
    62.8 3440.26    68.1 3438.75    74.1 3436.02    76.6 3435.45    86.2 3434.53
      993434.495   110.4 3433.63   122.13434.385   132.1 3437.32     157 3436.28
   163.1 3436.84   175.3 3436.99   188.6 3436.06   196.1 3436.99   206.3 3439.52
   215.1  3440.5   226.2 3444.63   237.2 3450.53   247.2 3454.68   254.9 3458.58
   268.2 3459.62   272.6 3460.45   281.5 3465.16   299.2 3471.53     336 3486.96
#Mann= 4 ,-1,0
       0     .06       0      80      .1       0      99    .045       0
   122.1      .1       0
#XS Ineff= 2 , 0
                          136.56          3440.6
Permanent Ineff=
       F       F
Bank Sta=99,122.1
XS Rating Curve= 0 ,0
Exp/Cntr=0.3,0.1

Type RM Length L Ch R = 1 ,54172   ,156.8,154.9,158
XS GIS Cut Line= 2
     2336687.255      530338.346     2336874.531      530524.214
#Sta/Elev= 30
       0 3449.41       4 3449.15     6.9 3448.17    18.2 3440.36    30.9 3435.07
    38.1 3433.52    53.6 3432.23    66.5 3427.98    76.2 3426.88    80.2 3427.11
    83.5 3427.91    91.5 3429.91   110.1 3431.33     114 3431.32   125.3 3429.87
   135.6 3430.21   142.2 3429.15   168.7 3429.74   185.7 3427.88   200.6 3428.73
   203.5 3429.44   208.4 3432.06   220.4 3440.86   225.5 3443.99   234.6 3447.75
   240.2 3450.71   243.6    3452   254.9 3453.27   259.5 3454.97   263.9 3457.46
#Mann= 4 ,-1,0
       0     .06       0    66.5    .045       0    83.5     .06       0
     110      .1       0
Bank Sta=66.5,83.5
XS Rating Curve= 0 ,0
Exp/Cntr=0.3,0.1

Type RM Length L Ch R = 1 ,54017   ,176.8,182,186.8
XS GIS Cut Line= 2
     2336626.708      530385.517     2336766.812      530610.812
#Sta/Elev= 30
       0  3445.1       9 3444.85    12.4 3443.95    25.5  3435.1    32.6  3432.2
    37.3  3431.1    55.8 3429.38    65.5 3424.98    70.3 3423.59    84.4 3425.51
    93.7 3425.44   103.2 3424.76   112.7  3422.8     117 3422.66   126.8 3424.38
   136.2 3426.91   148.9 3425.85   159.8 3422.53     1743422.235   183.3 3421.35
     188  3421.6   190.43422.377   198.3 3427.29   207.3 3430.79   209.9 3432.33
     221 3435.29   227.4 3437.82   239.8 3438.65   249.3 3442.82   265.1  3447.9
#Mann= 5 ,-1,0
       0      .1       0      50     .06       0     170      .1       0
     174    .045       0   190.4      .1       0
#XS Ineff= 2 , 0
           88.32 3427.31
Permanent Ineff=
       F       F
Bank Sta=174,190.4
XS Rating Curve= 0 ,0
Exp/Cntr=0.3,0.1

Type RM Length L Ch R = 1 ,53835   ,179.8,183.4,186.9
XS GIS Cut Line= 2
     2336523.917      530478.451     2336589.393      530700.225
#Sta/Elev= 30
       0 3436.38     5.6 3436.01     8.8 3435.07    11.2 3433.98    15.4 3431.26
    36.2 3420.27    40.4 3419.21    44.6 3418.61    48.7 3417.19    52.9 3414.85
    57.1 3413.69    61.2    3414    76.5 3417.32    82.9 3417.98    98.8 3417.32
   105.4 3415.73   115.1 3414.69   119.73414.666     128 3413.84   137.6 3413.82
   140.5 3413.87     1433414.664   144.6 3415.27   157.2 3422.14   161.3 3423.36
     178 3423.74   198.7  3426.1   211.4 3427.18   226.9 3426.53     231  3426.8
#Mann= 4 ,-1,0
       0     .06       0      50      .1       0   119.7    .045       0
     143      .1       0
Bank Sta=119.7,143
XS Rating Curve= 0 ,0
Exp/Cntr=0.3,0.1

Type RM Length L Ch R = 1 ,53651   ,150.5,150.6,151.1
XS GIS Cut Line= 3
     2336370.435      530536.183     2336390.149      530703.042
     2336459.145      530775.558
#Sta/Elev= 30
       0 3428.64       1 3427.84       5 3426.77    13.1 3426.42    17.4  3425.8
    21.1 3424.18    29.2 3417.72    33.2 3415.02    37.3 3413.14    41.3 3412.03
    49.3 3410.85    57.4 3410.55    69.5 3408.31    85.9 3406.86    97.7 3406.02
   101.7  3406.1   105.2 3406.79   113.8  3411.2   117.7 3411.77   129.9 3412.69
   157.4 3412.43     168 3411.68     171 3412.03   179.5 3416.33     182  3417.2
   204.1 3420.36   215.1 3421.64   234.8 3422.74     253 3422.69   268.1 3423.81
#Mann= 4 ,-1,0
       0     .06       0    85.9    .045       0   105.2      .1       0
   198.1     .06       0
Bank Sta=85.9,105.2
XS Rating Curve= 0 ,0
Exp/Cntr=0.3,0.1

Type RM Length L Ch R = 1 ,53501   ,120.4,123.1,125.6
XS GIS Cut Line= 2
     2336227.514      530573.497     2336248.636      530832.586
#Sta/Elev= 30
       0 3418.24     3.7 3417.16    15.7  3416.5    19.7 3414.35    27.8 3407.29
    31.8 3404.29    35.8 3402.08    37.4 3401.64    39.8 3401.08    51.9 3400.27
    59.7 3400.78    62.4 3401.66    75.9 3406.38   116.1 3408.25   120.1 3408.22
   128.1  3406.8   132.1 3407.31   148.2 3411.08   164.2 3411.26   172.3 3413.49
   176.3    3414   192.3 3413.93   200.3 3413.29   208.4 3413.78   212.4 3414.73
   216.4 3416.46   228.4 3422.95   234.1 3425.28   248.5 3428.67   259.9 3430.41
#Mann= 4 ,-1,0
       0     .06       0    37.4    .045       0    62.4     .06       0
     250      .1       0
Bank Sta=37.4,62.4
XS Rating Curve= 0 ,0
Exp/Cntr=0.3,0.1