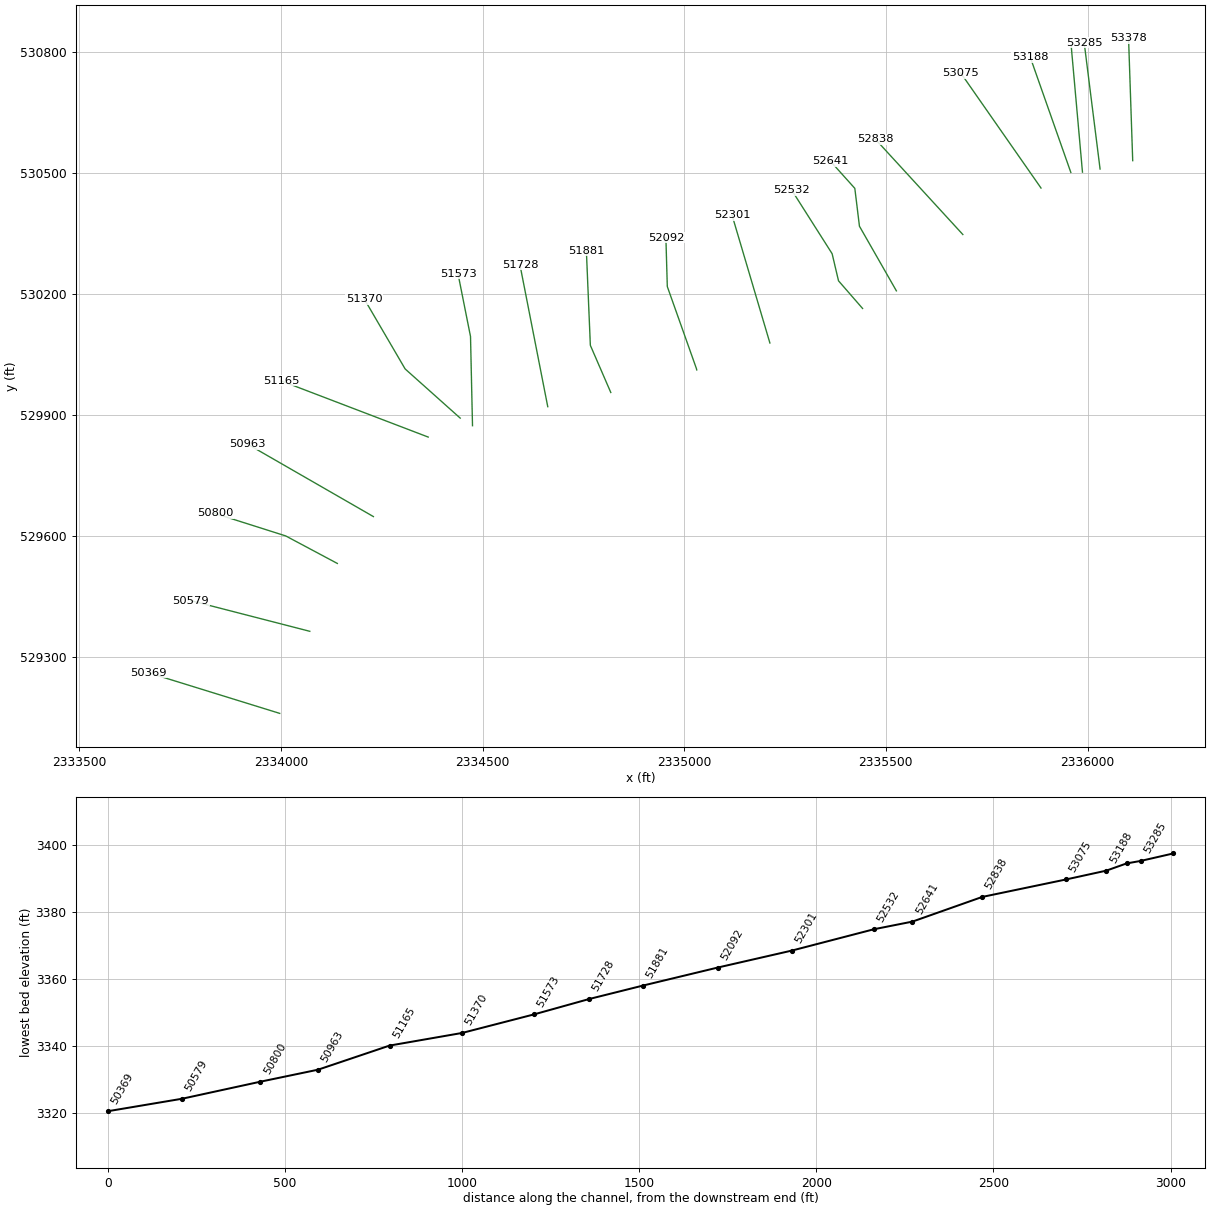
HEC-RAS study NRTHFRK.prj: NRTHFRK

--- NRTHFRK.g01 (geometry) --- (continued)

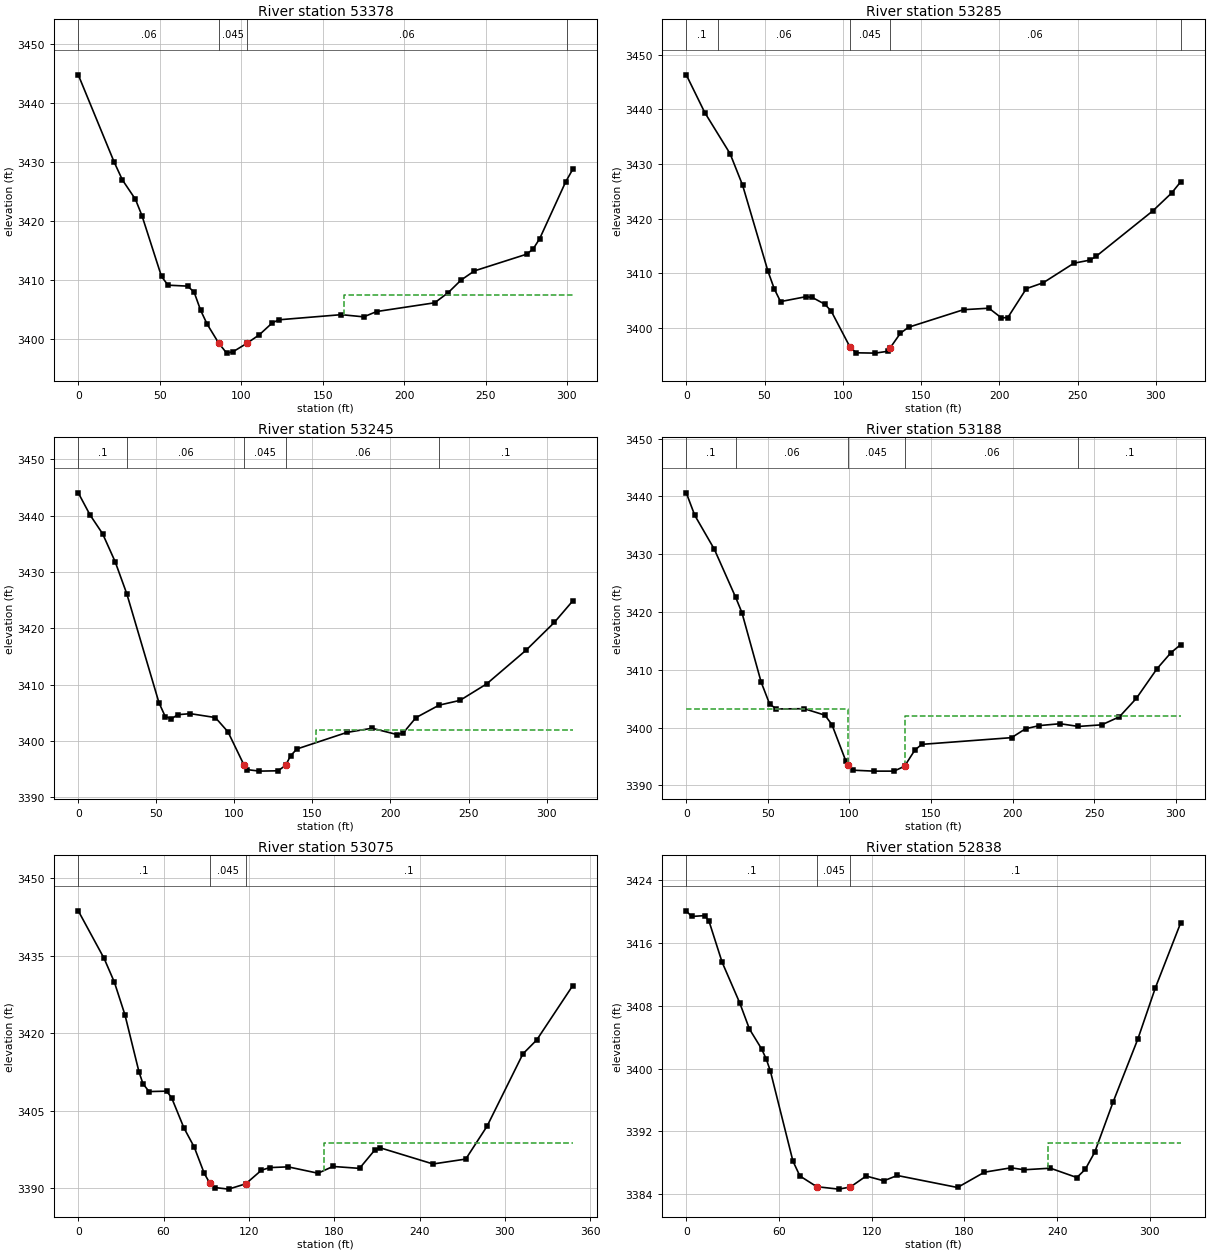
Type RM Length L Ch R = 1 ,53378   ,90.3,92.3,94.4
XS GIS Cut Line= 2
2336111.99908913530530.1225503822336101.69902527530833.402208611
#Sta/Elev= 30
       0 3444.71    22.1  3429.9    27.1 3426.92    35.1 3423.64    39.1 3420.88
    51.1 3410.58    55.1 3409.11    67.1 3408.95    71.1 3407.95    75.1 3404.87
    79.1 3402.52    86.2 3399.31    91.1 3397.61    95.1 3397.86   103.4 3399.25
   111.2 3400.73   119.1 3402.73   123.1 3403.25   161.5 3404.12   175.2 3403.75
   183.2 3404.65   218.8 3406.13   227.1 3407.85     235 3409.98   243.2 3411.53
   275.2 3414.35   279.2 3415.23   283.2 3416.96   299.2  3426.6   303.5  3428.7
#Mann= 4 ,-1,0
       0     .06       0    86.2    .045       0   103.4     .06       0
     300      .1       0
#XS Ineff= 2 , 0
                          163.27         3407.49
Permanent Ineff=
       F       F
Bank Sta=86.2,103.4
XS Rating Curve= 0 ,0
Exp/Cntr(USF)=0,0
Exp/Cntr=0.3,0.1

Type RM Length L Ch R = 1 ,53285   ,40.8,40,39.1
XS GIS Cut Line= 2
     2336031.086      530509.429     2335991.659      530822.729
#Sta/Elev= 30
       0  3446.3    11.8  3439.4      28 3431.86      36 3426.08    52.2 3410.34
    56.2 3407.14    60.2  3404.8    76.3 3405.69    80.4 3405.57    88.4 3404.34
    92.5  3403.1   104.6 3396.47   108.6 3395.43   120.6 3395.37   128.8 3395.71
   130.1 3396.28   136.8 3399.02     142 3400.11   177.1 3403.32   193.3 3403.59
   201.3 3401.82   205.4 3401.89   217.2 3407.17     228 3408.25   247.6 3411.83
   257.8 3412.39   261.8 3413.09   298.1 3421.43     310 3424.67   315.8 3426.72
#Mann= 5 ,-1,0
       0      .1       0      20     .06       0   104.6    .045       0
   130.1     .06       0   315.7      .1       0
Bank Sta=104.6,130.1
XS Rating Curve= 0 ,0
Exp/Cntr=0.5,0.3

Type RM Length L Ch R = 1 ,53245   ,51.4,57.1,64.4
XS GIS Cut Line= 2
     2335987.435      530501.685     2335959.273      530817.097
#Sta/Elev= 30
       0 3444.07     7.5 3440.16    15.6  3436.8    23.6 3431.85    31.1 3426.12
    51.7 3406.77    55.7 3404.32    59.7 3403.91    63.7 3404.65    71.8 3404.83
    87.8 3404.14    95.9  3401.6   106.1 3395.74   107.9  3394.9     116 3394.62
     128 3394.68   132.8 3395.64     136 3397.34     140 3398.55   172.1  3401.5
   188.2 3402.24   204.3 3401.11   208.3 3401.46   216.3 3404.12   231.1 3406.34
   244.5 3407.19   261.6 3410.12   286.9 3416.12   304.9 3421.03   316.7 3424.85
#Mann= 5 ,-1,0
       0      .1       0    31.1     .06       0   106.1    .045       0
   132.8     .06       0   231.1      .1       0
#XS Ineff= 2 , 0
            87.5  3403.2   152.5            3402
Permanent Ineff=
       F       F
Bank Sta=106.1,132.8
XS Rating Curve= 0 ,0
Exp/Cntr=0.5,0.3

Type RM Length L Ch R = 1 ,53188   ,107.3,113.6,121.9
XS GIS Cut Line= 2
     2335958.569      530500.981     2335857.891      530786.823
#Sta/Elev= 30
       0 3440.61     5.2 3436.72    17.2 3430.85    30.3 3422.52    34.1  3419.9
    45.9 3407.87    51.1 3404.07    55.3 3403.22    72.3 3403.27      85 3402.15
    89.3 3400.51    97.8 3394.23    99.3  3393.5   102.4 3392.63   114.9 3392.47
   127.4 3392.47   133.8 3393.32   140.2 3396.14   144.4  3397.1   199.4 3398.26
     208  3399.8   216.5 3400.35   229.2 3400.67   240.4  3400.2   254.7 3400.48
   265.5 3401.86   275.9 3405.05   288.6 3410.19   297.1 3412.95   303.1 3414.35
#Mann= 5 ,-1,0
       0      .1       0    30.3     .06       0    99.3    .045       0
   133.8     .06       0   240.4      .1       0
#XS Ineff= 2 , 0
            99.3  3403.2   133.8            3402
Permanent Ineff=
       F       F
Bank Sta=99.3,133.8
XS Rating Curve= 0 ,0
Exp/Cntr=0.5,0.3

Type RM Length L Ch R = 1 ,53075   ,234.2,236.8,240.4
XS GIS Cut Line= 2
     2335884.645      530462.258     2335685.696      530747.447
#Sta/Elev= 30
       0 3443.73    18.2  3434.5    25.4 3429.91    32.8 3423.62    42.7 3412.55
    45.5 3410.25    49.8 3408.73    62.1 3408.81    65.6 3407.57    74.3  3401.7
    81.6 3397.95    88.6 3392.89    92.6 3390.95    96.2 3390.14   105.7 3389.84
   117.8 3390.87   128.8  3393.5   134.6 3394.01   147.6 3394.15   168.6 3392.92
   179.1 3394.23   197.8 3393.86   208.4 3397.37   212.2 3397.85   249.5 3394.71
   272.5 3395.66   287.5 3402.03   312.7 3416.03   322.4 3418.72   347.7 3429.23
#Mann= 3 ,-1,0
       0      .1       0    92.6    .045       0   117.8      .1       0
#XS Ineff= 2 , 0
                          172.78         3398.85
Permanent Ineff=
       F       F
Bank Sta=92.6,117.8
XS Rating Curve= 0 ,0
Exp/Cntr=0.3,0.1

Type RM Length L Ch R = 1 ,52838   ,202,196.9,192.6
XS GIS Cut Line= 2
2335690.84092223530347.0103039042335474.53958108530582.767321245
#Sta/Elev= 30
       0 3420.12     3.4  3419.4    11.9 3419.51    14.7  3418.8    23.2 3413.56
    34.6 3408.37    40.9 3405.03    48.7 3402.52    51.8 3401.19    54.4 3399.69
      69  3388.2    73.5  3386.3    84.4 3384.93    98.6 3384.62   106.1 3384.88
   116.4 3386.29   127.8 3385.68   136.5 3386.36   175.5 3384.83   192.9 3386.78
   210.1 3387.34   218.6 3387.09   235.6 3387.29   252.7  3386.1   258.1 3387.13
   264.3 3389.34   276.1  3395.7   292.2 3403.78   303.5 3410.29   319.9 3418.59
#Mann= 3 ,0,0
       0      .1       0    84.4    .045       0   106.1      .1       0
#XS Ineff= 2 , 0
                          233.72         3390.53
Permanent Ineff=
       F       F
Bank Sta=84.4,106.1
XS Rating Curve= 0 ,0
Exp/Cntr(USF)=0,0
Exp/Cntr=0.3,0.1

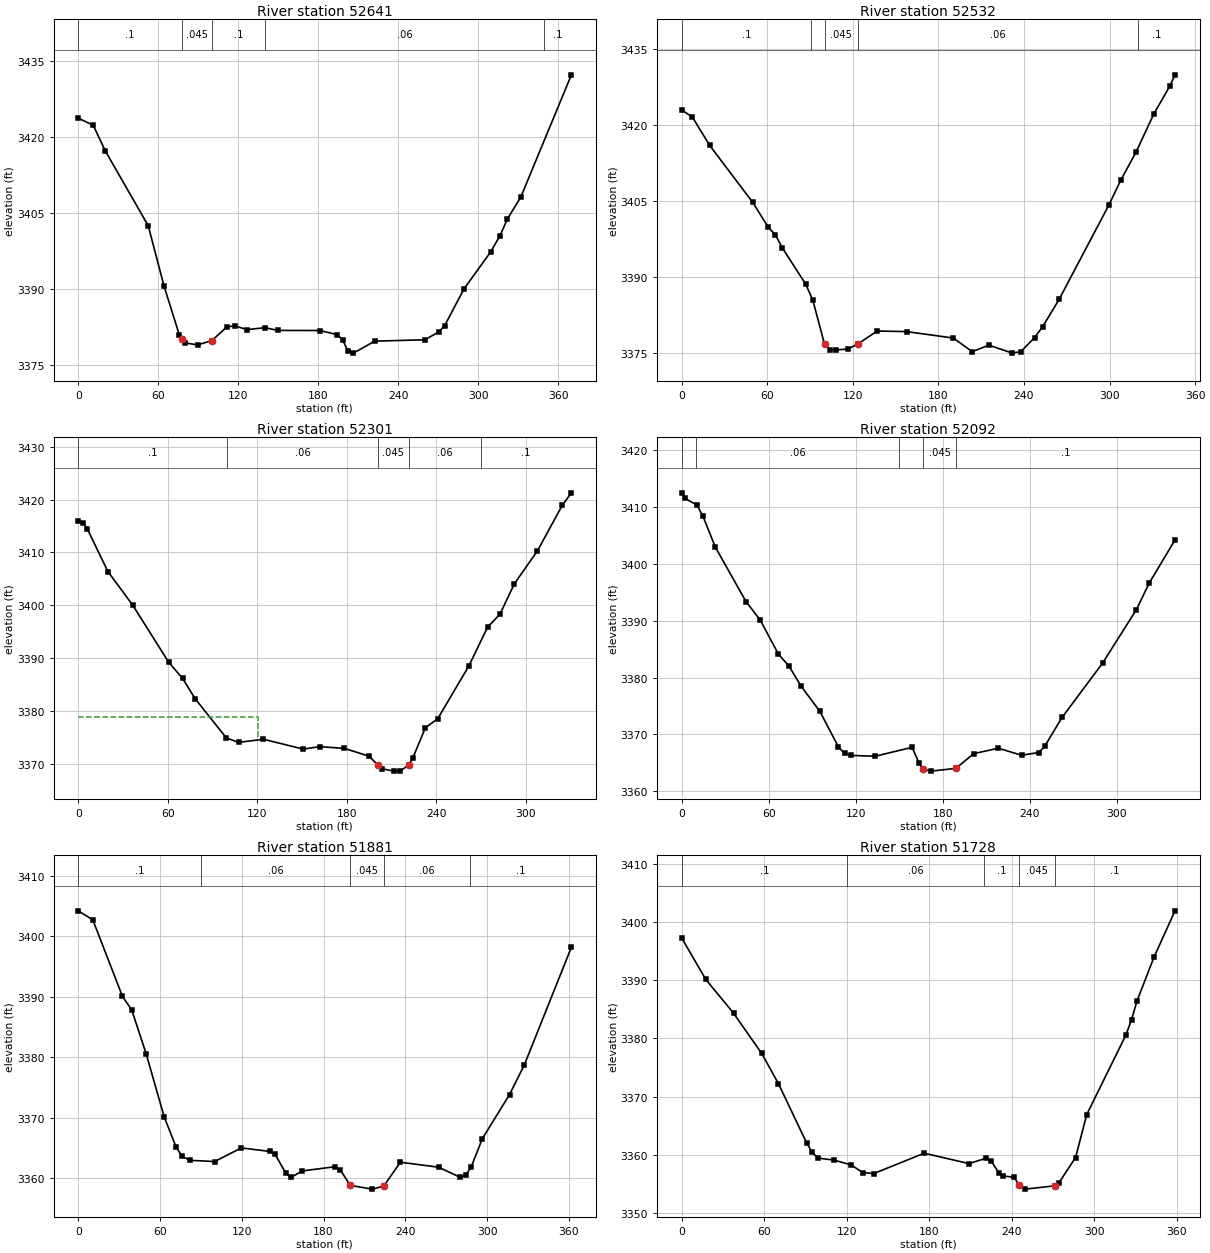
Type RM Length L Ch R = 1 ,52641   ,115.8,108.7,103.4
XS GIS Cut Line= 4
 2335526.0399004530207.3872159652335434.48377716530367.610431633
2335423.03926176530461.4554579532335362.38333011530528.978098842
#Sta/Elev= 30
       0 3423.73    11.3 3422.29    20.3 3417.25    52.5 3402.45    64.3 3390.57
    75.8 3380.88    77.73380.066    80.4 3379.27    89.6 3378.89   100.23379.736
   111.2 3382.38   117.2 3382.69   126.5 3381.91   140.3 3382.29   149.5 3381.75
   181.1 3381.73   194.2 3380.92   198.2  3379.9   202.2 3377.71   206.3 3377.26
   222.4 3379.63   259.9  3379.9   270.6 3381.48   274.8 3382.71   289.3 3389.97
   309.2 3397.25   316.3  3400.5   321.7 3403.73   331.9 3408.14   369.8 3432.28
#Mann= 5 ,-1,0
       0      .1       0    77.7    .045       0   100.2      .1       0
     140     .06       0  349.08      .1       0
Bank Sta=77.7,100.2
XS Rating Curve= 0 ,0
Exp/Cntr(USF)=0,0
Exp/Cntr=0.3,0.1

Type RM Length L Ch R = 1 ,52532   ,230.1,231,231.8
XS GIS Cut Line= 4
2335442.29207269530163.6261247082335382.59851952530232.210207078
2335366.72257452530299.5242138482335267.02163997530456.378550379
#Sta/Elev= 30
       0 3422.89     7.4 3421.51    19.6 3415.91    49.8 3404.67    60.4 3399.89
    65.7 3398.26    70.6 3395.69    86.9 3388.58    91.9 3385.42   100.1 3376.74
   104.2 3375.65   108.4 3375.61   116.6 3375.79   123.7 3376.83   137.1 3379.34
   157.7 3379.22   190.5 3377.95   203.7 3375.27   215.3 3376.55   231.9 3374.98
   237.9  3375.3   247.4 3378.04     253 3380.16   264.6 3385.56   299.5 3404.15
     308 3409.14   318.5 3414.56   331.2  3422.2   342.2 3427.57   345.9 3429.83
#Mann= 5 ,-1,0
       0      .1       0   90.92     .06       0   100.1    .045       0
   123.7     .06       0  320.08      .1       0
Bank Sta=100.1,123.7
XS Rating Curve= 0 ,0
Exp/Cntr(USF)=0,0
Exp/Cntr=0.3,0.1

Type RM Length L Ch R = 1 ,52301   ,208.1,209.4,208.6
XS GIS Cut Line= 2
2335212.46017831530078.0641918892335118.61515199530395.077268605
#Sta/Elev= 30
       0 3415.89     3.2 3415.61       6 3414.52    19.9 3406.39    36.6    3400
    60.7 3389.22      70 3386.16    78.3 3382.36    99.3 3374.91   107.5 3374.07
   124.2 3374.66   150.8  3372.8   161.8 3373.26   178.5 3372.93   195.1 3371.44
   200.93369.754   203.5 3369.08   211.6 3368.63     216 3368.67   221.6 3369.83
   224.3 3371.11   232.7 3376.84     241 3378.54   261.9 3388.55   274.4 3395.87
   282.7 3398.31   292.4 3404.09   307.8 3410.29   324.6 3418.98   330.6 3421.28
#Mann= 5 ,-1,0
       0      .1       0     100     .06       0   200.9    .045       0
   221.6     .06       0     270      .1       0
#XS Ineff= 2 , 0
          120.28 3378.82
Permanent Ineff=
       F       F
Bank Sta=200.9,221.6
XS Rating Curve= 0 ,0
Exp/Cntr(USF)=0,0
Exp/Cntr=0.3,0.1

Type RM Length L Ch R = 1 ,52092   ,218,211.2,205.2
XS GIS Cut Line= 4
2335031.07960141530011.2830550072335030.15254067530015.027279574
     2334958.122      530217.955     2334954.602       530339.05
#Sta/Elev= 30
       0 3412.47       2 3411.52    10.4 3410.34    14.6 3408.36    23.1 3402.95
    44.3 3393.36    54.1 3390.12    66.6 3384.15    74.1 3381.96    82.3  3378.5
    95.3 3374.05     108 3367.86   112.3 3366.66   116.5 3366.32   133.5 3366.18
   158.9 3367.74   163.7 3364.97   166.63363.912   171.7 3363.56   189.1 3364.04
   201.4 3366.63   218.4 3367.58   234.4 3366.36   246.4 3366.83   250.4 3367.92
   262.4    3373   290.3 3382.53   313.7 3391.96   322.5 3396.61   340.3 3404.18
#Mann= 5 ,-1,0
       0      .1       0      10     .06       0     150      .1       0
   166.6    .045       0   189.1      .1       0
Bank Sta=166.6,189.1
XS Rating Curve= 0 ,0
Exp/Cntr=0.3,0.1

Type RM Length L Ch R = 1 ,51881   ,150.2,152.2,157.3
XS GIS Cut Line= 3
     2334818.017      529955.346     2334767.326      530072.218
     2334757.469      530306.664
#Sta/Elev= 30
       0 3404.18    10.7  3402.7    32.5 3390.03    39.3 3387.78      50 3380.46
      63 3370.18    71.8 3365.15    76.1 3363.62    81.9 3362.94   100.1 3362.74
   119.7 3364.99   140.4 3364.42   144.4 3363.96   152.4 3360.79   156.4 3360.14
   164.4 3361.19   188.4 3361.88   192.4 3361.34   199.63358.796   215.9 3358.18
   224.23358.673   236.4 3362.63   264.5  3361.8   280.5 3360.11   284.5  3360.5
   288.5 3361.92   296.5  3366.5   316.5 3373.81   327.3 3378.68   361.9 3398.17
#Mann= 5 ,-1,0
       0      .1       0      90     .06       0   199.6    .045       0
   224.2     .06       0   287.4      .1       0
Bank Sta=199.6,224.2
XS Rating Curve= 0 ,0
Exp/Cntr=0.3,0.1

Type RM Length L Ch R = 1 ,51728   ,156,155.7,156.6
XS GIS Cut Line= 2
     2334661.719      529920.144     2334592.723      530272.166
#Sta/Elev= 30
       0 3397.22    17.4 3390.14    37.7 3384.32    58.1 3377.44    70.3 3372.25
    90.8 3362.08    94.8 3360.49    98.9 3359.49   110.9 3359.13   123.3  3358.3
   131.5 3357.01   139.6 3356.83   176.3 3360.32   208.9 3358.54   221.2 3359.45
   225.2 3358.93   230.5 3356.96   233.4 3356.42   241.5  3356.2   245.6 3354.85
   249.7 3354.16   271.4 3354.73   274.2 3355.21   286.4 3359.58   294.5 3366.94
   323.1 3380.64   327.1 3383.24   331.2 3386.51   343.4 3393.93   358.7 3401.89
#Mann= 5 ,-1,0
       0      .1       0     120     .06       0     220      .1       0
   245.6    .045       0   271.4      .1       0
Bank Sta=245.6,271.4
XS Rating Curve= 0 ,0
Exp/Cntr=0.3,0.1

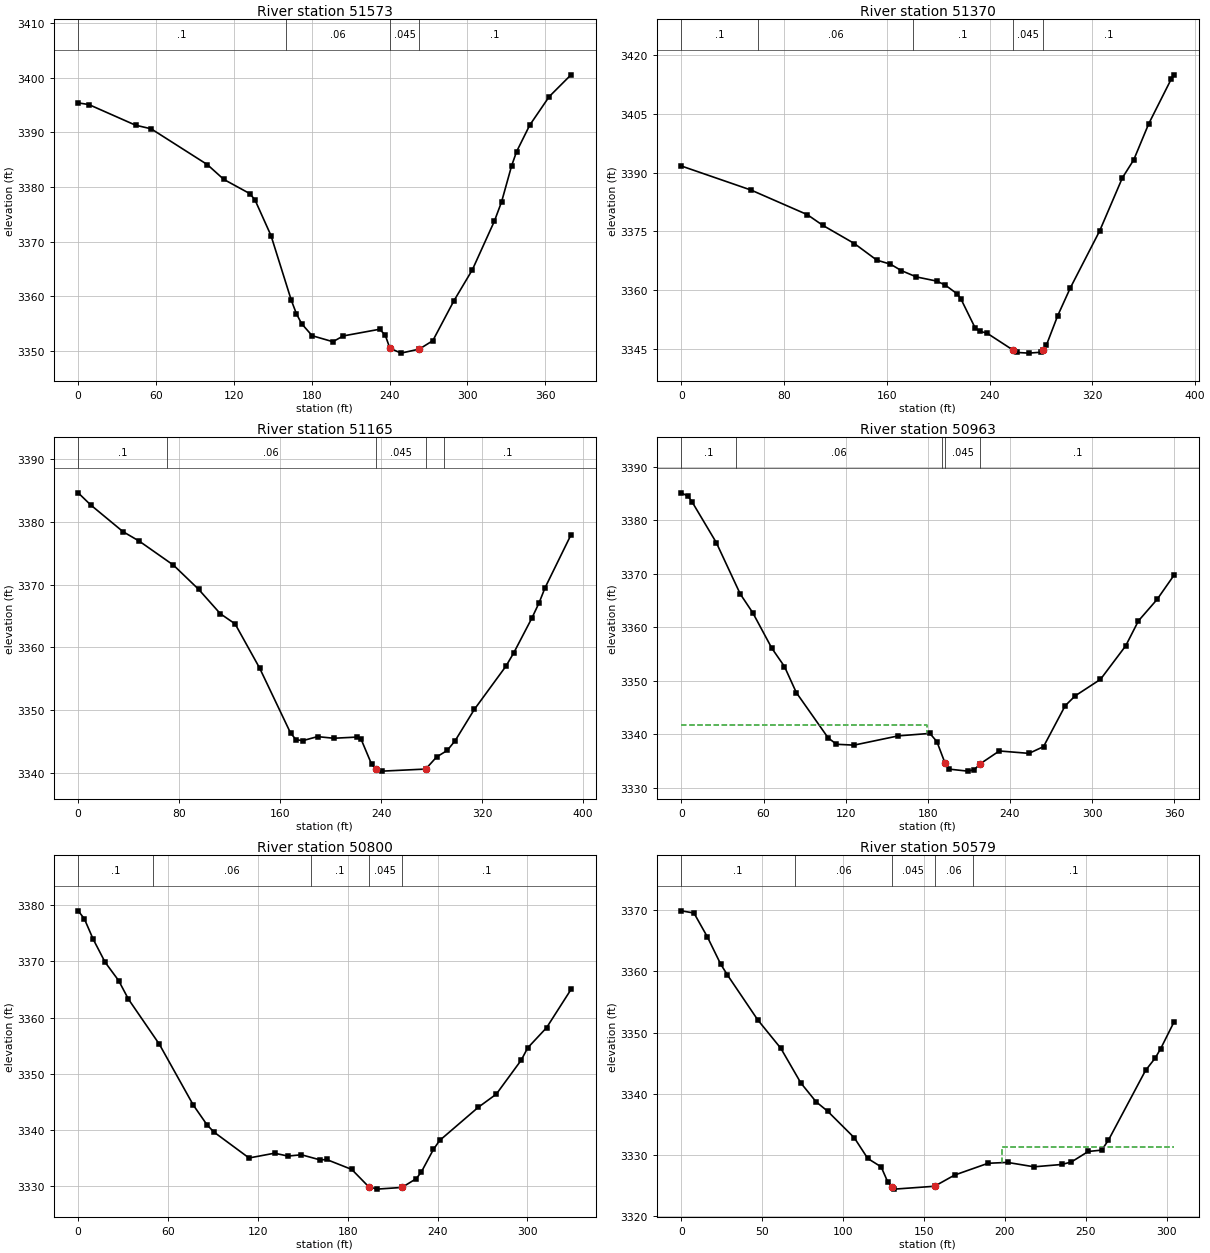
Type RM Length L Ch R = 1 ,51573   ,200.6,203,212.3
XS GIS Cut Line= 3
     2334475.148      529872.973     2334470.219      530094.043
     2334439.241      530249.637
#Sta/Elev= 30
       0 3395.38     8.2 3395.08    44.2  3391.3    56.2 3390.64    99.5 3384.09
   112.2 3381.38   132.2 3378.78   136.2 3377.65   148.6 3371.09   164.2 3359.28
   168.2 3356.77   172.2 3354.96   180.3 3352.76   196.3 3351.66   204.3 3352.72
   232.3 3353.94   236.6 3352.89   240.2 3350.47   248.8 3349.57   262.9 3350.31
   273.3 3351.85   289.6 3359.17   303.8 3364.84   320.8 3373.76   326.3 3377.27
     334 3383.84   337.8 3386.43     348 3391.31     363 3396.53   379.8 3400.52
#Mann= 4 ,-1,0
       0      .1       0     160     .06       0   240.2    .045       0
   262.9      .1       0
Bank Sta=240.2,262.9
XS Rating Curve= 0 ,0
Exp/Cntr=0.3,0.1

Type RM Length L Ch R = 1 ,51370   ,193.7,204.8,223.7
XS GIS Cut Line= 3
2334444.64768933529891.8299464282334308.11456239530013.757203974
     2334206.907      530186.977
#Sta/Elev= 30
       0 3391.67    54.3 3385.54    98.1 3379.28   110.1 3376.57   134.7 3371.93
   152.2  3367.7   162.8 3366.68   171.3 3365.04     183 3363.43   198.8 3362.37
   205.5 3361.35   214.8  3359.1   217.7 3357.81   228.7 3350.48   232.3 3349.61
     238 3349.11   258.6 3344.73   261.5  3344.2   270.3 3344.03   279.7 3344.25
   281.43344.814   284.3 3346.13     293 3353.54   302.8  3360.6   325.7 3375.15
   343.4 3388.67   352.2 3393.22   363.9 3402.43   381.4 3413.79   383.7 3414.88
#Mann= 5 ,-1,0
       0      .1       0      60     .06       0     180      .1       0
   258.6    .045       0   281.4      .1       0
Bank Sta=258.6,281.4
XS Rating Curve= 0 ,0
Exp/Cntr=0.3,0.1

Type RM Length L Ch R = 1 ,51165   ,205.8,201.8,199.7
XS GIS Cut Line= 2
     2334365.317      529844.811     2334000.622      529984.212
#Sta/Elev= 30
       0 3384.62     9.8 3382.71    35.5 3378.43    48.3 3376.93    75.5 3373.09
    95.4 3369.24   112.6 3365.35   124.3 3363.73   143.7  3356.7   168.2 3346.35
   172.5 3345.28   177.8 3345.11   189.6 3345.76   202.4  3345.5   221.1 3345.69
   223.9 3345.45   232.5 3341.33  235.56 3340.64     241 3340.26   275.3 3340.59
   283.9 3342.51   292.3 3343.55   298.6  3345.1   313.8 3350.09   338.9    3357
   345.1 3359.13   359.5 3364.69   365.2 3367.13   369.8 3369.47   390.4 3377.93
#Mann= 5 ,-1,0
       0      .1       0      70     .06       0  235.56    .045       0
   275.3     .06       0     290      .1       0
Bank Sta=235.56,275.3
XS Rating Curve= 0 ,0
Exp/Cntr=0.3,0.1

Type RM Length L Ch R = 1 ,50963   ,160.2,163,167.3
XS GIS Cut Line= 2
     2334229.436      529647.679     2333917.544       529827.21
#Sta/Elev= 30
       0  3385.1       5 3384.44     7.9 3383.38    25.5 3375.81      43  3366.2
    52.2 3362.66    66.1 3356.04    75.3 3352.63      84 3347.74   107.2 3339.29
   113.3 3338.09   126.1 3337.93   158.4 3339.66   181.5 3340.12   186.6  3338.6
   192.4 3334.68   195.3 3333.45   209.1 3333.07   213.8 3333.32   218.4 3334.46
   232.2 3336.84   253.9 3336.39   264.5 3337.65   280.3 3345.29   287.6 3347.14
   306.1 3350.23   324.5 3356.49   333.8 3361.16   347.4 3365.16   359.9 3369.74
#Mann= 5 ,-1,0
       0      .1       0      40     .06       0     190      .1       0
   192.4    .045       0   218.4      .1       0
#XS Ineff= 2 , 0
          179.15 3341.73
Permanent Ineff=
       F       F
Bank Sta=192.4,218.4
XS Rating Curve= 0 ,0
Exp/Cntr=0.3,0.1

Type RM Length L Ch R = 1 ,50800   ,221,220.8,221.8
XS GIS Cut Line= 3
     2334140.022      529531.511     2334011.886      529599.804
     2333836.579      529655.423
#Sta/Elev= 30
       0 3378.98     4.1 3377.57      10 3373.94      18 3369.83      27 3366.58
    33.6 3363.25    54.2 3355.25    76.9 3344.42    85.9 3340.97    90.5 3339.66
   114.1 3335.02   131.1 3335.87   140.1 3335.36   149.1 3335.59   161.7 3334.67
   165.9 3334.75   182.7 3332.98   193.9 3329.93   199.5 3329.48   216.2 3329.78
   225.7 3331.33   229.1  3332.5   237.2 3336.53   241.4 3338.14   267.1 3344.02
   279.2 3346.37   295.8  3352.4   300.2 3354.61   312.8  3358.2   329.1 3364.99
#Mann= 5 ,-1,0
       0      .1       0      50     .06       0   155.2      .1       0
   193.9    .045       0   216.2      .1       0
Bank Sta=193.9,216.2
XS Rating Curve= 0 ,0
Exp/Cntr=0.3,0.1

Type RM Length L Ch R = 1 ,50579   ,211.1,209.8,209.1
XS GIS Cut Line= 2
      2334071.73      529363.245     2333776.735      529439.282
#Sta/Elev= 30
       0 3369.92     7.8 3369.56    16.1 3365.65    24.3 3361.21    28.5 3359.42
    47.2 3352.09    61.5 3347.43    73.9 3341.75    83.3 3338.68    90.4 3337.15
   106.9  3332.8   115.2 3329.42   123.5 3328.04   127.6 3325.56   130.3 3324.82
   131.7  3324.4   156.5 3324.87   168.9  3326.7   189.6 3328.63   201.6 3328.77
     218 3328.05     235 3328.43     241 3328.83   251.5 3330.56   259.8 3330.78
     264 3332.42   286.9 3343.81   292.8 3345.81   296.2 3347.34   304.6 3351.79
#Mann= 5 ,-1,0
       0      .1       0      70     .06       0   130.3    .045       0
   156.5     .06       0     180      .1       0
#XS Ineff= 2 , 0
                          198.45         3331.35
Permanent Ineff=
       F       F
Bank Sta=130.3,156.5
XS Rating Curve= 0 ,0
Exp/Cntr=0.3,0.1

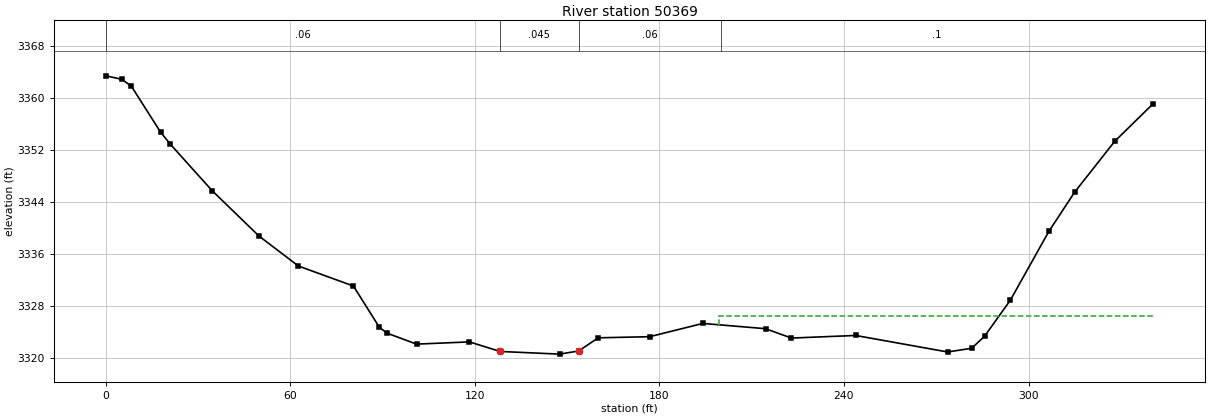
Type RM Length L Ch R = 1 ,50369   ,193.5,187.2,181.5
XS GIS Cut Line= 2
     2333997.101      529159.776     2333671.833      529260.454
#Sta/Elev= 30
       0 3363.47     5.2 3362.93     8.3 3361.86    17.8 3354.79      21 3352.93
    34.5 3345.83    49.8 3338.82    62.6 3334.22    80.5 3331.14    88.9 3324.81
    91.4  3323.9     101 3322.21   118.2 3322.55   128.2 3321.08   147.5 3320.67
   153.7 3321.15   160.1 3323.18   176.8 3323.35   194.1 3325.39   214.5 3324.58
   222.9 3323.14   243.8 3323.54   273.7    3321   281.5 3321.57   285.7 3323.41
   294.1 3328.97   306.6 3339.53     315 3345.58     328 3353.38   340.5 3359.17
#Mann= 4 ,-1,0
       0     .06       0   128.2    .045       0   153.7     .06       0
     200      .1       0
#XS Ineff= 2 , 0
                          199.26         3326.55
Permanent Ineff=
       F       F
Bank Sta=128.2,153.7
XS Rating Curve= 0 ,0
Exp/Cntr=0.3,0.1