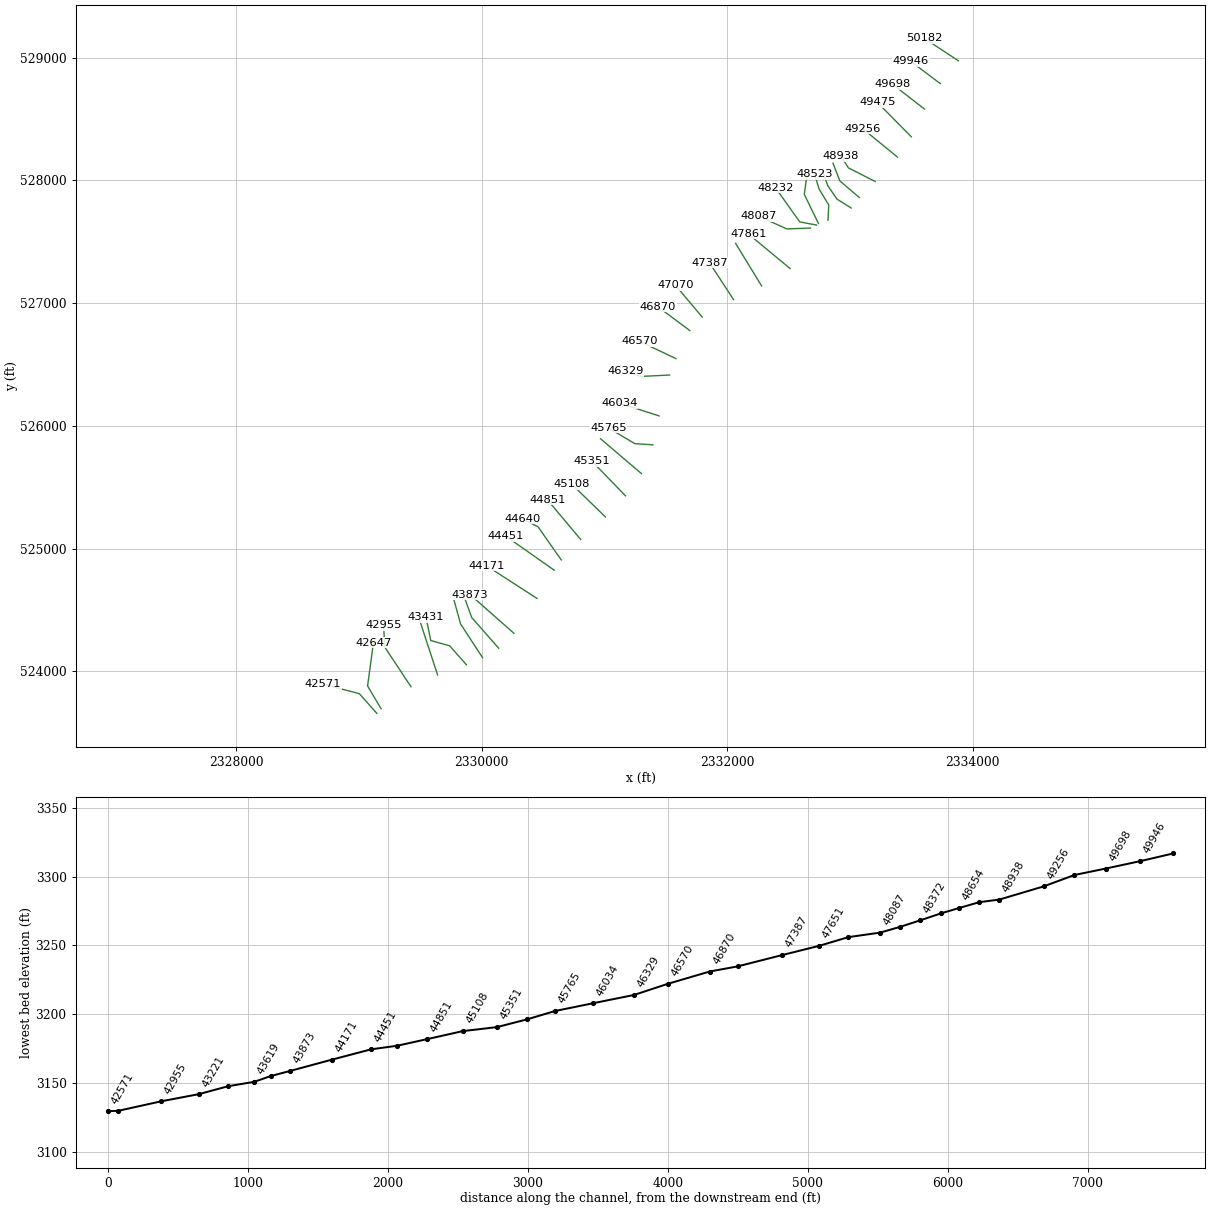
HEC-RAS study NRTHFRK.prj: NRTHFRK

--- NRTHFRK.g01 (geometry) --- (continued)

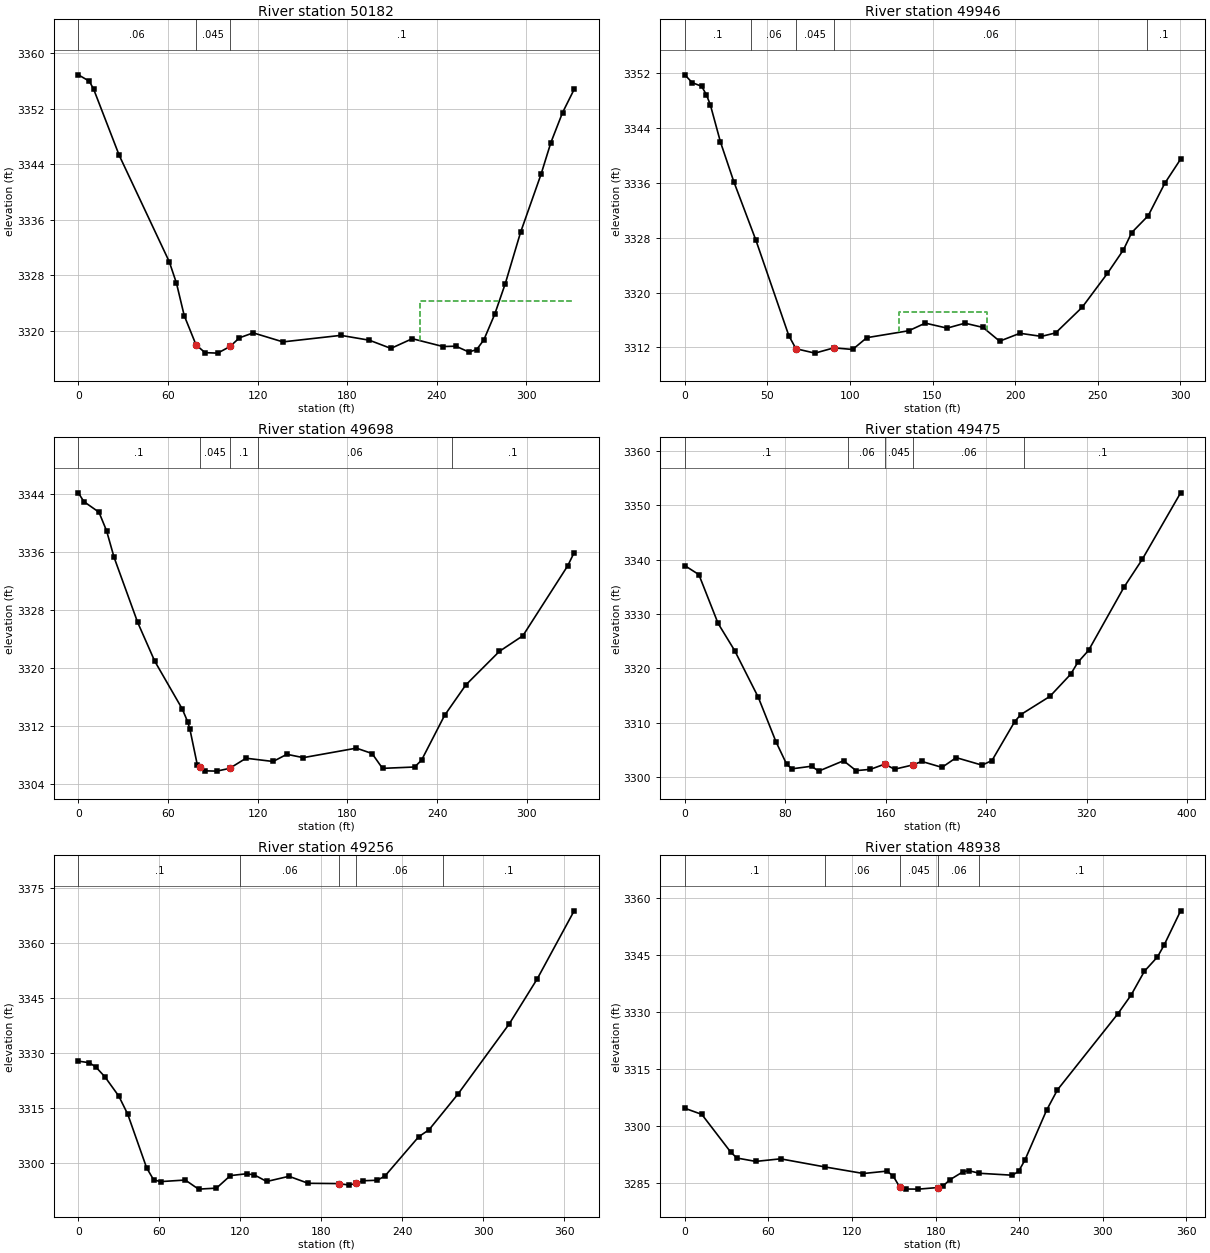
Type RM Length L Ch R = 1 ,50182   ,236.8,236.1,234.5
XS GIS Cut Line= 2
     2333883.046      528973.908     2333605.653      529156.256
#Sta/Elev= 30
       0 3356.87     7.3 3355.96    10.2 3354.83    27.4 3345.25    60.9 3329.93
    65.7 3326.85    70.9 3322.17    78.8 3317.96    84.8 3316.83    93.3 3316.76
   101.6 3317.72   107.9 3318.97   117.1 3319.68     137 3318.38   175.8 3319.32
   194.9 3318.62   209.3 3317.44   223.6 3318.84   244.2 3317.71   252.8 3317.76
   261.5 3316.92   266.7 3317.27   271.5 3318.66   278.8 3322.36   285.9 3326.79
   296.1 3334.16   309.8 3342.52   316.4  3347.1   324.2 3351.41     332 3354.78
#Mann= 3 ,-1,0
       0     .06       0    78.8    .045       0   101.6      .1       0
#XS Ineff= 2 , 0
                          228.92         3324.21
Permanent Ineff=
       F       F
Bank Sta=78.8,101.6
XS Rating Curve= 0 ,0
Exp/Cntr=0.3,0.1

Type RM Length L Ch R = 1 ,49946   ,247.9,248,247.3
XS GIS Cut Line= 2
     2333736.605      528787.336     2333496.526      528967.572
#Sta/Elev= 30
       0 3351.71     4.5 3350.57    10.2 3350.04    13.1  3348.8    15.5 3347.31
    21.6 3341.92    29.7 3336.13      43 3327.66      63 3313.71    67.3 3311.82
    78.8 3311.18    90.3 3311.95   101.6 3311.71   110.2 3313.43   135.6 3314.44
   145.6 3315.55   158.8 3314.82   169.6 3315.54   180.6 3314.92   190.6 3312.92
   202.9 3314.07   215.9 3313.62   224.5 3314.12   240.6 3317.86   255.9  3322.8
   265.6 3326.23   270.6 3328.74   280.6  3331.2   290.6 3335.91   300.2 3339.43
#Mann= 5 ,-1,0
       0      .1       0      40     .06       0    67.3    .045       0
    90.3     .06       0     280      .1       0
#XS Ineff= 1 ,-1
   129.5  183.22  3317.2
Permanent Ineff=
       F
Bank Sta=67.3,90.3
XS Rating Curve= 0 ,0
Exp/Cntr=0.3,0.1

Type RM Length L Ch R = 1 ,49698   ,225.8,223.1,220.5
XS GIS Cut Line= 2
     2333607.061      528580.347     2333345.156      528783.816
#Sta/Elev= 30
       0 3344.14     3.7 3342.93    13.8 3341.47    18.9  3338.9    23.9 3335.25
    39.7 3326.27    51.1 3320.93    69.5 3314.34    73.1 3312.59    74.6 3311.58
    79.6 3306.62    81.2 3306.28    84.7  3305.8    92.6 3305.76   101.2 3306.14
   112.2 3307.54   130.3 3307.09   139.5 3308.08   150.5 3307.62     186 3308.93
   196.5 3308.19   203.5 3306.14     225 3306.33   229.6 3307.27     245 3313.44
   259.2 3317.64   281.7 3322.28   297.4 3324.43   327.4 3334.08   331.7  3335.9
#Mann= 5 ,-1,0
       0      .1       0    81.2    .045       0   101.2      .1       0
     120     .06       0     250      .1       0
Bank Sta=81.2,101.2
XS Rating Curve= 0 ,0
Exp/Cntr=0.3,0.1

Type RM Length L Ch R = 1 ,49475   ,217.2,219.4,221.2
XS GIS Cut Line= 2
     2333500.046      528354.349     2333222.652      528635.263
#Sta/Elev= 30
       0 3338.88    11.2 3337.23    26.5 3328.26    39.7 3323.26    58.5 3314.68
    72.6  3306.5    81.1 3302.37    85.2 3301.52   100.9    3302   106.6  3301.1
   126.4 3303.01   136.4 3301.19   147.8 3301.43   159.2 3302.39     167 3301.45
     182 3302.26   188.6 3302.89   204.8 3301.79   216.1 3303.58   236.7  3302.2
   244.6 3303.05   262.6 3310.17   267.4 3311.47   290.7 3314.84   307.2  3318.9
   312.9 3321.08   321.5  3323.3   349.8 3334.95   364.2 3340.01   394.8 3352.26
#Mann= 5 ,-1,0
       0      .1       0     130     .06       0   159.2    .045       0
     182     .06       0     270      .1       0
Bank Sta=159.2,182
XS Rating Curve= 0 ,0
Exp/Cntr=0.3,0.1

Type RM Length L Ch R = 1 ,49256   ,312.3,317.5,321.8
XS GIS Cut Line= 2
     2333387.399      528188.899     2333102.965      528421.233
#Sta/Elev= 30
       0 3327.73     8.2  3327.3    13.1 3326.08    19.7 3323.45      30 3318.18
    36.6 3313.25    50.6 3298.62    55.8 3295.36      61 3294.89    79.2 3295.32
      89 3292.84   102.3 3293.11   112.6 3296.53   124.7 3297.03   130.4 3296.71
   139.5 3294.92     156 3296.34   170.2 3294.43     193 3294.35   200.4 3293.95
   205.6 3294.42   210.8 3295.12   221.4 3295.26   227.1 3296.42   252.1 3307.13
   259.7 3309.02   281.1 3318.73   319.2 3337.93   339.9 3350.19   367.2 3368.71
#Mann= 5 ,-1,0
       0      .1       0     120     .06       0     193    .045       0
   205.6     .06       0     270      .1       0
Bank Sta=193,205.6
XS Rating Curve= 0 ,0
Exp/Cntr=0.3,0.1

Type RM Length L Ch R = 1 ,48938   ,149.9,143.8,138.5
XS GIS Cut Line= 3
     2333205.529      527990.115     2332987.362      528101.371
     2332928.257      528195.244
#Sta/Elev= 30
       0 3304.59    12.2 3302.97      33    3293    37.4 3291.46    50.9 3290.57
    68.7 3291.25   100.3 3289.13   128.2 3287.38   145.2 3288.02   149.7  3286.6
   154.2 3283.83   158.7 3283.29   167.7 3283.26   181.7 3283.68   185.6 3284.18
   190.1  3285.7   199.5 3287.81   203.6 3288.14   211.4 3287.44     235 3286.93
   239.5 3287.94     244 3290.87   259.6 3304.06   267.4 3309.44   310.7 3329.48
   320.3 3334.46   329.8 3340.72   339.2 3344.51   343.9 3347.59   355.8 3356.66
#Mann= 5 ,-1,0
       0      .1       0   100.3     .06       0   154.2    .045       0
   181.7     .06       0   211.4      .1       0
#XS Ineff= 2 , 0
                           203.6          3287.7
Permanent Ineff=
       F       F
Bank Sta=154.2,181.7
XS Rating Curve= 0 ,0
Exp/Cntr=0.3,0.1

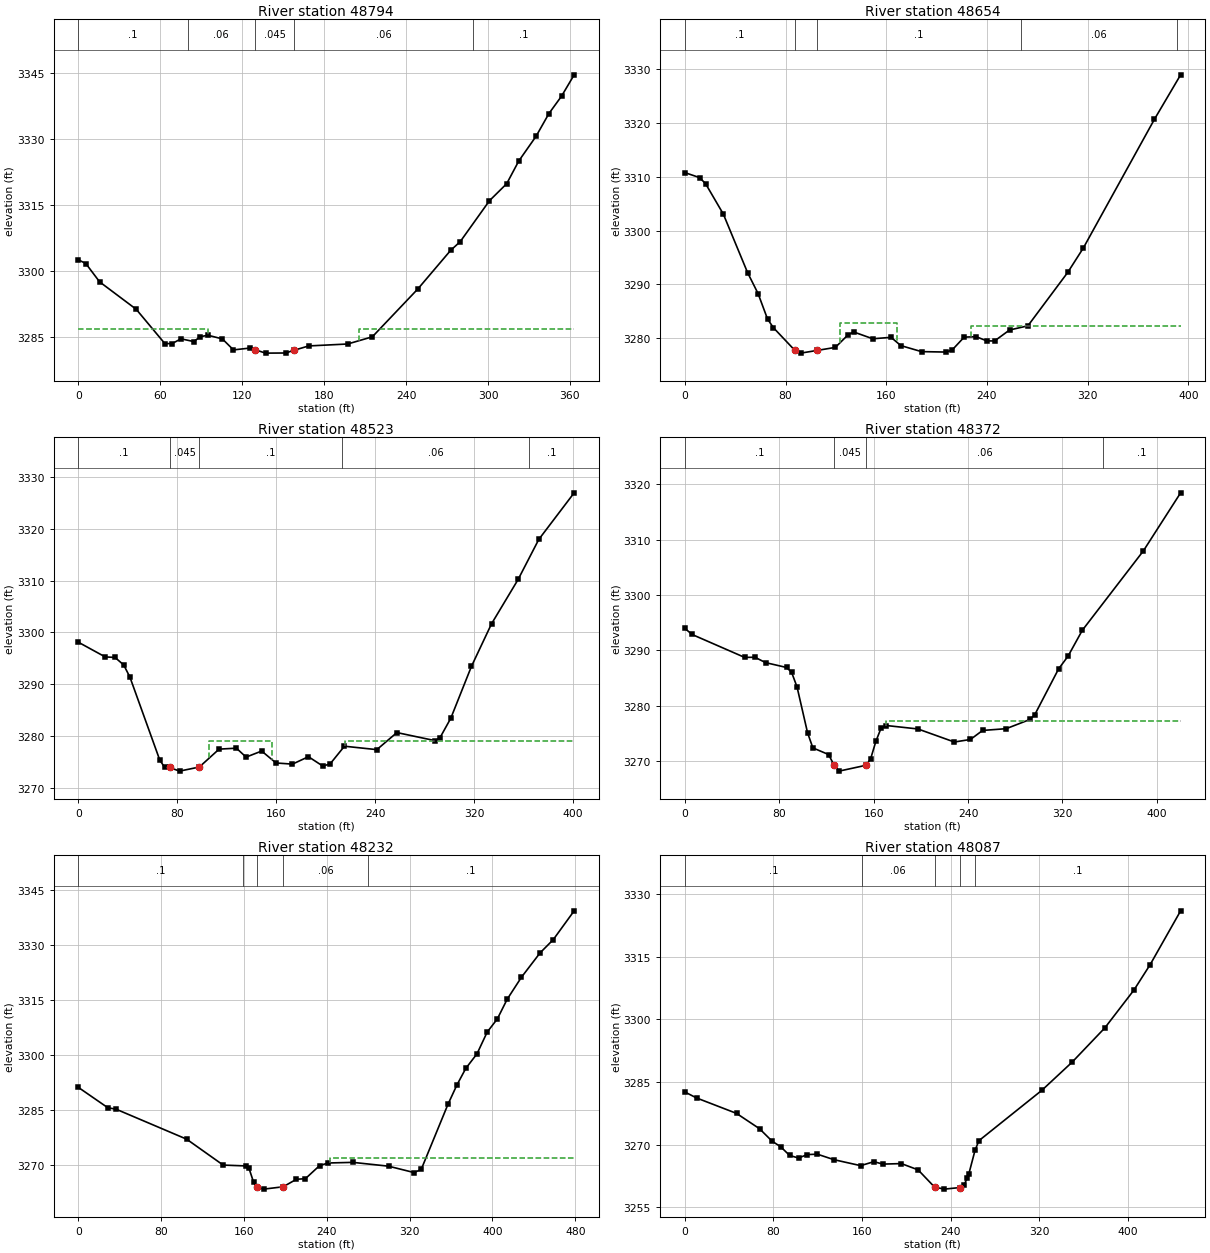
Type RM Length L Ch R = 1 ,48794   ,130.7,140.7,141.3
XS GIS Cut Line= 3
      2333076.37      527859.339     2332917.723      527995.089
     2332862.114      528139.016
#Sta/Elev= 30
       0 3302.54     5.5 3301.67    15.6 3297.52    42.4  3291.3    63.4 3283.51
    68.7 3283.53    75.2 3284.61    84.5 3283.98    89.4  3285.1      95 3285.41
   105.5 3284.58   113.6 3282.09   125.9 3282.52   129.1 3282.17   137.1 3281.36
   151.8 3281.39   158.2 3282.03   168.7 3282.99   197.2 3283.43   215.3 3285.06
   248.7 3295.94   272.6 3304.65   279.7 3306.66   301.1 3315.94   313.7 3319.79
   322.5 3324.92   335.2 3330.54   344.6 3335.69   353.9 3339.66   363.1 3344.48
#Mann= 5 ,-1,0
       0      .1       0      80     .06       0   129.1    .045       0
   158.2     .06       0   288.8      .1       0
#XS Ineff= 2 , 0
           94.85 3286.72  205.27         3286.72
Permanent Ineff=
       F       F
Bank Sta=129.1,158.2
XS Rating Curve= 0 ,0
Exp/Cntr=0.3,0.1

Type RM Length L Ch R = 1 ,48654   ,147.9,130.7,103.6
XS GIS Cut Line= 4
      2333010.13      527774.291     2332894.007      527847.073
     2332818.864      527957.471     2332778.339      528073.776
#Sta/Elev= 30
       0 3310.81    11.7 3309.88    16.5 3308.75    30.6 3303.09    49.9 3292.18
    58.2  3288.3    65.7 3283.57    70.3 3281.97    87.3 3277.76      92 3277.22
   105.1 3277.72   119.6 3278.29   129.8 3280.66   134.1 3281.16   149.3 3279.89
   163.8 3280.16   171.6 3278.62     188  3277.5   207.3 3277.42   212.2 3277.77
   221.9  3280.2   231.5 3280.27   239.8  3279.5     246 3279.48   257.9 3281.52
   272.5  3282.3   304.2 3292.26   316.5 3296.77     373 3320.73   393.8    3329
#Mann= 5 ,-1,0
       0      .1       0    87.3    .045       0   105.1      .1       0
     267     .06       0   390.6      .1       0
#XS Ineff= 2 ,-1
  123.25  168.61 3282.84  227.26   393.8 3282.18
Permanent Ineff=
       F       F
Bank Sta=87.3,105.1
XS Rating Curve= 0 ,0
Exp/Cntr=0.3,0.1

Type RM Length L Ch R = 1 ,48523   ,136.5,150.7,160.6
XS GIS Cut Line= 4
     2332821.161      527675.519     2332827.768      527798.824
     2332749.204      527927.533      2332712.04      528048.463
#Sta/Elev= 30
       0 3298.13    21.7  3295.3    29.7 3295.19    36.7 3293.74    41.7  3291.4
    65.8 3275.44    69.8    3274    73.8 3273.99    81.8 3273.29    97.8 3274.08
   113.8 3277.53   127.8 3277.71   135.6 3275.99   148.2 3277.16   159.8 3274.86
   173.1 3274.64     186 3276.07   197.6 3274.27   203.5 3274.67   215.1 3278.09
   241.3 3277.43   257.5 3280.72   288.6 3279.15   292.4 3279.75   301.1 3283.49
   317.8 3293.49     334 3301.67   355.5 3310.22   372.2 3317.93   400.8 3326.91
#Mann= 5 ,-1,0
       0      .1       0    73.8    .045       0    97.8      .1       0
   213.5     .06       0   364.3      .1       0
#XS Ineff= 2 ,-1
  105.96  156.93 3279.19  215.35   400.8 3279.08
Permanent Ineff=
       F       F
Bank Sta=73.8,97.8
XS Rating Curve= 0 ,0
Exp/Cntr=0.3,0.1

Type RM Length L Ch R = 1 ,48372   ,136.3,140.5,144
XS GIS Cut Line= 3
     2332743.989      527647.653     2332628.387      527884.943
     2332649.247      528039.658
#Sta/Elev= 30
       0 3293.98     6.1 3292.87    50.6 3288.73    59.5 3288.74    68.4 3287.78
    86.2  3286.9    90.5 3286.02    95.1 3283.38     104 3275.11   108.5 3272.37
   121.8 3271.17   126.3 3269.33   130.7 3268.17   153.6 3269.23   157.4 3270.36
   161.9 3273.56   166.3 3275.94   170.8 3276.41   197.5 3275.79   228.4 3273.43
     242 3273.89   252.3 3275.52   272.3 3275.84   292.4  3277.5   296.5 3278.36
   316.7 3286.64   324.7 3288.94   336.8 3293.62   388.5 3307.96   420.1 3318.46
#Mann= 4 ,-1,0
       0      .1       0   126.3    .045       0   153.6     .06       0
     354      .1       0
#XS Ineff= 2 , 0
                           170.1         3277.16
Permanent Ineff=
       F       F
Bank Sta=126.3,153.6
XS Rating Curve= 0 ,0
Exp/Cntr=0.3,0.1

Type RM Length L Ch R = 1 ,48232   ,132,144.5,154.8
XS GIS Cut Line= 3
2332728.20910969527635.3100883912332591.15750546527660.742344846
 2332394.7639695527937.671359582
#Sta/Elev= 30
       0 3291.25    28.5  3285.7    36.6 3285.29   104.6 3277.14   139.9 3270.08
   161.9 3269.85   164.8 3269.23   169.3 3265.39   172.43264.222   179.1 3263.53
   197.83264.168   210.7 3266.22   219.3 3266.37   233.1 3269.96   241.4 3270.65
   265.2 3270.82   299.6 3269.78   324.3 3268.04   331.2 3268.91     357 3286.62
   365.6 3291.87   374.2  3296.4   385.1 3300.41   394.9 3306.31   404.7  3309.9
   414.2 3315.25     428 3321.26     446 3327.89   458.7 3331.49   478.9 3339.34
#Mann= 5 ,-1,0
       0      .1       0  159.39     .06       0   172.4    .045       0
   197.8     .06       0  279.39      .1       0
#XS Ineff= 2 , 0
                          243.17         3271.93
Permanent Ineff=
       F       F
Bank Sta=172.4,197.8
XS Rating Curve= 0 ,0
Exp/Cntr(USF)=0,0
Exp/Cntr=0.3,0.1

Type RM Length L Ch R = 1 ,48087   ,234.1,226.6,219.2
XS GIS Cut Line= 3
       2332678.8      527611.147     2332486.709      527603.325
     2332253.765      527708.497
#Sta/Elev= 30
       0 3282.61    10.6 3281.17    46.7 3277.47    67.5 3273.79    78.7 3270.84
    86.7 3269.44    94.7 3267.38   102.7 3266.77   110.7  3267.6   119.8 3267.68
   134.7 3266.37   158.8 3264.94   170.8 3265.89   178.8 3265.31   195.6 3265.43
   210.7 3263.93   225.6 3259.79   234.5 3259.31   248.8  3259.7   252.1 3260.21
   255.1 3261.98   256.5 3262.94   262.1 3268.59   265.6 3270.92   322.6 3283.03
   349.8 3289.75   379.4 3297.98   405.7 3307.06   420.3 3313.14   447.8 3326.03
#Mann= 5 ,-1,0
       0      .1       0     160     .06       0   225.6    .045       0
   248.8     .06       0   262.2      .1       0
Bank Sta=225.6,248.8
XS Rating Curve= 0 ,0
Exp/Cntr=0.3,0.1

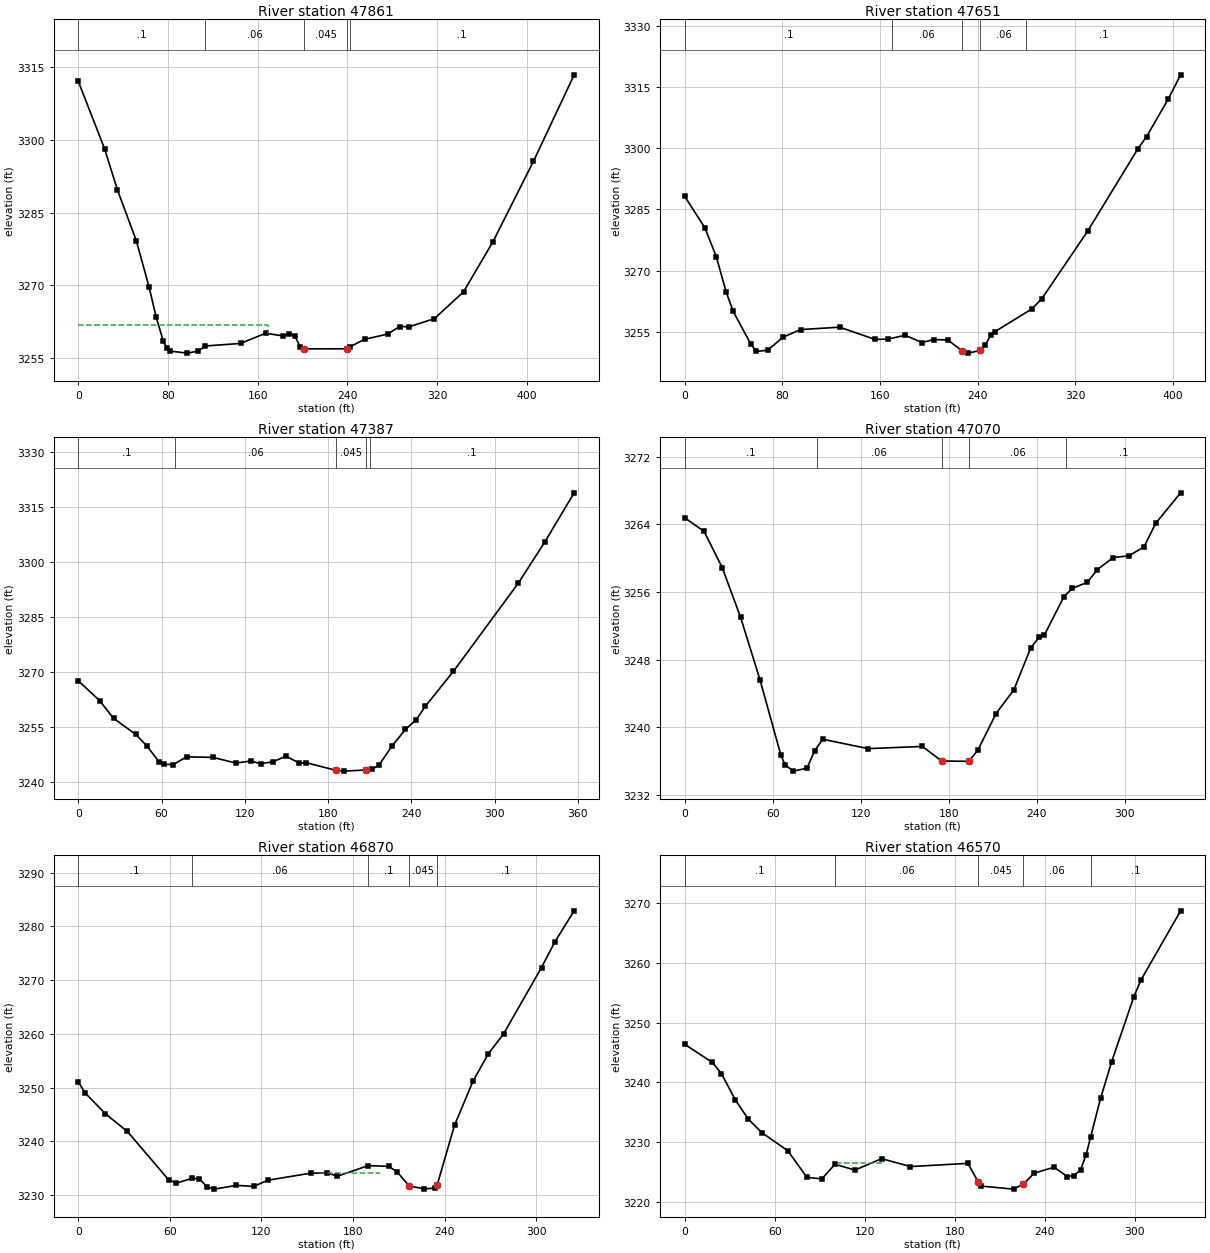
Type RM Length L Ch R = 1 ,47861   ,220.5,209.3,196.3
XS GIS Cut Line= 2
     2332512.784      527280.855     2332172.061      527563.342
#Sta/Elev= 30
       0 3312.01    23.4 3298.14    34.8 3289.73    51.8 3279.14    63.1 3269.67
    69.4 3263.48    75.7 3258.59    78.7 3257.14      82 3256.44    97.2 3256.03
     107 3256.45   113.3  3257.5   144.7 3258.03   167.1 3260.12   182.5 3259.58
   188.2 3260.01     193 3259.62   198.2 3257.23   201.2 3256.91   239.8 3256.92
   242.1 3257.31   255.4 3258.87   276.2 3259.97   286.6 3261.51   295.1 3261.46
   317.7 3263.13   343.7 3268.66     370 3279.01   406.1 3295.56   442.4 3313.37
#Mann= 5 ,-1,0
       0      .1       0   113.3     .06       0   201.2    .045       0
   239.8     .06       0   242.1      .1       0
#XS Ineff= 2 , 0
          168.96 3261.75
Permanent Ineff=
       F       F
Bank Sta=201.2,239.8
XS Rating Curve= 0 ,0
Exp/Cntr=0.3,0.1

Type RM Length L Ch R = 1 ,47651   ,263.8,264.8,265
XS GIS Cut Line= 2
      2332280.71      527139.177     2332068.628      527485.984
#Sta/Elev= 30
       0 3288.19    16.4 3280.52    25.8 3273.43    33.8 3264.82    39.7 3259.93
    53.9 3252.05    58.6 3250.11      68 3250.41    80.4  3253.6    94.9 3255.49
     127 3256.07     156 3253.07   166.4 3253.14   180.5 3254.08   194.6 3252.31
     204 3253.03   215.7 3252.94   227.4 3250.22   232.1  3249.7   242.3 3250.36
   246.2  3251.6   250.8 3254.07     254 3254.93   284.7 3260.59   292.8 3263.11
   330.6 3279.82   371.3 3299.83   378.6 3302.91   396.2 3312.05   406.5 3318.08
#Mann= 5 ,-1,0
       0      .1       0     170     .06       0   227.4    .045       0
   242.3     .06       0     280      .1       0
Bank Sta=227.4,242.3
XS Rating Curve= 0 ,0
Exp/Cntr=0.3,0.1

Type RM Length L Ch R = 1 ,47387   ,313.5,316.2,317.9
XS GIS Cut Line= 2
     2332052.113       527027.92     2331856.545      527326.922
#Sta/Elev= 30
       0 3267.61    15.3  3262.2    25.4 3257.36    41.3 3253.02    49.3  3249.9
    58.3 3245.46    61.5 3244.86    68.4 3244.77      78 3246.89    97.1 3246.73
   113.6 3245.18   124.1 3245.73   131.4 3245.04   140.1 3245.52   149.7 3247.06
   159.2 3245.17     164  3245.3   185.8  3243.2   191.6 3242.99   207.1 3243.31
   211.8 3243.53   216.6 3244.61   226.1 3249.86   235.7 3254.33   243.6 3257.03
     250 3260.63   270.3 3270.17     317 3294.15   336.1 3305.37   357.3 3318.79
#Mann= 5 ,-1,0
       0      .1       0      70     .06       0   185.8    .045       0
   207.1     .06       0     210      .1       0
Bank Sta=185.8,207.1
XS Rating Curve= 0 ,0
Exp/Cntr=0.3,0.1

Type RM Length L Ch R = 1 ,47070   ,197.2,200.2,206.2
XS GIS Cut Line= 2
     2331796.571      526885.373     2331579.273      527144.392
#Sta/Elev= 30
       0 3264.76    13.1 3263.17    25.5 3258.89      38 3253.02    51.3 3245.59
    65.4 3236.77    68.3 3235.58      74 3234.82    83.3 3235.17    88.5 3237.23
      94 3238.59   124.9 3237.48     162 3237.74  175.04 3236.02   193.63235.977
   199.8 3237.31   212.2 3241.63   224.3 3244.42   235.8 3249.38   241.5 3250.64
   245.1  3250.9   258.5 3255.46   264.2 3256.42   274.5 3257.15   281.2 3258.65
   292.1 3260.07   302.6 3260.27     313 3261.32     321 3264.12     338 3267.72
#Mann= 5 ,-1,0
       0      .1       0      90     .06       0  175.04    .045       0
   193.6     .06       0     260      .1       0
Bank Sta=175.04,193.6
XS Rating Curve= 0 ,0
Exp/Cntr=0.3,0.1

Type RM Length L Ch R = 1 ,46870   ,297.5,300.4,304.8
XS GIS Cut Line= 2
     2331695.745      526775.855     2331434.988      526969.685
#Sta/Elev= 30
       0 3251.05     4.4 3249.01    17.8 3245.11    32.1 3241.83    59.3 3232.79
    64.3  3232.2    74.2 3233.07    79.2 3233.04    84.2 3231.54    89.2 3231.09
   103.6 3231.79     115  3231.6   124.1 3232.74   152.2 3234.06   163.1  3234.1
   169.8  3233.5     190 3235.47   203.4 3235.32   208.8 3234.33   216.8 3231.67
   226.5 3231.16   233.7 3231.27   235.1 3231.83   246.5 3242.98   258.6 3251.18
   268.6 3256.27   278.6 3259.98   303.5 3272.35   312.3 3277.16   324.9 3282.91
#Mann= 5 ,-1,0
       0      .1       0    74.2     .06       0     190      .1       0
   216.8    .045       0   235.1      .1       0
#XS Ineff= 1 ,-1
   157.9   197.9 3234.16
Permanent Ineff=
       F
Bank Sta=216.8,235.1
XS Rating Curve= 0 ,0
Exp/Cntr=0.3,0.1

Type RM Length L Ch R = 1 ,46570   ,226,240.8,251
XS GIS Cut Line= 2
      2331582.75      526547.258     2331283.749      526688.936
#Sta/Elev= 30
       0 3246.35    18.4 3243.32    24.4 3241.47    33.8    3237    42.4 3233.82
    51.4 3231.56    68.7 3228.54    81.5 3224.07    91.4 3223.83   100.2 3226.27
   113.5  3225.3   131.2 3227.21   150.5 3225.89   188.8 3226.42   195.73223.304
   197.6 3222.62   219.3 3222.11   225.93222.975     233 3224.78   246.3 3225.78
   255.2 3224.21   259.6 3224.37     264 3225.34   267.7  3227.9   270.6 3230.79
   277.3  3237.3   284.7 3243.44   299.4 3254.25   304.2 3257.11   330.7 3268.71
#Mann= 5 ,-1,0
       0      .1       0   100.2     .06       0   195.7    .045       0
   225.9     .06       0   270.6      .1       0
#XS Ineff= 1 ,-1
   102.5   131.2 3226.43
Permanent Ineff=
       F
Bank Sta=195.7,225.9
XS Rating Curve= 0 ,0
Exp/Cntr=0.3,0.1

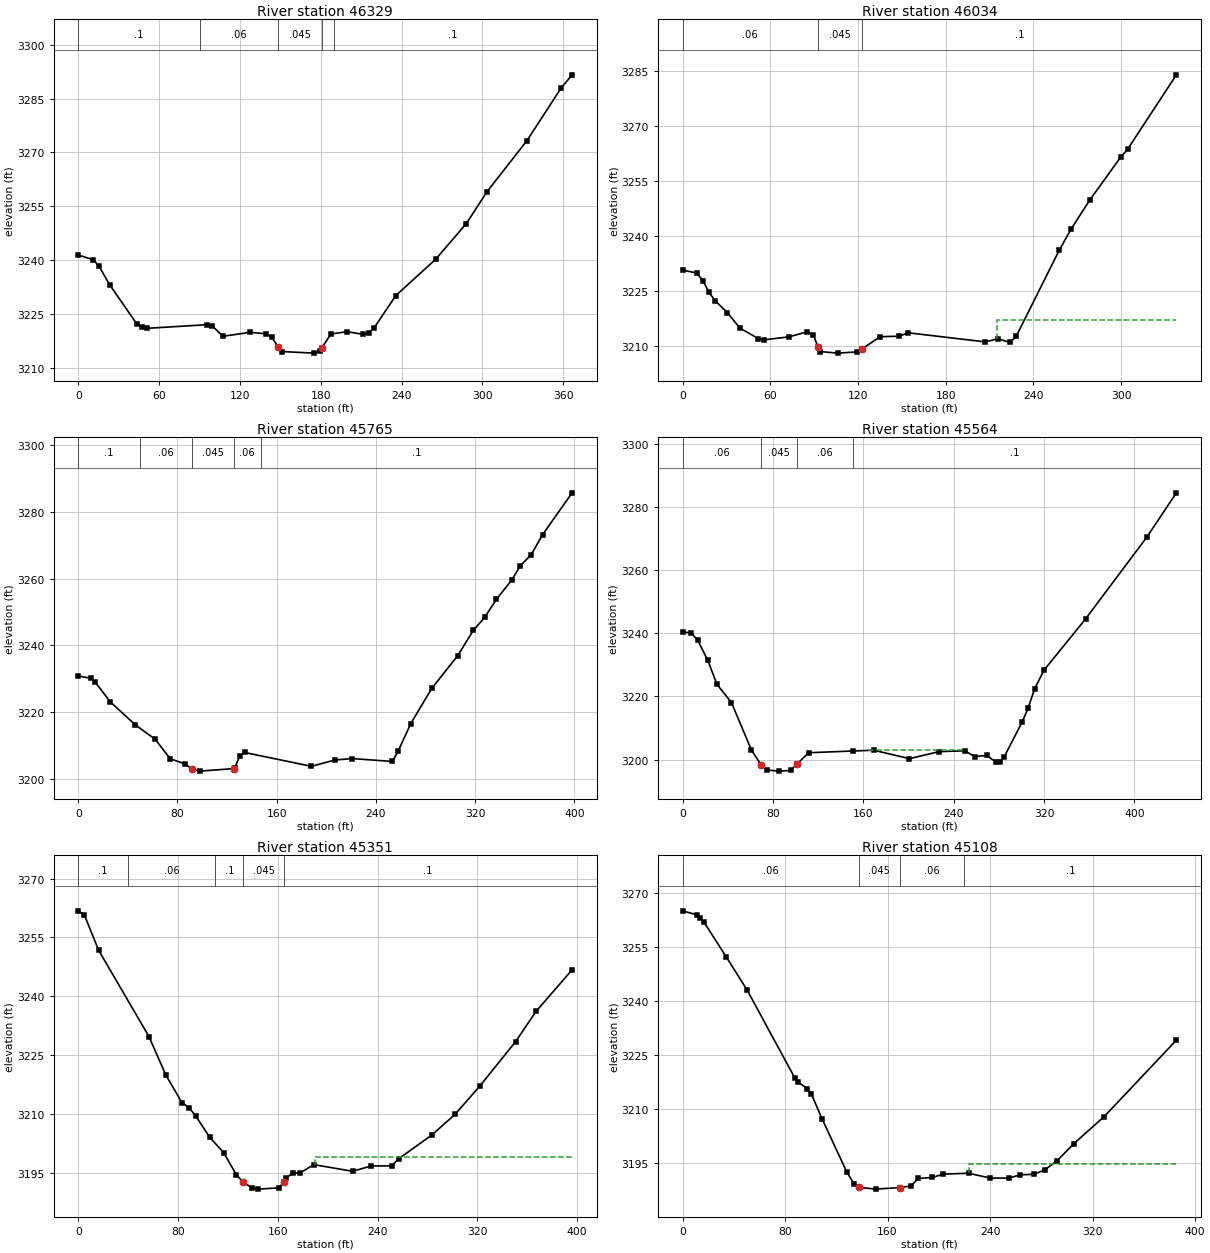
Type RM Length L Ch R = 1 ,46329   ,303.8,295.3,285.5
XS GIS Cut Line= 3
     2331531.468      526413.403     2331297.656      526402.103
     2331172.492      526445.563
#Sta/Elev= 30
       0 3241.42    11.3 3240.07    15.3 3238.37    23.3 3233.14    43.3 3222.29
    47.3 3221.39    51.4 3220.99    95.8    3222    99.4 3221.68   107.4 3218.76
   127.4 3219.86   139.5 3219.47   143.5 3218.51   148.5 3215.76   151.5  3214.5
   175.3 3214.07   179.5 3214.61   180.8 3215.52   187.5 3219.41   199.5 3220.04
   211.5 3219.31   215.5 3219.67   219.5 3221.06   235.7 3230.12   265.3 3240.24
     288 3250.18   303.4 3259.08     333  3273.3   358.4 3287.97   366.5 3291.64
#Mann= 5 ,-1,0
       0      .1       0      90     .06       0   148.5    .045       0
   180.8     .06       0     190      .1       0
Bank Sta=148.5,180.8
XS Rating Curve= 0 ,0
Exp/Cntr=0.3,0.1

Type RM Length L Ch R = 1 ,46034   ,262.1,268.3,274.9
XS GIS Cut Line= 2
     2331445.418      526080.503     2331123.817      526183.936
#Sta/Elev= 30
       0 3230.63     9.7 3229.82    13.9 3227.77    18.1 3224.57    22.3 3222.29
    30.7 3219.03    39.1 3214.88    51.7 3211.98    55.9 3211.64    72.7 3212.42
    85.3 3213.82    89.5 3213.01    92.7 3209.57    93.7 3208.44   106.4    3208
     119 3208.32   122.9 3209.18   135.1 3212.47   148.4 3212.62   154.1 3213.55
   207.2 3211.06   215.6  3211.9     224 3210.93   228.2 3212.54   257.6 3235.99
     266 3241.95   278.6 3249.73   299.6 3261.34   304.4 3263.53   337.8 3283.83
#Mann= 3 ,-1,0
       0     .06       0    92.7    .045       0   122.9      .1       0
#XS Ineff= 2 , 0
            85.3 3213.82  215.29         3216.97
Permanent Ineff=
       F       F
Bank Sta=92.7,122.9
XS Rating Curve= 0 ,0
Exp/Cntr=0.3,0.1

Type RM Length L Ch R = 1 ,45765   ,218.7,201.6,184
XS GIS Cut Line= 3
     2331394.136      525844.952     2331247.243      525854.513
     2331031.683      525983.153
#Sta/Elev= 30
       0 3230.89      10 3230.21    13.3 3229.23      26 3223.09    46.1 3216.25
    62.1 3211.95    74.1 3206.17    86.1 3204.57    91.9    3203    98.2 3202.44
   125.2 3203.19   126.2 3203.37   130.2 3207.01   134.2 3208.01     188 3203.88
   206.7 3205.74   220.6  3206.2   253.3 3205.33   257.9 3208.39   268.1 3216.63
   285.1  3227.2     306 3236.96   318.5  3244.5   327.8 3248.43   337.1 3253.75
   349.8 3259.71   356.3 3263.76   365.1 3267.09   374.4 3273.12   398.2 3285.64
#Mann= 5 ,-1,0
       0      .1       0      50     .06       0    91.9    .045       0
   125.2     .06       0   147.2      .1       0
Bank Sta=91.9,125.2
XS Rating Curve= 0 ,0
Exp/Cntr=0.3,0.1

Type RM Length L Ch R = 1 ,45564   ,215,212.8,210.3
XS GIS Cut Line= 2
     2331301.132      525611.139     2330968.232      525894.496
#Sta/Elev= 30
       0 3240.51     7.8    3240    13.5 3237.78    22.3 3231.47    30.5 3223.81
    43.3 3218.06      61 3203.01    69.5 3198.36    74.8 3196.69    85.3 3196.34
    95.7 3196.56   101.1 3198.53   111.6 3202.16   151.3 3202.72   169.3 3202.96
   200.9 3200.29   227.1 3202.51     250 3202.78   258.6 3200.94   269.2 3201.29
   277.4 3199.23   280.9 3199.23   284.9 3200.96   300.7 3211.93   305.9 3216.23
   311.7  3222.4   319.9 3228.26   356.8 3244.53     411 3270.41   437.2 3284.46
#Mann= 4 ,-1,0
       0     .06       0    69.5    .045       0   101.1     .06       0
   151.3      .1       0
#XS Ineff= 1 ,-1
   163.9   248.1 3203.04
Permanent Ineff=
       F
Bank Sta=69.5,101.1
XS Rating Curve= 0 ,0
Exp/Cntr=0.3,0.1

Type RM Length L Ch R = 1 ,45351   ,241.9,242.9,243.9
XS GIS Cut Line= 2
     2331171.623      525429.479     2330896.089      525713.704
#Sta/Elev= 30
       0  3261.8       5 3260.69    16.4 3251.71    56.7 3229.71    70.1 3219.97
    83.1 3212.87    88.7 3211.59    94.3 3209.39   105.4    3204   116.6 3200.09
   126.7 3194.46   132.3 3192.54   138.9 3191.14   144.4 3190.77   161.1 3191.11
  164.84  3192.7   166.7 3193.66   172.3 3194.88   177.9 3194.93   188.9 3197.02
     220 3195.32   234.8 3196.68   251.2  3196.7   256.8  3198.5   283.7 3204.64
   302.1 3209.87   321.9 3217.07   350.6 3228.41     367 3236.13   395.9 3246.74
#Mann= 5 ,-1,0
       0      .1       0      40     .06       0     110      .1       0
   132.3    .045       0  164.84      .1       0
#XS Ineff= 2 , 0
                          190.15            3199
Permanent Ineff=
       F       F
Bank Sta=132.3,164.84
XS Rating Curve= 0 ,0
Exp/Cntr=0.3,0.1

Type RM Length L Ch R = 1 ,45108   ,259.7,257.1,255
XS GIS Cut Line= 2
     2331008.215      525257.379     2330731.812      525525.959
#Sta/Elev= 30
       0 3265.05    11.2 3263.94      14 3263.01    16.9 3261.84    34.2 3252.22
    50.3 3243.15    87.6 3218.73    90.4 3217.49    97.3 3215.78   100.4 3214.39
   108.8 3207.44   128.3 3192.53   133.9 3189.34   137.5 3188.39   150.6 3187.88
   169.6 3188.31   178.1 3188.75   184.1 3190.83   194.9 3191.11   203.6 3192.05
   223.2 3192.28   240.3 3190.94   254.5 3190.94   263.7 3191.85   274.3 3191.99
   282.8 3193.24   292.4 3195.79   305.4 3200.51   329.1 3208.01   385.4 3229.19
#Mann= 4 ,-1,0
       0     .06       0   137.5    .045       0   169.6     .06       0
     220      .1       0
#XS Ineff= 2 , 0
                           223.6         3194.94
Permanent Ineff=
       F       F
Bank Sta=137.5,169.6
XS Rating Curve= 0 ,0
Exp/Cntr=0.3,0.1

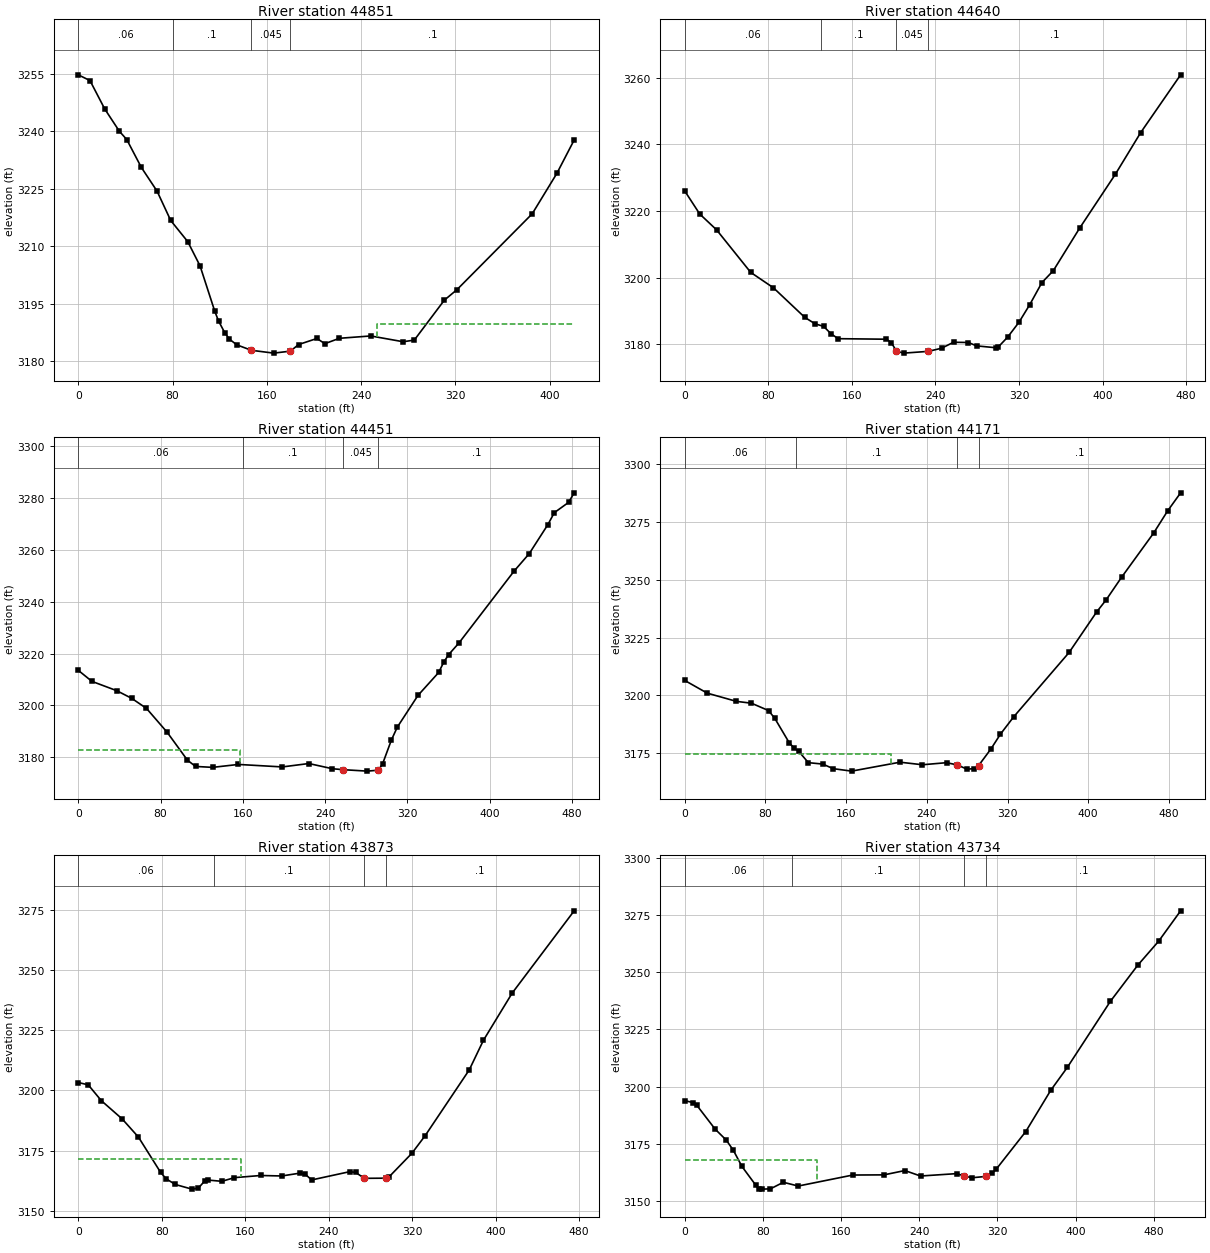
Type RM Length L Ch R = 1 ,44851   ,213.7,210.7,209
XS GIS Cut Line= 2
     2330806.563       525073.98     2330536.244      525396.449
#Sta/Elev= 30
       0 3254.79     9.9 3253.28    22.4 3245.87    34.8 3240.05    41.1 3237.87
    53.5 3230.57    66.8 3224.39    78.4 3216.71    92.9 3211.16   103.3 3204.84
   115.8 3192.97     119 3190.43   124.2  3187.4   128.2 3185.69   134.5 3184.19
   146.9 3182.77   165.8 3182.03     180 3182.55   186.9 3184.27   202.5 3185.86
   209.2  3184.5   221.6 3185.91   248.2 3186.52   275.6 3185.01   285.1 3185.43
   310.6 3195.87   321.3 3198.61   385.2 3218.46   406.1 3229.01   420.8 3237.75
#Mann= 4 ,-1,0
       0     .06       0      80      .1       0   146.9    .045       0
     180      .1       0
#XS Ineff= 2 , 0
                          253.72         3189.59
Permanent Ineff=
       F       F
Bank Sta=146.9,180
XS Rating Curve= 0 ,0
Exp/Cntr=0.3,0.1

Type RM Length L Ch R = 1 ,44640   ,183.3,188.8,197.8
XS GIS Cut Line= 3
      2330648.37      524907.095     2330459.756      525176.544
     2330330.246      525243.472
#Sta/Elev= 30
       0 3225.99    14.3 3219.09    30.4 3214.34    63.1 3201.55    84.9 3196.91
   114.8 3188.05   124.6 3186.11   132.9 3185.33   139.8 3183.16   146.8 3181.63
     193 3181.47   197.8 3180.45   202.6 3177.86   209.6 3177.29   233.1 3177.82
   245.8 3178.76   257.3 3180.56   271.6 3180.48   279.3 3179.47   297.5 3178.92
   300.3 3179.21     309 3182.06   319.9 3186.55   330.3 3191.88   341.9 3198.49
   352.8 3202.06     378 3214.84   412.2 3231.03   436.5 3243.57   474.7 3260.91
#Mann= 4 ,-1,0
       0     .06       0     130      .1       0   202.6    .045       0
   233.1      .1       0
Bank Sta=202.6,233.1
XS Rating Curve= 0 ,0
Exp/Cntr=0.3,0.1

Type RM Length L Ch R = 1 ,44451   ,279.7,280.3,281.3
XS GIS Cut Line= 2
     2330591.003      524823.653     2330196.391      525100.925
#Sta/Elev= 30
       0  3213.5    13.2 3209.26    37.4 3205.66    51.9 3202.71    66.3 3198.83
    86.4 3189.62   106.1 3178.87     114 3176.44   130.6 3176.08   155.7 3177.21
   198.4 3176.25   224.2 3177.56   247.2 3175.55   257.7 3175.19     281 3174.63
   291.9 3174.99     296 3177.48   304.6 3186.71   310.3 3191.62   330.4 3203.85
   350.5 3212.68   355.4 3216.65   360.3 3219.62   370.1    3224   423.9 3251.81
   438.6 3258.53   456.8 3269.77     463 3274.34   476.9 3278.31   482.3 3281.99
#Mann= 4 ,-1,0
       0     .06       0     160      .1       0   257.7    .045       0
   291.9      .1       0
#XS Ineff= 2 , 0
          156.93 3182.73
Permanent Ineff=
       F       F
Bank Sta=257.7,291.9
XS Rating Curve= 0 ,0
Exp/Cntr=0.3,0.1

Type RM Length L Ch R = 1 ,44171   ,301.5,298.5,295.4
XS GIS Cut Line= 2
     2330451.064      524593.317     2330038.198      524860.159
#Sta/Elev= 30
       0 3206.41    22.2 3200.93    51.1 3197.37    66.1 3196.56      83 3193.38
    89.2 3190.02   103.5 3179.46   108.2 3177.18     113 3175.68   122.5 3170.81
   136.8 3170.19   147.1 3168.21   165.4 3167.14   213.4 3171.01   235.6  3169.9
   259.5  3170.8   270.2 3169.83   279.7    3168   287.1 3168.21   291.3 3169.56
   303.5 3176.73     313 3183.19     326 3190.61     381 3218.53   408.3 3236.07
   417.8 3241.36     433 3251.09   464.9 3270.31   478.7 3279.86   491.6  3287.7
#Mann= 4 ,-1,0
       0     .06       0     110      .1       0   270.2    .045       0
   291.3      .1       0
#XS Ineff= 2 , 0
          204.47 3174.72
Permanent Ineff=
       F       F
Bank Sta=270.2,291.3
XS Rating Curve= 0 ,0
Exp/Cntr=0.3,0.1

Type RM Length L Ch R = 1 ,43873   ,141.5,138.9,136.5
XS GIS Cut Line= 2
     2330263.319      524309.092      2329906.95      524623.739
#Sta/Elev= 30
       0 3203.29     9.5 3202.32    22.1 3195.72      42 3188.16    57.6 3180.61
    78.9 3165.91    84.2 3163.25      93 3160.88   108.9 3158.95     115 3159.34
   121.3 3162.41   124.1 3162.73   137.6  3162.2   149.7 3163.73   174.9 3164.62
     195 3164.42   212.3 3165.59   217.6 3165.13   223.7 3162.77     260 3166.19
   265.8 3165.91   274.3 3163.44   294.9 3163.51   297.7 3163.95   319.7  3173.8
   332.5 3181.16   374.8 3208.53   388.4 3220.85     416  3240.5   475.4  3274.7
#Mann= 4 ,-1,0
       0     .06       0     130      .1       0   274.3    .045       0
   294.9      .1       0
#XS Ineff= 2 , 0
          156.29 3171.36
Permanent Ineff=
       F       F
Bank Sta=274.3,294.9
XS Rating Curve= 0 ,0
Exp/Cntr=0.3,0.1

Type RM Length L Ch R = 1 ,43734   ,123.2,114.6,112.6
XS GIS Cut Line= 3
2330138.77236372524187.9608325792329918.82483217524438.190995287
2329859.85339255524602.354732605
#Sta/Elev= 30
       0 3193.89     8.4 3193.06    12.3 3191.87      31 3181.47    42.4 3176.68
    49.6 3172.27    58.5 3165.13    72.8 3156.87    76.2 3155.36    79.2 3155.23
    87.7 3155.36   100.9 3158.22   116.1 3156.58     172 3161.39   203.9 3161.46
   225.3 3163.35   241.3 3160.96   278.6 3162.01   286.1 3160.93   294.5 3160.22
   308.8  3160.8   314.5 3162.07     319 3164.04   349.1 3180.41   374.6 3198.39
   391.6 3208.42   435.6 3237.24   463.8 3253.12   485.1 3263.57   507.6 3276.84
#Mann= 4 ,-1,0
       0     .06       0     110      .1       0   286.1    .045       0
   308.8      .1       0
#XS Ineff= 2 , 0
           135.4  3167.9
Permanent Ineff=
       F       F
Bank Sta=286.1,308.8
XS Rating Curve= 0 ,0
Exp/Cntr(USF)=0,0
Exp/Cntr=0.3,0.1

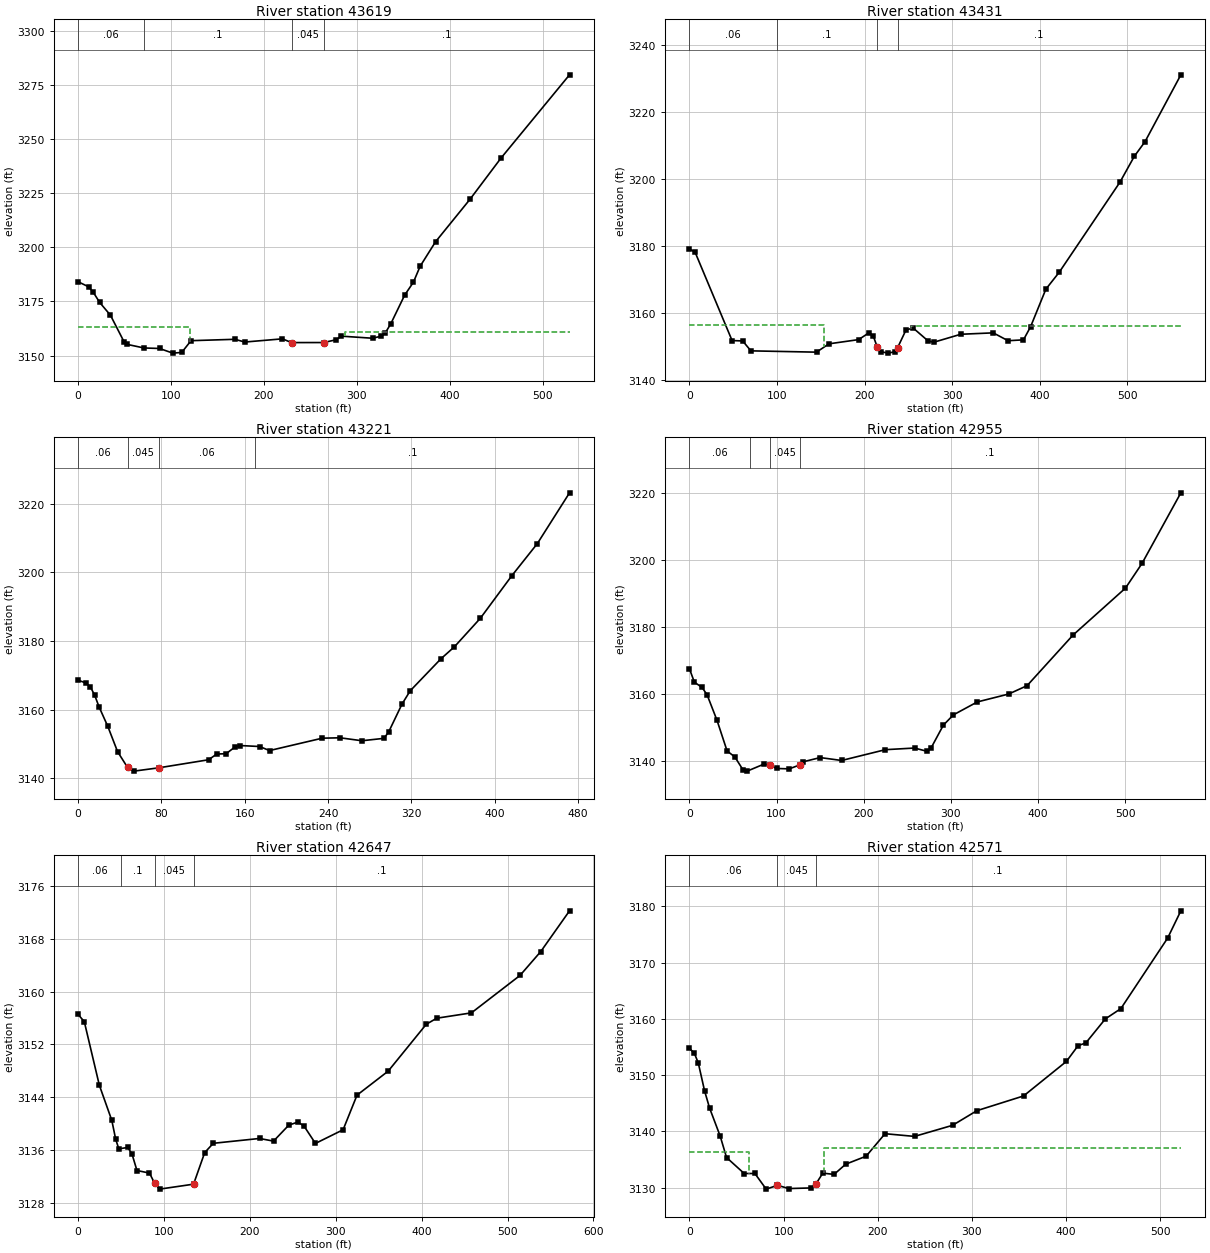
Type RM Length L Ch R = 1 ,43619   ,173.8,188.1,202.8
XS GIS Cut Line= 3
     2330006.907      524111.785     2329827.854       524386.45
     2329774.833      524580.279
#Sta/Elev= 30
       0  3184.1    11.2 3181.78      16 3179.44    23.2 3174.54    34.8 3168.63
    49.4 3156.39    52.1 3155.22    70.9  3153.5    87.6 3153.27   101.9 3151.12
   111.5 3151.44   121.5 3156.87   168.8 3157.51   179.3 3156.24   219.8 3157.72
   229.73155.989   264.3 3156.01   277.6  3157.3   283.3 3158.96   316.8    3158
   326.4 3158.98   330.7  3160.6   336.3 3164.53   351.4 3177.92   360.8 3183.88
     368 3191.21   384.6 3202.55   421.9  3222.3   455.1 3241.25   528.8 3279.69
#Mann= 4 ,-1,0
       0     .06       0    70.9      .1       0   229.7    .045       0
   264.3      .1       0
#XS Ineff= 2 , 0
          120.27 3162.99  287.29         3160.92
Permanent Ineff=
       F       F
Bank Sta=229.7,264.3
XS Rating Curve= 0 ,0
Exp/Cntr=0.3,0.1

Type RM Length L Ch R = 1 ,43431   ,235.9,209.9,189.8
XS GIS Cut Line= 4
     2329876.529       524052.68     2329739.197      524207.396
      2329585.35      524250.856     2329546.236      524441.209
#Sta/Elev= 30
       0 3179.06     6.6 3177.98    48.7 3151.65    60.8 3151.53    70.2 3148.57
   145.1 3148.18   159.3 3150.67   193.2 3151.93   205.4 3154.04     210 3152.93
   214.5 3149.68   218.3 3148.33     227 3147.89     235 3148.33   237.6 3149.46
   247.4 3154.89   255.7 3155.34   272.3 3151.58   278.8 3151.13   309.8 3153.53
   346.9 3153.95   363.8  3151.6   381.4 3151.86   389.5 3155.76     407 3167.02
   422.2 3172.06   491.6 3199.01     508 3206.74   520.2 3211.11   561.1 3231.09
#Mann= 4 ,-1,0
       0     .06       0     100      .1       0   214.5    .045       0
   237.6      .1       0
#XS Ineff= 2 , 0
          153.26 3156.24  252.92         3156.05
Permanent Ineff=
       F       F
Bank Sta=214.5,237.6
XS Rating Curve= 0 ,0
Exp/Cntr=0.3,0.1

Type RM Length L Ch R = 1 ,43221   ,259,266.3,273.9
XS GIS Cut Line= 2
     2329640.978      523970.107     2329494.085       524418.61
#Sta/Elev= 30
       0 3168.62     7.4 3167.82    11.7 3166.71    15.9 3164.25    20.1 3160.86
    28.5 3155.17    37.9  3147.8    47.5 3143.19    53.7 3142.13    77.8 3143.11
   125.3 3145.44   133.1 3147.11   142.1  3147.2   150.5 3149.13   155.3 3149.59
   174.3  3149.3   183.8 3148.12   234.5 3151.73   251.6 3151.84   272.5 3150.98
   293.7 3151.68   298.2 3153.53     311 3161.64   318.9 3165.53   348.4 3174.85
   361.4 3178.36   386.3 3186.67   416.6  3199.1     441 3208.42   471.9  3223.2
#Mann= 4 ,-1,0
       0     .06       0    47.5    .045       0    77.8     .06       0
     170      .1       0
Bank Sta=47.5,77.8
XS Rating Curve= 0 ,0
Exp/Cntr=0.3,0.1

Type RM Length L Ch R = 1 ,42955   ,308.5,307.5,304.9
XS GIS Cut Line= 3
     2329424.549      523873.627     2329210.729      524196.966
     2329201.167      524373.412
#Sta/Elev= 30
       0 3167.58     5.7 3163.56    14.4 3162.02    20.2 3159.84    31.7 3152.14
    43.2 3143.03    52.2 3141.21    61.8 3137.24    66.3 3136.99    85.8 3139.12
    92.3 3138.69   100.2 3137.78   114.6 3137.67   126.43138.824   129.8 3139.73
   150.1 3141.04   174.7 3140.17   224.9  3143.4   258.4 3143.89   272.8 3142.91
   277.1 3143.77   291.5 3150.73     303  3153.8   330.4 3157.66   366.5 3160.03
   387.6 3162.53   440.2 3177.61   500.5 3191.67   519.5 3199.04   564.1 3220.15
#Mann= 4 ,-1,0
       0     .06       0      70      .1       0    92.3    .045       0
   126.4      .1       0
Bank Sta=92.3,126.4
XS Rating Curve= 0 ,0
Exp/Cntr=0.3,0.1

Type RM Length L Ch R = 1 ,42647   ,68.7,75.9,80.7
XS GIS Cut Line= 3
     2329180.307      523695.443     2329070.789      523880.581
     2329118.594      524234.341
#Sta/Elev= 30
       0 3156.54     7.2 3155.45    24.7 3145.83    39.2 3140.51    43.8 3137.61
    47.4 3136.19    57.8  3136.4    62.7 3135.42    68.5 3132.91    83.1 3132.52
      89 3130.99    94.8 3130.09   134.4 3130.84   147.4 3135.63   157.4 3137.03
   211.2 3137.76   227.5 3137.36   245.3 3139.78     256 3140.25   263.1 3139.62
   276.3 3137.01   308.5 3139.08   324.7 3144.32     361 3147.96   405.3 3155.05
   417.5 3155.97   457.9 3156.78   514.4 3162.44   538.6 3166.06   572.1 3172.23
#Mann= 4 ,-1,0
       0     .06       0      50      .1       0      89    .045       0
   134.4      .1       0
Bank Sta=89,134.4
XS Rating Curve= 0 ,0
Exp/Cntr=0.3,0.1

Type RM Length L Ch R = 1 ,42571   ,325.5,327.4,327.9
XS GIS Cut Line= 3
     2329146.408      523657.199     2329002.992      523817.999
     2328706.598      523895.357
#Sta/Elev= 30
       0 3154.78     5.3 3153.86     9.4 3152.18    16.1  3147.2    21.4 3144.16
    32.7 3139.15    39.4 3135.37    58.2 3132.52    69.5 3132.53    81.5 3129.75
    93.5 3130.43   105.5 3129.85   128.6 3129.96     134 3130.59   141.6 3132.59
   153.6 3132.37   165.9 3134.18   187.6  3135.6   207.7  3139.6     239 3139.12
   279.4 3141.09   305.2 3143.69   354.8 3146.31   400.3 3152.45   412.7 3155.25
   420.9 3155.73   441.6    3160   458.1 3161.83   507.8 3174.37   521.8 3179.21
#Mann= 3 ,-1,0
       0     .06       0    93.5    .045       0     134      .1       0
#XS Ineff= 2 , 0
           63.23 3136.38  142.96         3137.05
Permanent Ineff=
       F       F
Bank Sta=93.5,134
XS Rating Curve= 0 ,0
Exp/Cntr=0.3,0.1