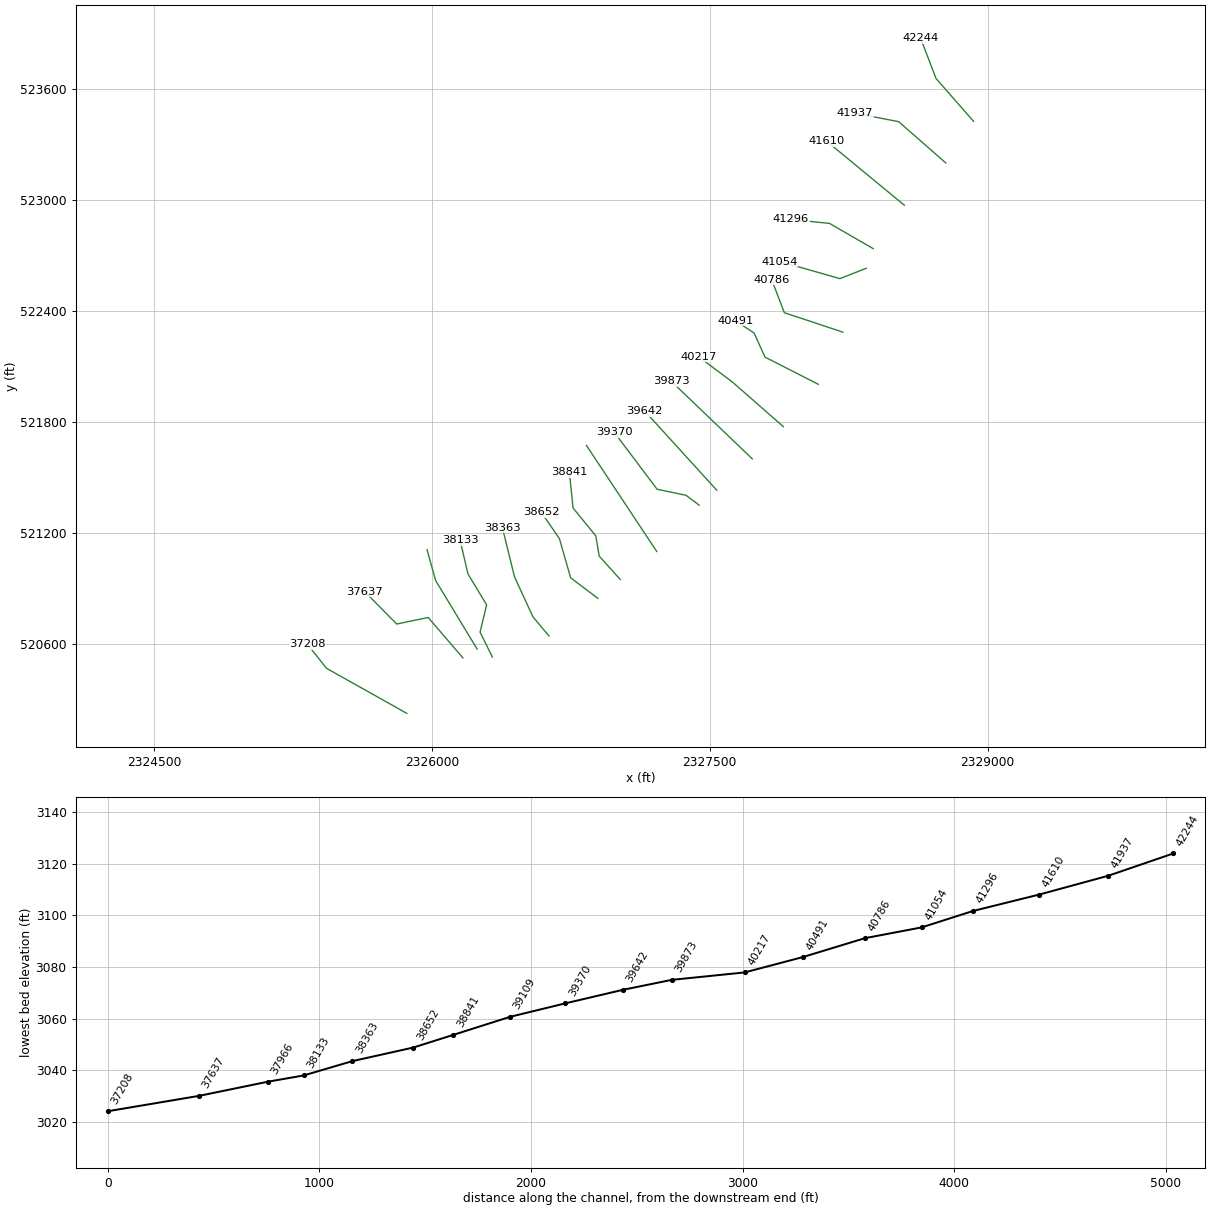
HEC-RAS study NRTHFRK.prj: NRTHFRK

--- NRTHFRK.g01 (geometry) --- (continued)

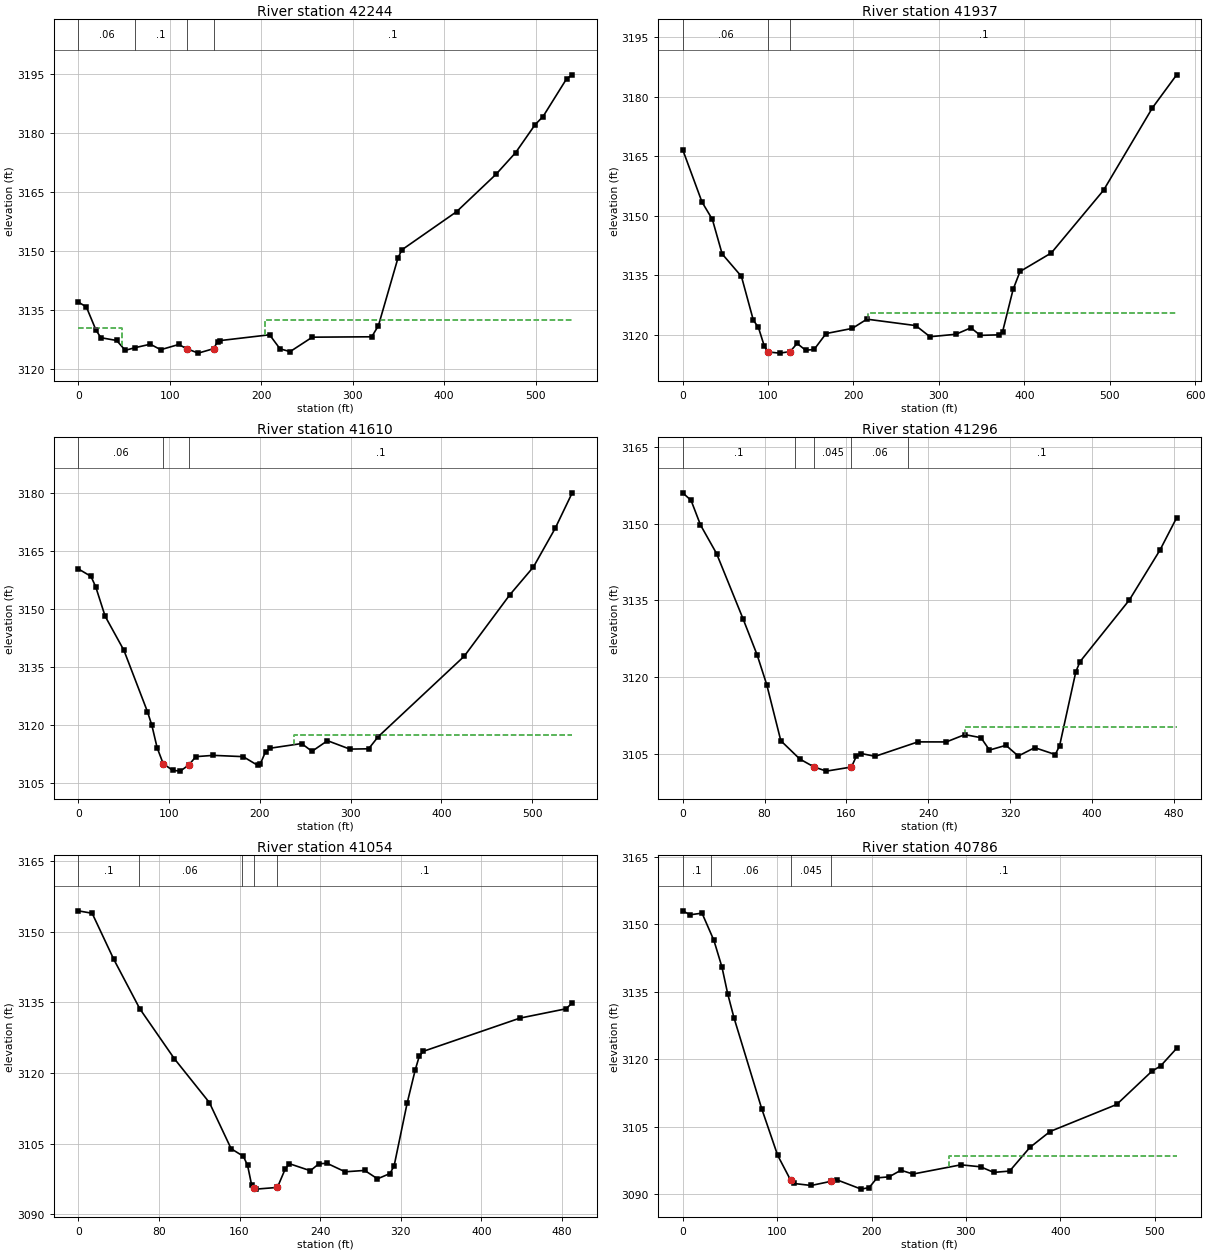
Type RM Length L Ch R = 1 ,42244   ,302.3,307.2,309.9
XS GIS Cut Line= 3
     2328924.765      523422.517     2328722.243      523653.722
     2328638.801       523871.02
#Sta/Elev= 30
       0 3136.98     8.9  3135.7    19.5 3129.77    24.8 3127.88      42 3127.18
    51.4 3124.67    61.6 3125.32    78.8 3126.23    90.2 3124.83   109.9 3126.16
   118.5  3125.1   131.2 3123.96   147.93125.085   152.4  3126.9   155.4 3127.16
   209.2 3128.63   220.6 3125.06   231.6 3124.34   255.9 3128.02   320.9 3128.12
   328.2 3130.95   349.6 3148.18   353.9 3150.26   413.6 3159.95   456.7 3169.46
   478.2 3174.99   499.6 3182.14   508.2 3184.18   533.9 3193.77   540.1  3194.8
#Mann= 4 ,-1,0
       0     .06       0    61.6      .1       0   118.5    .045       0
   147.9      .1       0
#XS Ineff= 2 , 0
           47.42 3130.33  204.12          3132.4
Permanent Ineff=
       F       F
Bank Sta=118.5,147.9
XS Rating Curve= 0 ,0
Exp/Cntr=0.3,0.1

Type RM Length L Ch R = 1 ,41937   ,325.7,326.8,327.2
XS GIS Cut Line= 3
     2328774.395      523198.266     2328520.591      523420.779
     2328284.171      523466.846
#Sta/Elev= 30
       0  3166.7    22.6 3153.47    34.8 3149.06    46.2 3140.37    68.8 3134.69
    82.7 3123.67    88.7  3121.8    95.4 3117.23     100 3115.62   113.6 3115.33
   125.8 3115.71     134 3117.77     144 3116.06   153.9 3116.25   167.9 3120.27
   198.6 3121.57   215.7  3123.9   272.9 3122.28   289.6 3119.47   319.9 3120.09
   337.5 3121.72   348.5 3119.81   370.6 3119.95   374.6 3120.74   386.9  3131.4
     395 3135.93   431.7 3140.62   492.8 3156.43   550.1 3177.25   578.4 3185.56
#Mann= 3 ,-1,0
       0     .06       0     100    .045       0   125.8      .1       0
#XS Ineff= 2 , 0
                          217.18          3125.5
Permanent Ineff=
       F       F
Bank Sta=100,125.8
XS Rating Curve= 0 ,0
Exp/Cntr=0.3,0.1

Type RM Length L Ch R = 1 ,41610   ,309.3,314.2,319.4
XS GIS Cut Line= 2
     2328551.013      522969.669     2328131.194      523315.607
#Sta/Elev= 30
       0 3160.39      14 3158.45    19.2 3155.77    29.6 3148.14    50.3  3139.3
    76.2 3123.43      81 3119.96    86.9 3114.07    93.6 3109.94     104 3108.24
   112.4 3108.03   122.1  3109.7   129.5 3111.78   148.8 3112.11   181.6 3111.78
   197.7 3109.52   200.6 3109.94   206.3 3113.07     211 3113.95     246 3115.17
   257.4 3113.16   274.5 3115.91   299.1 3113.73   319.8 3113.81   330.2 3116.91
   425.1 3137.78   475.3 3153.68   501.3 3160.88   525.2 3170.86     544 3180.07
#Mann= 3 ,-1,0
       0     .06       0    93.6    .045       0   122.1      .1       0
#XS Ineff= 2 , 0
                          237.11         3117.27
Permanent Ineff=
       F       F
Bank Sta=93.6,122.1
XS Rating Curve= 0 ,0
Exp/Cntr=0.3,0.1

Type RM Length L Ch R = 1 ,41296   ,235.4,241.9,248.3
XS GIS Cut Line= 3
     2328383.259      522734.987     2328146.839       522871.45
     2327938.233       522893.18
#Sta/Elev= 30
       0 3155.99     8.2 3154.52    17.4 3149.72    33.1 3144.14      59 3131.39
    72.8 3124.32    82.1 3118.56    95.9 3107.59   114.4 3104.02   128.3 3102.47
   140.4 3101.65   164.9 3102.45   169.8 3104.59   174.4 3105.09   188.1 3104.54
   229.9 3107.36   257.6 3107.35   275.7 3108.78   291.5 3108.18   299.8 3105.76
   315.9 3106.69   327.9  3104.6     344 3106.23   364.1 3104.89   368.3 3106.59
   384.2 3121.07   388.3 3123.03   436.5 3135.07   466.4 3144.81   482.7 3151.12
#Mann= 5 ,-1,0
       0      .1       0     110     .06       0   128.3    .045       0
   164.9     .06       0     220      .1       0
#XS Ineff= 2 , 0
                          275.49         3110.18
Permanent Ineff=
       F       F
Bank Sta=128.3,164.9
XS Rating Curve= 0 ,0
Exp/Cntr=0.3,0.1

Type RM Length L Ch R = 1 ,41054   ,269,268,267.1
XS GIS Cut Line= 3
     2328345.015      522628.946     2328203.336      522573.318
     2327878.259      522665.452
#Sta/Elev= 30
       0 3154.42    13.8  3153.9    35.3  3144.1    61.1 3133.61    95.4    3123
   130.1  3113.7   151.7 3103.89   163.8 3102.29     168 3100.37   172.1 3096.11
   174.4 3095.64   176.3 3095.31   197.6 3095.67   205.4 3099.61   209.5 3100.71
   230.3 3099.22   238.9 3100.72     247 3100.78   264.8 3098.99   284.2 3099.28
   296.9  3097.5   309.3 3098.62   313.4 3100.26   326.3 3113.55   334.3  3120.6
   338.4 3123.57   342.4 3124.58   438.2 3131.63   483.9 3133.61   490.1 3134.85
#Mann= 5 ,-1,0
       0      .1       0      60     .06       0   162.2      .1       0
   174.4    .045       0   197.6      .1       0
Bank Sta=174.4,197.6
XS Rating Curve= 0 ,0
Exp/Cntr=0.3,0.1

Type RM Length L Ch R = 1 ,40786   ,298.4,294.9,290.3
XS GIS Cut Line= 3
2328219.60800791522283.9682253252327903.22300791522389.141225325
2327835.42600791522566.455225325
#Sta/Elev= 30
       0 3152.97     7.8 3152.09    20.5 3152.45    33.1 3146.39    41.6 3140.48
    47.7 3134.53    54.3 3129.24    83.7 3109.02   100.6 3098.65   114.4 3093.11
   117.6  3092.4   136.1 3091.95   157.23092.878   163.8 3093.17   189.1 3091.14
   197.5 3091.48   205.9 3093.64   218.6 3093.87   231.2 3095.34   243.9 3094.49
   294.7 3096.54   315.5  3096.1   329.5 3094.86   346.3 3095.15   367.7 3100.39
   389.1 3103.94   459.7 3109.95   496.9 3117.32   506.2  3118.5   523.2 3122.42
#Mann= 4 ,-1,0
       0      .1       0      30     .06       0   114.4    .045       0
   157.2      .1       0
#XS Ineff= 2 , 0
                          282.47         3098.39
Permanent Ineff=
       F       F
Bank Sta=114.4,157.2
XS Rating Curve= 0 ,0
Exp/Cntr=0.3,0.1

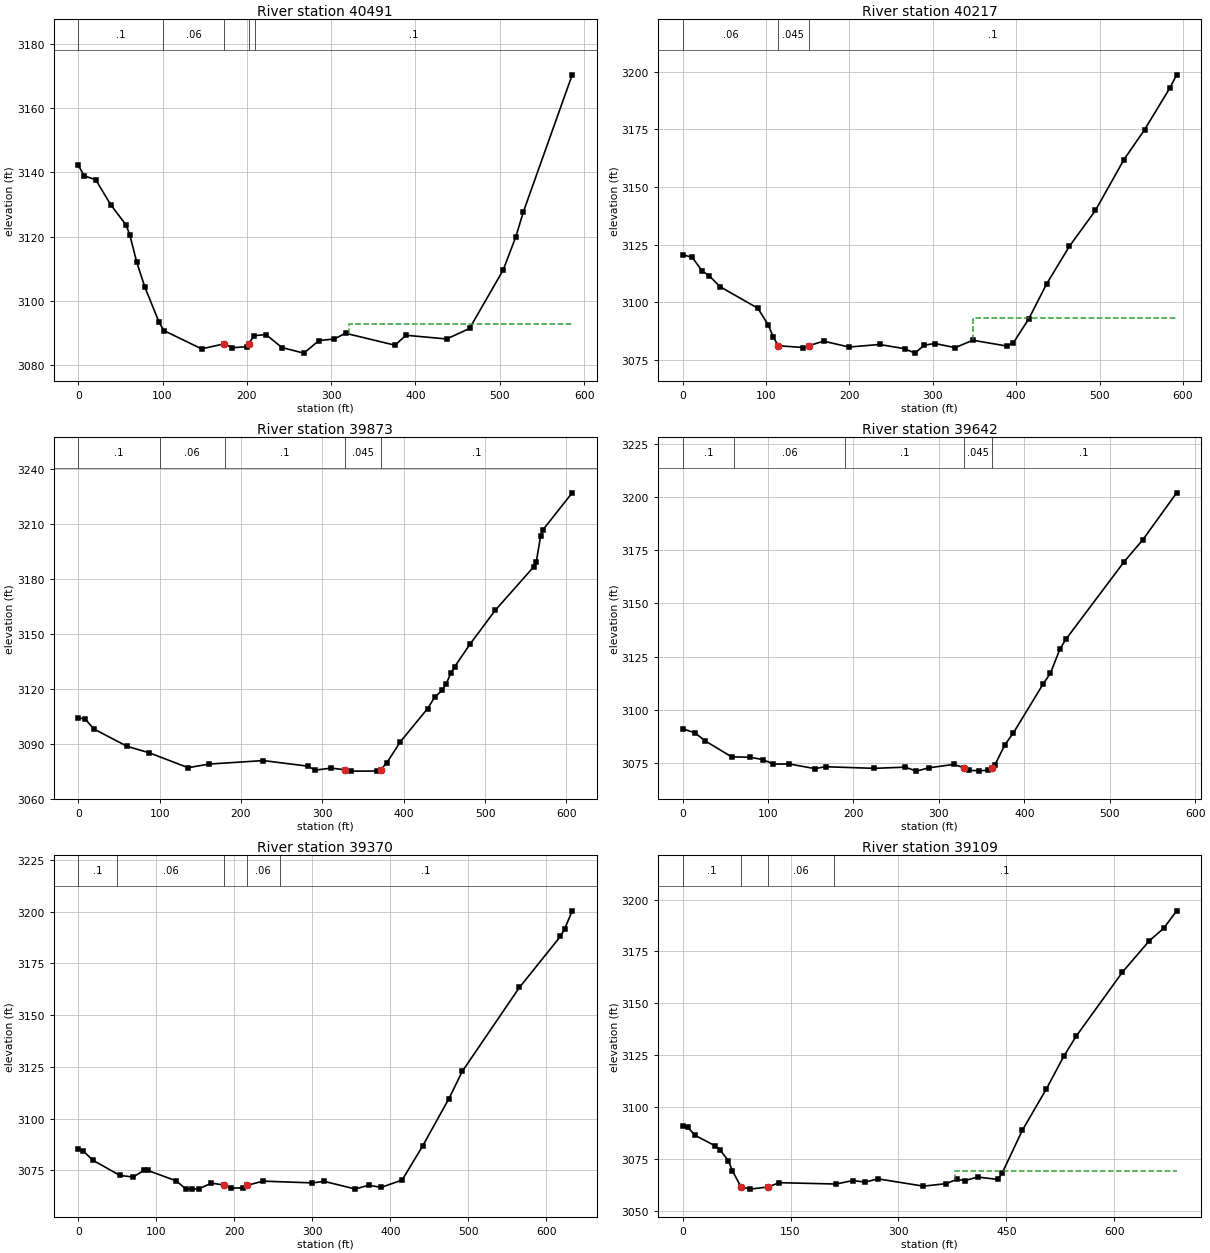
Type RM Length L Ch R = 1 ,40491   ,280.1,273.8,268.3
XS GIS Cut Line= 4
     2328086.575      522002.453     2327798.776      522149.249
     2327739.865      522279.628     2327639.425        522345.3
#Sta/Elev= 30
       0 3142.22     7.2  3138.9    20.7 3137.71    38.6  3129.9    56.6 3123.68
    61.1 3120.63    69.2 3112.24      79 3104.31      96 3093.32   101.5 3090.81
   146.4 3085.11   173.43086.701   182.6 3085.47   199.7 3085.78   202.13086.761
     209 3089.24   222.7 3089.55   241.7 3085.51   267.6 3083.79   285.6 3087.71
   303.5 3088.17     317 3089.97   375.7 3086.25   388.8 3089.35   436.9 3088.19
   464.1 3091.45     504 3109.63   519.1 3120.02   527.9 3127.67   585.9 3170.32
#Mann= 5 ,-1,0
       0      .1       0     100     .06       0   173.4    .045       0
   202.1     .06       0     210      .1       0
#XS Ineff= 2 , 0
                          320.96         3092.92
Permanent Ineff=
       F       F
Bank Sta=173.4,202.1
XS Rating Curve= 0 ,0
Exp/Cntr=0.3,0.1

Type RM Length L Ch R = 1 ,40217   ,334.5,344.3,342.1
XS GIS Cut Line= 3
2327897.73837861521773.716621956 2327625.1755921522012.722995963
2327441.38324448522150.818487825
#Sta/Elev= 30
       0 3120.53    11.3 3119.55    23.4 3113.53    31.9 3111.44    44.6 3106.76
    90.2 3097.35   102.8 3089.96   108.4 3085.06   114.5 3081.08   144.8 3080.31
   150.9 3081.08   169.1 3083.07   199.4 3080.52   236.2 3081.62   266.1  3079.8
   278.5 3077.87   289.8 3081.33   302.5 3082.05   326.8 3080.25   347.9 3083.46
   388.8 3080.95   396.6 3082.37     415 3092.72   436.5 3107.95   463.8 3124.26
     495 3139.83   529.2 3161.91   553.9 3174.87   583.9 3192.79   592.4 3198.72
#Mann= 3 ,-1,0
       0     .06       0   114.5    .045       0   150.9      .1       0
#XS Ineff= 2 , 0
                          347.91         3093.15
Permanent Ineff=
       F       F
Bank Sta=114.5,150.9
XS Rating Curve= 0 ,0
Exp/Cntr=0.3,0.1

Type RM Length L Ch R = 1 ,39873   ,234.4,231.5,229.8
XS GIS Cut Line= 2
     2327730.207      521599.728     2327291.749      522019.836
#Sta/Elev= 30
       0 3104.09     8.4 3103.46    19.4 3097.97    59.9 3088.56    87.3 3084.99
   135.1 3076.88   160.9 3078.86   227.6 3080.75   282.5  3077.7   291.2 3075.53
   310.8 3076.65   327.8 3075.74   335.2    3075   367.4 3075.05     372 3075.88
   379.5 3079.68   396.1 3091.09   429.4 3109.13   438.1 3115.29   447.3 3119.12
   452.3 3122.65   457.9  3128.4   462.6 3131.95     482 3144.56   512.5 3162.75
   559.8 3186.48   562.9 3188.88   568.3 3203.16   571.1 3206.65   607.2  3226.9
#Mann= 5 ,-1,0
       0      .1       0     100     .06       0     180      .1       0
   327.8    .045       0     372      .1       0
Bank Sta=327.8,372
XS Rating Curve= 0 ,0
Exp/Cntr=0.3,0.1

Type RM Length L Ch R = 1 ,39642   ,255.8,271.7,288.9
XS GIS Cut Line= 2
     2327538.019      521430.718     2327148.815      521858.553
#Sta/Elev= 30
       0 3090.98    14.4 3089.15    25.7 3085.49    57.4 3077.83      79 3077.66
    93.7 3076.56   106.1 3074.44   124.8 3074.49   154.7 3072.31   167.3  3073.2
   223.9 3072.44   260.7 3072.99   273.7 3071.13   288.1 3072.69   317.4 3074.27
   329.7  3072.7   335.6 3071.51   347.5 3071.28     357 3071.54   361.9 3072.55
   365.3 3073.84   377.2 3083.43   387.3 3089.15   422.1 3112.09   430.5 3117.09
   441.9 3128.64   448.6 3133.04     517  3169.6   538.7 3179.82   578.4 3201.94
#Mann= 5 ,-1,0
       0      .1       0      60     .06       0     190      .1       0
   329.7    .045       0   361.9      .1       0
Bank Sta=329.7,361.9
XS Rating Curve= 0 ,0
Exp/Cntr=0.3,0.1

Type RM Length L Ch R = 1 ,39370   ,288,261.2,245.3
XS GIS Cut Line= 4
     2327443.374      521349.594     2327372.873      521402.711
2327216.47397458521435.4911258482326984.93928505 521743.21657841
#Sta/Elev= 30
       0 3085.08       6  3084.4    19.1  3079.8    53.4 3072.51    70.5 3071.75
    84.1 3074.98      89 3074.96   125.8 3069.86     138 3065.93   146.2  3065.9
   155.1 3066.08   170.7  3068.8   187.1 3067.87   195.7 3066.37   211.6 3066.52
     216 3067.68   236.8 3069.76   300.2 3068.91   315.3 3069.65     355 3065.96
   372.3 3067.78   388.3 3066.74   415.2  3070.3   441.5 3086.77   475.2 3109.65
   492.3 3122.81   565.5 3163.33     618 3187.96   623.7 3191.78   633.2 3200.36
#Mann= 5 ,-1,0
       0      .1       0      50     .06       0   187.1    .045       0
     216     .06       0  258.07      .1       0
Bank Sta=187.1,216
XS Rating Curve= 0 ,0
Exp/Cntr=0.3,0.1

Type RM Length L Ch R = 1 ,39109   ,283.3,268,259.6
XS GIS Cut Line= 2
     2327214.487       521099.46      2326834.94       521672.16
#Sta/Elev= 30
       0 3090.97     6.9 3090.48    17.3 3086.56    45.3 3081.47      52 3079.44
    63.5 3074.42    69.2 3069.46    80.8 3061.92    93.2 3060.68   118.2 3061.68
   134.5 3063.78   213.2 3063.14   236.7 3064.79     254 3064.04   271.3 3065.63
   334.8 3062.11   366.8 3063.33     381  3065.4   392.5 3064.76     410  3066.5
   438.6 3065.33   444.5 3068.57   472.3 3088.96   505.9 3108.97   529.9 3124.57
   547.2 3134.24   611.5 3165.06   648.6 3180.04   669.1 3186.24   686.9 3194.56
#Mann= 4 ,-1,0
       0      .1       0    80.8    .045       0   118.2     .06       0
     210      .1       0
#XS Ineff= 2 , 0
                          379.27          3069.3
Permanent Ineff=
       F       F
Bank Sta=80.8,118.2
XS Rating Curve= 0 ,0
Exp/Cntr=0.3,0.1

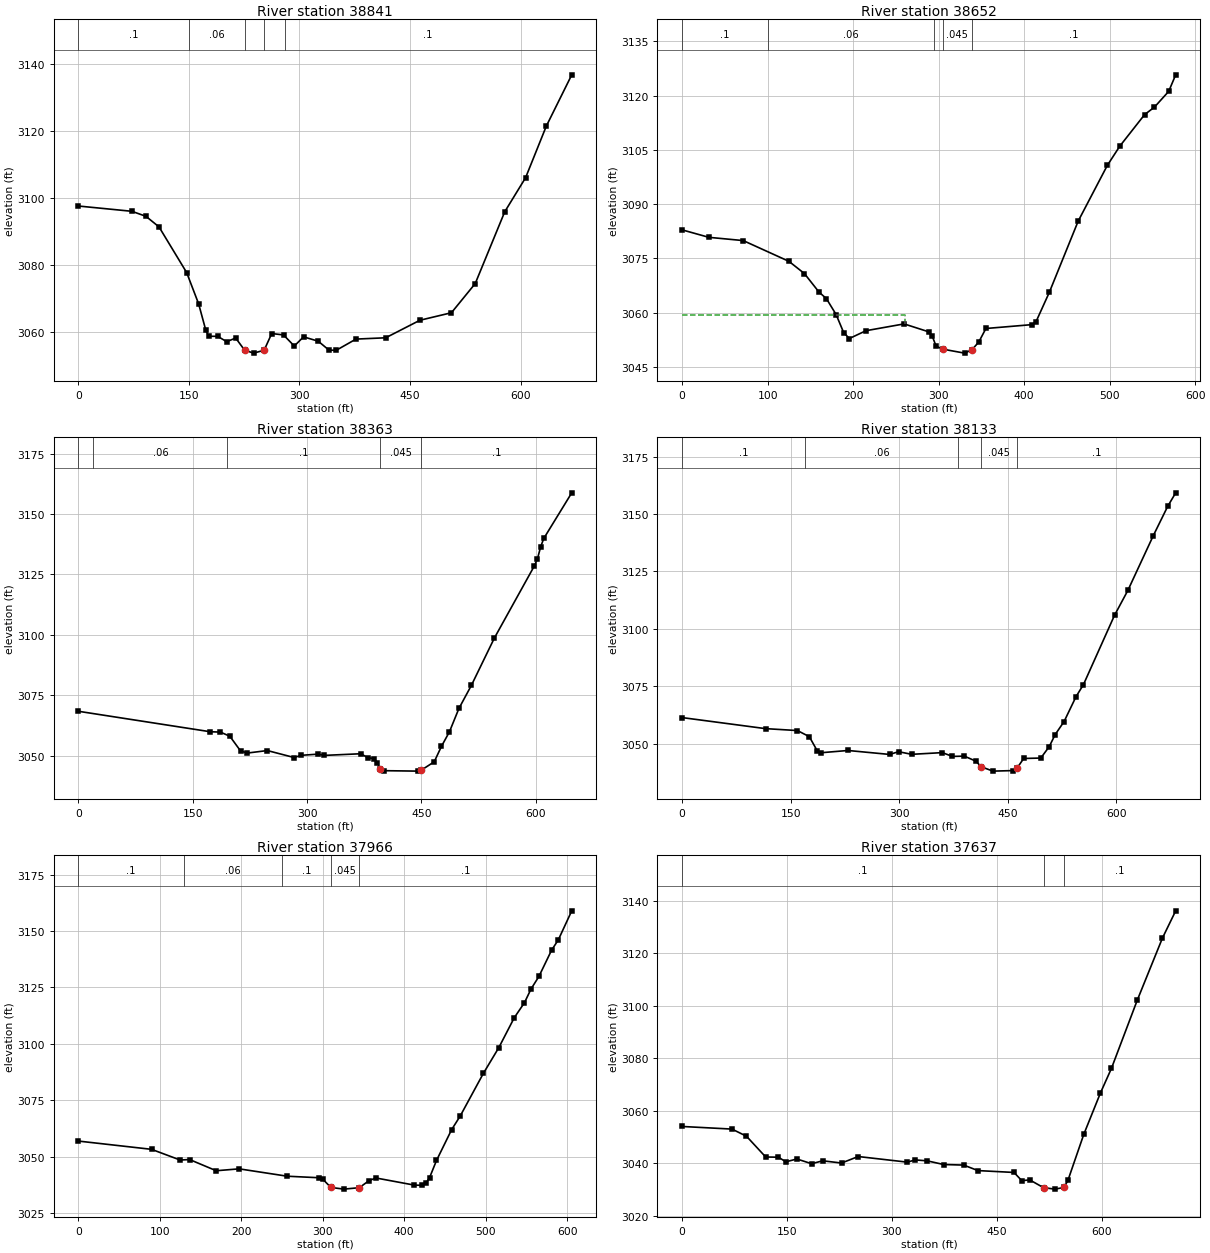
Type RM Length L Ch R = 1 ,38841   ,184.8,188.8,191.2
XS GIS Cut Line= 5
2327017.65841622520947.901532617 2326903.9675392521074.096055861
2326885.17483444521184.2287105092326762.77858014521334.129791599
  2326742.743094521527.515788221
#Sta/Elev= 30
       0 3097.62    72.8 3096.04    91.9 3094.54   109.6 3091.38   147.1 3077.75
   163.4 3068.38     173 3060.58     177 3058.73   189.2 3058.72   201.4 3057.11
   213.6 3058.21   225.7 3054.59   237.9  3053.7   252.2 3054.56   262.5 3059.55
   278.5 3059.13   293.1 3055.82   305.7 3058.56   325.6 3057.26   340.1 3054.61
   349.9 3054.53   376.8 3057.89   417.1 3058.28   463.5 3063.51   506.3 3065.76
   538.6 3074.48   578.6  3095.9   606.9 3106.08     635 3121.47   669.5 3136.78
#Mann= 5 ,-1,0
       0      .1       0     150     .06       0   225.7    .045       0
   252.2     .06       0  279.85      .1       0
Bank Sta=225.7,252.2
XS Rating Curve= 0 ,0
Exp/Cntr(USF)=0,0
Exp/Cntr=0.3,0.1

Type RM Length L Ch R = 1 ,38652   ,289.9,288.5,287.4
XS GIS Cut Line= 4
     2326897.098      520845.863     2326749.595      520957.359
      2326689.11      521168.995     2326591.567      521310.963
#Sta/Elev= 30
       0 3082.88    31.2 3080.82    71.4 3079.92   124.9 3074.18     143  3070.8
   160.1 3065.67   168.7 3063.88   180.1 3059.46   188.9 3054.49   195.6 3052.84
     215    3055   259.6 3056.88   288.7 3054.67   292.7  3053.4     297 3050.74
   304.6 3049.91   330.3  3048.8   338.8 3049.68     347 3051.89   355.3 3055.61
   408.7 3056.67   413.7 3057.37   429.5 3065.62   463.2 3085.28   497.4 3100.74
     512 3106.05   540.9 3114.74   552.5 3116.83   569.1 3121.17   577.3 3125.75
#Mann= 5 ,-1,0
       0      .1       0     100     .06       0   294.9      .1       0
   304.6    .045       0   338.8      .1       0
#XS Ineff= 2 , 0
          261.17 3059.37
Permanent Ineff=
       F       F
Bank Sta=304.6,338.8
XS Rating Curve= 0 ,0
Exp/Cntr=0.3,0.1

Type RM Length L Ch R = 1 ,38363   ,217.1,230,238.9
XS GIS Cut Line= 4
     2326632.841      520642.997     2326546.016      520746.854
     2326446.702      520962.321      2326381.03      521228.873
#Sta/Elev= 30
       0 3068.33   173.2 3059.84   186.4  3059.7   198.8 3057.98   212.8 3051.92
   221.6 3051.01     248 3052.05   283.1 3049.16   292.1 3050.07   314.1 3050.56
   322.9 3050.05   370.7 3050.73   379.7 3049.06   387.9 3048.76     392  3047.1
   396.1 3044.34   400.3 3043.72   445.6 3043.53     450 3043.97   466.8  3047.4
   476.2 3053.75   486.8 3059.87   499.2 3069.51   515.6 3079.11   545.6 3098.62
     598 3128.49   602.1 3131.41   606.3 3136.42   610.4 3139.89   647.1  3158.8
#Mann= 5 ,-1,0
       0      .1       0      20     .06       0   195.4      .1       0
   396.1    .045       0     450      .1       0
Bank Sta=396.1,450
XS Rating Curve= 0 ,0
Exp/Cntr=0.3,0.1

Type RM Length L Ch R = 1 ,38133   ,169,167.8,167.8
XS GIS Cut Line= 5
     2326326.981      520529.526     2326260.727      520663.761
     2326296.152      520811.351     2326195.602      520977.773
     2326153.109      521159.338
#Sta/Elev= 30
       0 3061.31   115.3  3056.5   159.4 3055.66   175.8 3053.01   186.9 3046.76
   192.3 3046.01   229.3 3046.98   286.9 3045.26   299.2 3046.45   317.4 3045.31
   359.7 3046.05   373.7  3044.4   390.2 3044.52   406.4 3042.29   413.3  3039.9
   429.8 3037.99   457.8 3038.23   463.3 3039.41   472.2  3043.5   495.9 3043.69
   507.6 3048.69   515.8 3053.94   528.1  3059.6   544.6 3070.43   554.9 3075.71
   597.8 3105.85   616.3 3116.73   651.4 3140.54   671.4 3153.35   682.4 3159.21
#Mann= 5 ,-1,0
       0      .1       0   169.7     .06       0   381.5      .1       0
   413.3    .045       0   463.3      .1       0
Bank Sta=413.3,463.3
XS Rating Curve= 0 ,0
Exp/Cntr=0.3,0.1

Type RM Length L Ch R = 1 ,37966   ,325.5,328.4,335.3
XS GIS Cut Line= 3
     2326244.857      520572.151     2326020.798      520943.006
     2325974.442      521109.118
#Sta/Elev= 30
       0 3056.89      90 3053.22   125.1 3048.48   136.7 3048.69   169.4 3043.73
   197.5 3044.57   256.6  3041.3   295.3 3040.63   300.3 3039.93   310.1 3036.32
   326.2 3035.58     345 3036.22   357.1 3039.39   365.4 3040.52   412.5 3037.36
   421.8 3037.27   426.5 3038.08   431.2 3040.67   439.7 3048.27   458.3 3061.96
   468.8 3067.98   497.2 3086.87   516.2 3098.31   535.2 3111.59   547.7 3118.24
   555.7 3124.28   565.4 3129.85   580.9 3141.46   589.2 3146.07   605.7 3158.94
#Mann= 5 ,-1,0
       0      .1       0     130     .06       0     250      .1       0
   310.1    .045       0     345      .1       0
Bank Sta=310.1,345
XS Rating Curve= 0 ,0
Exp/Cntr=0.3,0.1

Type RM Length L Ch R = 1 ,37637   ,421.6,429.8,438.7
XS GIS Cut Line= 4
2326168.09548707520524.6066944052325980.87520884 520742.91597159
2325810.82619802520707.636093828     2325638.891      520881.733
#Sta/Elev= 30
       0 3053.95    71.3 3052.95      92 3050.23   119.5 3042.31   137.8 3042.23
   148.3 3040.47   164.1 3041.55   185.2 3039.75     201 3040.86     228 3040.01
   251.8 3042.49   322.3 3040.34   333.2 3041.21   350.6 3040.84   374.1 3039.44
   402.7 3039.23   423.1 3037.13   474.7 3036.42   485.9 3033.28   497.2 3033.58
   516.93030.629   533.3 3030.06   546.23030.702   551.9 3033.44   574.5 3050.93
   598.4 3066.76   614.1  3076.1   650.9 3102.01     687 3125.76     706 3136.17
#Mann= 3 ,-1,0
       0      .1       0   516.9    .045       0   546.2      .1       0
#XS Ineff= 2 , 0
          359.22 3039.48
Permanent Ineff=
       F       F
Bank Sta=516.9,546.2
XS Rating Curve= 0 ,0
Exp/Cntr=0.3,0.1

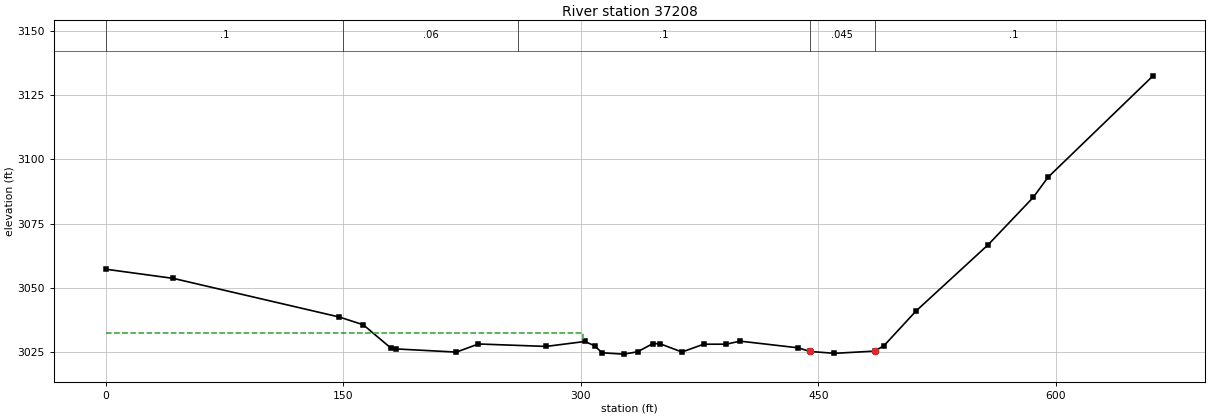
Type RM Length L Ch R = 1 ,37208   ,334.8,334.3,333.2
XS GIS Cut Line= 3
      2325865.31      520225.011     2325431.788      520468.599
     2325329.845      520597.368
#Sta/Elev= 30
       0  3057.2    42.6 3053.62   147.3  3038.6   162.5 3035.57     180 3026.48
   183.1 3026.16   221.3 3024.92   235.3 3028.08     278 3027.13   302.5 3029.05
   308.7 3027.36   313.3 3024.65     327 3024.13   335.8 3025.04   345.4 3028.24
     350 3028.16   363.8 3024.95   377.5 3027.99   391.7    3028   400.5 3029.19
   437.2 3026.58   444.63025.177   460.1 3024.44   485.6 3025.31   491.5 3027.49
   511.6 3040.92   557.2 3066.76   585.7 3085.22   594.9 3092.97   661.3 3132.52
#Mann= 5 ,-1,0
       0      .1       0     150     .06       0     260      .1       0
   444.6    .045       0   485.6      .1       0
#XS Ineff= 2 , 0
          301.49  3032.4
Permanent Ineff=
       F       F
Bank Sta=444.6,485.6
XS Rating Curve= 0 ,0
Exp/Cntr=0.3,0.1