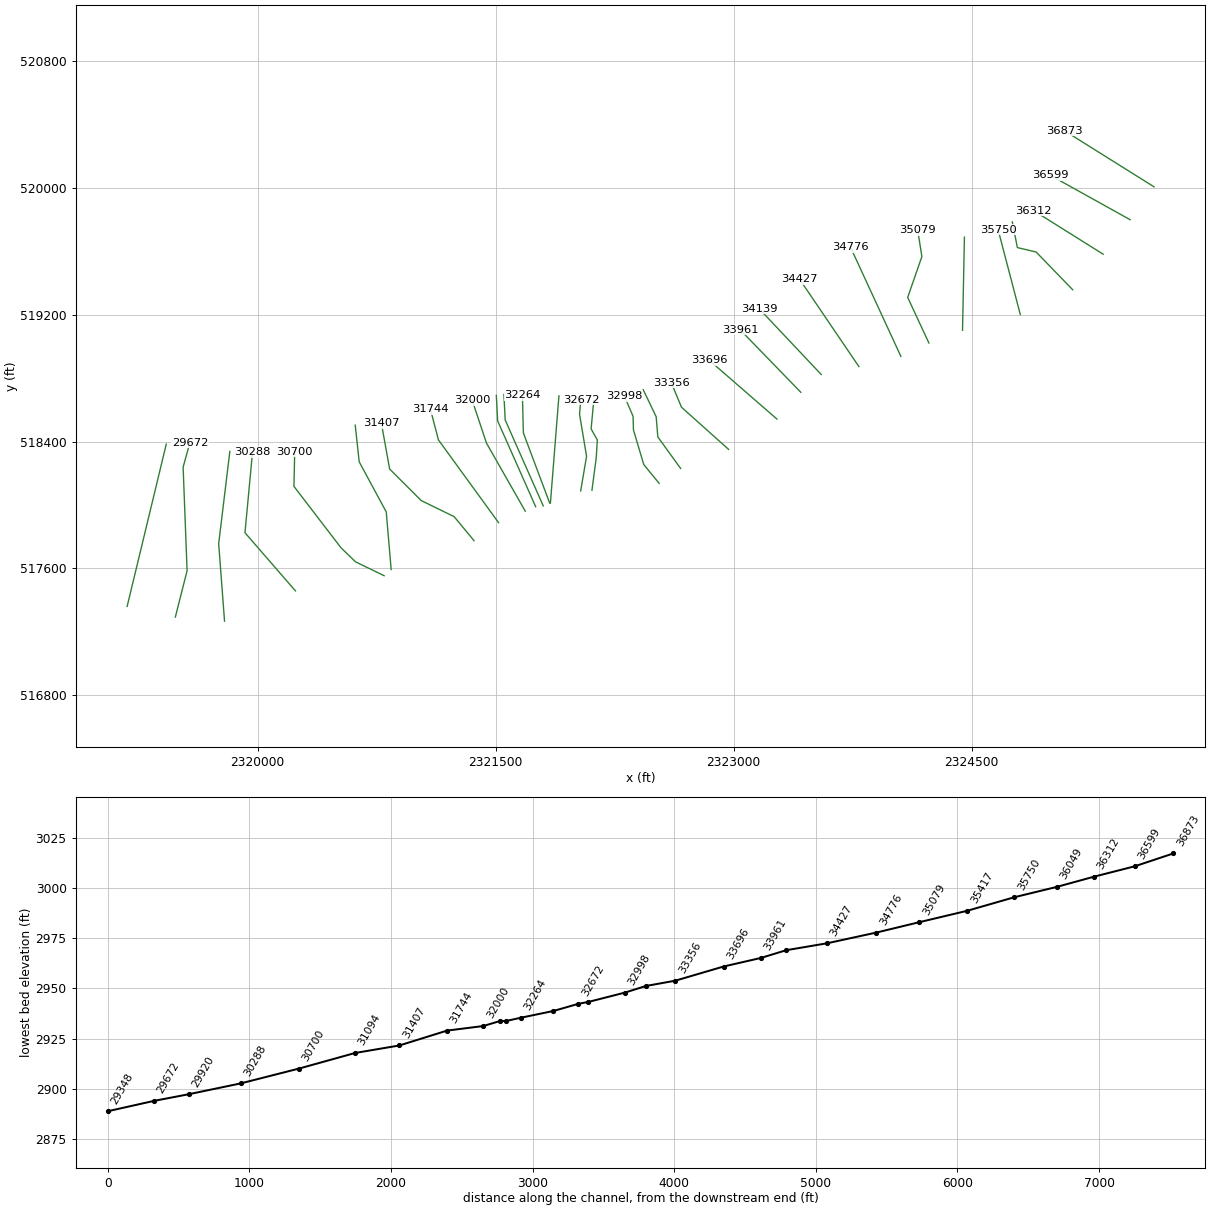
HEC-RAS study NRTHFRK.prj: NRTHFRK

--- NRTHFRK.g01 (geometry) --- (continued)

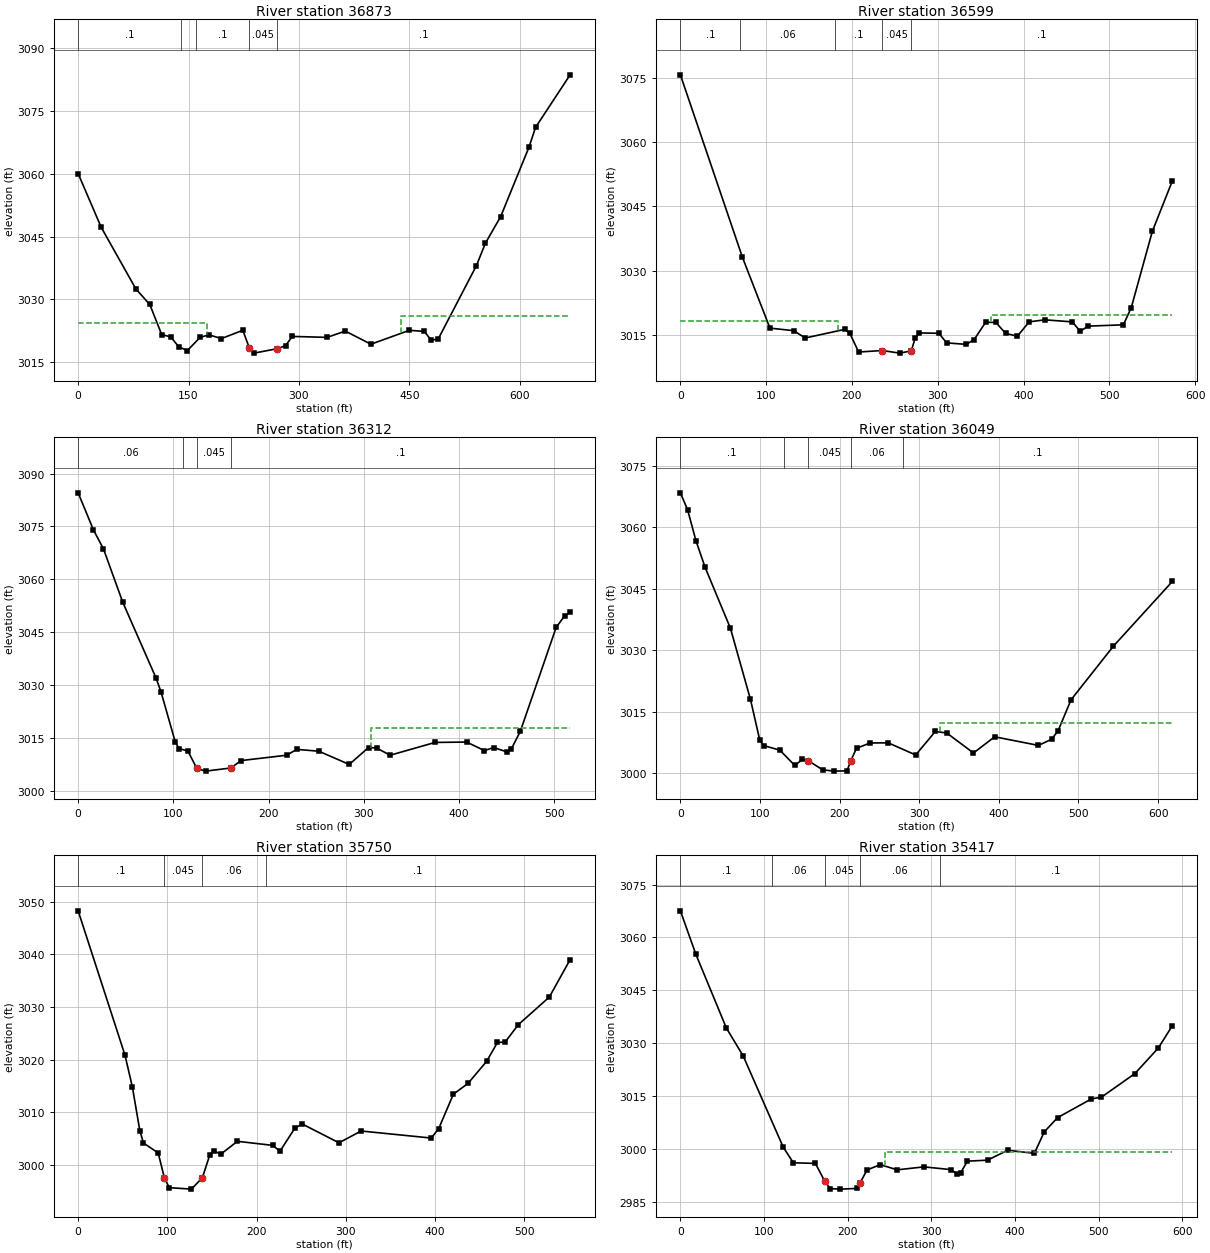
Type RM Length L Ch R = 1 ,36873   ,271,273.9,274.1
XS GIS Cut Line= 2
     2325650.695      520007.177     2325084.111      520362.365
#Sta/Elev= 30
       0 3060.02    31.3 3047.21    78.5 3032.47    97.4 3028.77   113.6 3021.56
   125.7 3021.06   136.8 3018.66   148.4 3017.77   165.8 3020.92   177.7 3021.52
   194.8 3020.64   223.8 3022.61   232.5 3018.46     239 3017.16   270.9 3018.23
   281.9 3018.94     291 3021.15   338.2 3020.92   363.1 3022.42   397.9 3019.29
   450.2 3022.61   470.4 3022.34   479.8 3020.27   489.2 3020.49   541.2 3038.03
   553.5 3043.42   574.2 3049.75   612.7 3066.33   621.6 3071.05   668.6  3083.6
#Mann= 5 ,-1,0
       0      .1       0     140     .06       0     160      .1       0
   232.5    .045       0   270.9      .1       0
#XS Ineff= 2 , 0
           174.8 3024.32   438.6         3025.94
Permanent Ineff=
       F       F
Bank Sta=232.5,270.9
XS Rating Curve= 0 ,0
Exp/Cntr=0.3,0.1

Type RM Length L Ch R = 1 ,36599   ,283.6,287,282.1
XS GIS Cut Line= 2
     2325499.391      519800.073     2324998.265      520079.073
#Sta/Elev= 30
       0 3075.76    72.4 3033.09   104.4 3016.58   131.9 3015.99   145.6 3014.28
   191.4 3016.28   197.3 3015.45   207.8    3011   235.5 3011.35   255.5 3010.74
   269.2 3011.26   273.6 3014.22   278.4 3015.46   301.3 3015.38   310.4 3013.13
   333.3 3012.79   342.5 3013.92   355.9 3017.97   367.8  3017.9   379.1 3015.35
   392.8  3014.7   406.6 3018.05   424.9 3018.52   456.9 3018.04   466.1 3015.84
   475.2 3017.05   516.4 3017.35   525.6 3021.38   550.2 3039.22   573.5 3050.99
#Mann= 5 ,-1,0
       0      .1       0      70     .06       0     180      .1       0
   235.5    .045       0   269.2      .1       0
#XS Ineff= 2 , 0
          184.19 3018.14  361.51         3019.69
Permanent Ineff=
       F       F
Bank Sta=235.5,269.2
XS Rating Curve= 0 ,0
Exp/Cntr=0.3,0.1

Type RM Length L Ch R = 1 ,36312   ,268,262.8,256.8
XS GIS Cut Line= 2
     2325329.845      519582.239     2324892.031      519856.946
#Sta/Elev= 30
       0 3084.55    16.1 3074.01    26.6 3068.65    46.9 3053.49    81.7  3032.1
      87 3028.14     102 3013.89   105.9 3012.01   115.3 3011.29   124.7 3006.36
   133.9 3005.59   160.6 3006.49   171.1 3008.58   219.2 3010.11   229.7 3011.76
   252.9 3011.24   284.8 3007.49   305.1 3012.29   313.6 3012.15   327.8  3010.1
     375 3013.73   408.1 3013.84   426.9 3011.41   436.4 3012.28   450.6 3011.05
   455.3 3011.96   464.6  3016.9   502.2 3046.35   511.1 3049.63   516.9 3050.68
#Mann= 4 ,-1,0
       0     .06       0     110      .1       0   124.7    .045       0
   160.6      .1       0
#XS Ineff= 2 , 0
                           307.9          3017.9
Permanent Ineff=
       F       F
Bank Sta=124.7,160.6
XS Rating Curve= 0 ,0
Exp/Cntr=0.3,0.1

Type RM Length L Ch R = 1 ,36049   ,316,300,282.9
XS GIS Cut Line= 4
     2325137.765      519357.967     2324907.054      519596.189
     2324789.016      519624.089     2324756.823      519786.123
#Sta/Elev= 30
       0 3068.35     9.1 3064.21    19.5  3056.7      31 3050.21    62.8 3035.37
      88    3018    99.6 3008.15   104.7 3006.74     125 3005.61   143.7 3001.89
   153.3 3003.38   160.53003.051   178.8 3000.82   192.9 3000.51   209.3 3000.58
     2143003.054   221.2 3006.07   238.2 3007.37     261 3007.41   295.5 3004.45
   320.2 3010.18   334.6  3009.8   368.1 3004.93   394.7 3008.88   449.7 3006.78
   466.3 3008.29   474.4 3010.37   490.7 3017.92   543.8 3030.96   617.9 3046.75
#Mann= 5 ,-1,0
       0      .1       0     130     .06       0   160.5    .045       0
     214     .06       0     280      .1       0
#XS Ineff= 2 , 0
                          326.35         3012.27
Permanent Ineff=
       F       F
Bank Sta=160.5,214
XS Rating Curve= 0 ,0
Exp/Cntr=0.3,0.1

Type RM Length L Ch R = 1 ,35750   ,340.4,332.3,323.1
XS GIS Cut Line= 2
     2324807.258      519202.371     2324667.758      519735.689
#Sta/Elev= 30
       0 3048.28    52.5 3020.83    60.8 3014.77    69.1  3006.5    73.2 3004.14
    89.7 3002.25    96.6 2997.53   102.1 2995.65   126.9 2995.37   139.2 2997.53
   147.6 3001.92   151.7 3002.64     160 3002.04   178.5 3004.46   217.9 3003.69
   226.2 3002.59   242.7 3006.92     251 3007.76   292.3 3004.18   317.1 3006.42
   395.7 3005.08     404 3006.87   420.5 3013.42     437 3015.49   457.7 3019.66
   469.9 3023.27   478.4 3023.31   493.1 3026.61     528 3031.89   551.3    3039
#Mann= 4 ,-1,0
       0      .1       0    96.6    .045       0   139.2     .06       0
     210      .1       0
Bank Sta=96.6,139.2
XS Rating Curve= 0 ,0
Exp/Cntr=0.3,0.1

Type RM Length L Ch R = 1 ,35417   ,346.9,338,327.2
XS GIS Cut Line= 2
     2324443.247      519102.217      2324455.17      519690.024
#Sta/Elev= 30
       0 3067.54    18.4 3055.28      55 3034.29      75 3026.42     123 3000.49
     135 2996.11   161.3 2995.93   172.4 2990.95     179 2988.79     191 2988.64
     211 2988.83   214.9 2990.47     223 2994.07   238.9 2995.59     259 2994.11
     291 2994.95     323 2994.18     331 2992.89     335 2993.32     343 2996.57
     367 2996.85     391 2999.66     423 2998.79   434.9  3004.9   450.8 3008.92
   491.1 3014.21   503.1 3014.71   543.1 3021.39   571.1 3028.65   587.9 3034.98
#Mann= 5 ,-1,0
       0      .1       0     110     .06       0   172.4    .045       0
   214.9     .06       0     310      .1       0
#XS Ineff= 2 , 0
                          244.67         2999.19
Permanent Ineff=
       F       F
Bank Sta=172.4,214.9
XS Rating Curve= 0 ,0
Exp/Cntr=0.3,0.1

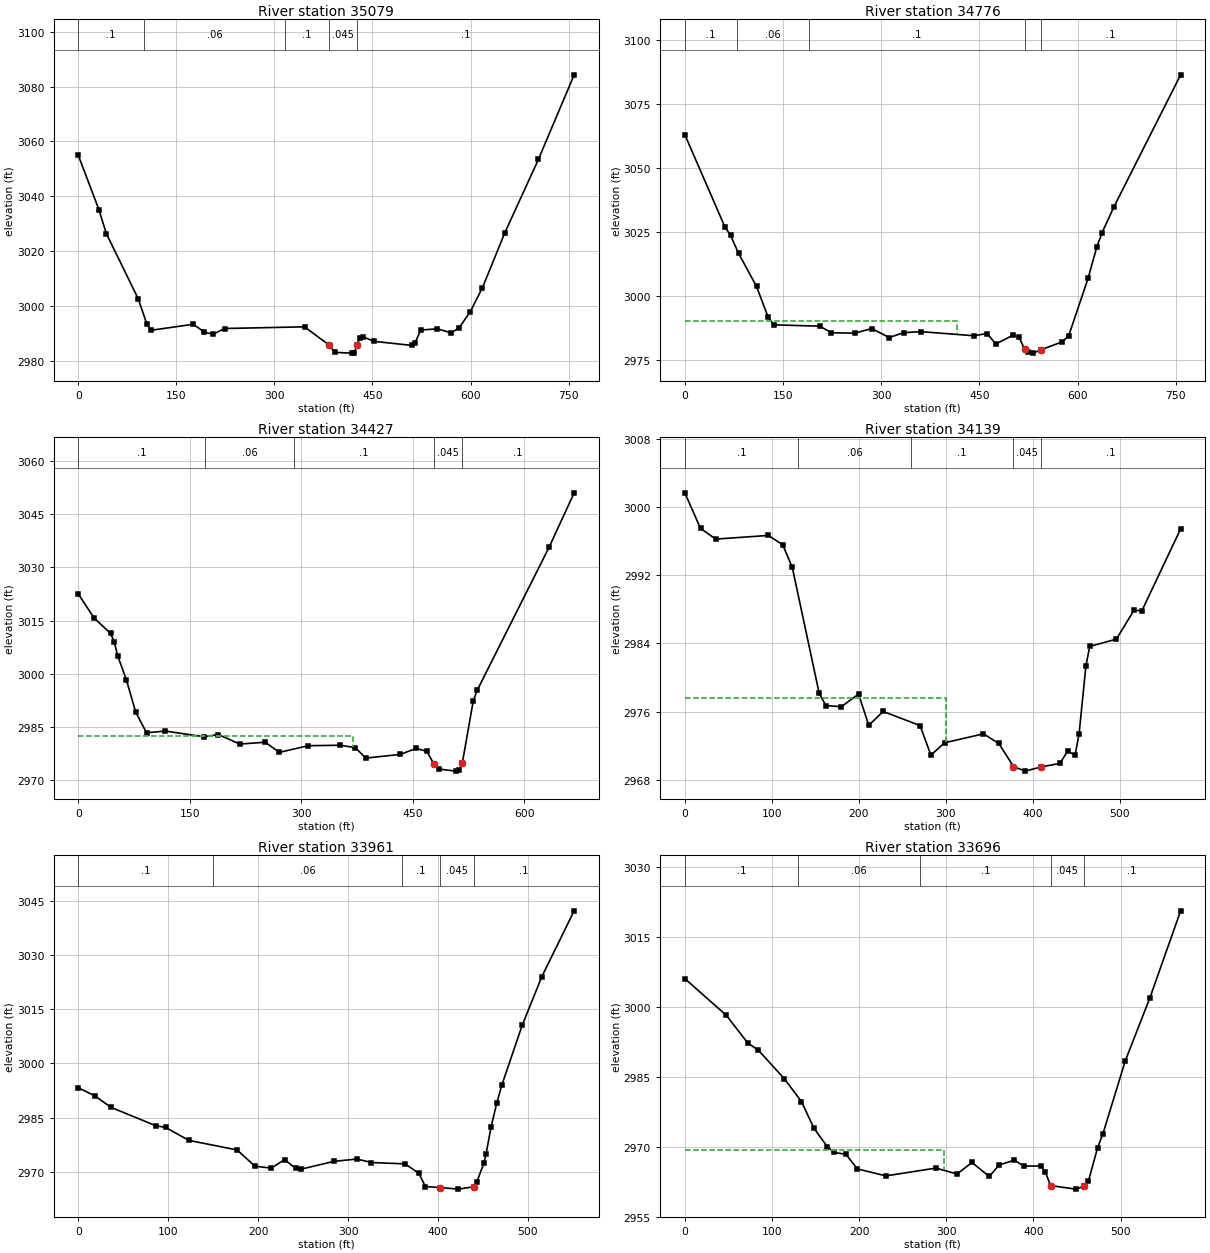
Type RM Length L Ch R = 1 ,35079   ,281,303.2,320
XS GIS Cut Line= 4
     2324231.017      519022.333     2324097.478      519309.678
     2324186.901      519567.216     2324160.671      519734.139
#Sta/Elev= 30
       0 3054.93    31.4 3035.24    42.8 3026.51    91.4 3002.86   104.6 2993.76
   111.1 2991.29   175.9 2993.49   192.8 2990.62     206 2989.84   223.7 2991.94
     346 2992.55     383 2986.03   392.5 2983.25     418 2982.98   422.2 2983.15
   426.4 2985.97   430.7  2988.6   434.9    2989   451.8 2987.28   510.3 2985.78
   515.3 2986.84   523.8 2991.38   549.2 2991.82   570.4 2990.36   582.6 2992.22
   599.6 2998.08   618.1 3006.72   652.2 3026.66   703.9 3053.53   758.5 3084.26
#Mann= 5 ,-1,0
       0      .1       0     100     .06       0   316.8      .1       0
     383    .045       0   426.4      .1       0
Bank Sta=383,426.4
XS Rating Curve= 0 ,0
Exp/Cntr=0.3,0.1

Type RM Length L Ch R = 1 ,34776   ,344,348.6,353.9
XS GIS Cut Line= 2
     2324054.555      518937.679     2323737.402      519625.639
#Sta/Elev= 30
       0 3063.14    61.1 3027.19    69.9 3023.79    82.1 3016.79   109.6 3003.84
   127.2 2991.93     136 2988.87   206.3 2988.34   224.1 2985.79   259.3 2985.59
   285.7 2987.42   312.2  2983.9   334.2  2985.8   360.2 2986.21   441.6 2984.61
   461.9 2985.48   475.1 2981.37   501.6 2984.85   510.4 2984.08   519.2 2979.39
   523.6 2978.08     532 2977.82   544.9 2979.19   576.5 2982.22   586.3 2984.44
   616.1    3007   629.3 3019.13   637.5 3024.86   655.4 3034.83   757.5 3086.48
#Mann= 5 ,-1,0
       0      .1       0      80     .06       0     190      .1       0
   519.2    .045       0   544.9      .1       0
#XS Ineff= 2 , 0
          416.04 2990.48
Permanent Ineff=
       F       F
Bank Sta=519.2,544.9
XS Rating Curve= 0 ,0
Exp/Cntr=0.3,0.1

Type RM Length L Ch R = 1 ,34427   ,283.5,288.5,292.2
XS GIS Cut Line= 2
     2323789.864      518873.294      2323415.48      519425.332
#Sta/Elev= 30
       0  3022.5    21.3 3015.71    43.4 3011.36    48.2 3009.06      53    3005
    64.5 2998.36    77.2 2989.12    91.7 2983.31     117 2983.79     169 2982.19
   188.3 2982.81   217.1 2980.13   251.2 2980.64   270.5 2977.79   309.2 2979.66
   352.2 2979.79   372.6 2979.11   386.5 2976.16   433.1 2977.21   454.2 2978.89
   468.7 2978.08   478.52974.365     485 2973.07   507.3 2972.48   512.2  2972.9
   516.32974.644     531  2992.2   536.3 2995.28     633 3035.68   666.8 3051.09
#Mann= 5 ,-1,0
       0      .1       0     170     .06       0     290      .1       0
   478.5    .045       0   516.3      .1       0
#XS Ineff= 2 , 0
          368.84 2982.32
Permanent Ineff=
       F       F
Bank Sta=478.5,516.3
XS Rating Curve= 0 ,0
Exp/Cntr=0.3,0.1

Type RM Length L Ch R = 1 ,34139   ,179.1,178.4,180.7
XS GIS Cut Line= 2
     2323552.595      518823.217     2323161.519       519238.14
#Sta/Elev= 30
       0 3001.64    18.1 2997.47    35.6 2996.22    96.1 2996.65   112.6 2995.55
   123.6 2992.91   154.5 2978.18   162.1 2976.72     180 2976.59   199.8 2978.06
   211.6 2974.41   228.1 2976.03   270.5 2974.38     283 2970.92   298.8 2972.36
   343.5 2973.41   361.1 2972.28     378 2969.58   391.3 2969.04   409.8 2969.53
   431.4 2969.95   440.3 2971.41   448.8  2970.9   453.4 2973.38   461.3 2981.38
   465.7 2983.65   496.3  2984.5   516.7 2987.91   525.5 2987.79   570.2 2997.41
#Mann= 5 ,-1,0
       0      .1       0     130     .06       0     260      .1       0
     378    .045       0   409.8      .1       0
#XS Ineff= 2 , 0
          300.34 2977.62
Permanent Ineff=
       F       F
Bank Sta=378,409.8
XS Rating Curve= 0 ,0
Exp/Cntr=0.3,0.1

Type RM Length L Ch R = 1 ,33961   ,261.2,264.1,266
XS GIS Cut Line= 2
     2323423.826      518711.141     2323039.903      519106.986
#Sta/Elev= 30
       0 2993.23    18.2 2991.03    36.3 2987.82    86.1 2982.75    97.2 2982.25
   122.8 2978.69   176.6 2976.03   196.4 2971.54   214.6 2971.01   229.3 2973.36
   241.6 2970.97   247.3  2970.7   284.1 2972.87   309.7 2973.53     326 2972.56
   363.3 2972.19   378.7 2969.58   385.9 2965.92   401.7 2965.65   422.7  2965.2
   439.7 2965.85   443.1 2967.15     451  2972.4   453.4 2974.89   459.1 2982.52
   465.3 2988.98   470.9 2993.93   493.6 3010.52   515.5    3024   551.4 3042.19
#Mann= 5 ,-1,0
       0      .1       0     150     .06       0     360      .1       0
   401.7    .045       0   439.7      .1       0
Bank Sta=401.7,439.7
XS Rating Curve= 0 ,0
Exp/Cntr=0.3,0.1

Type RM Length L Ch R = 1 ,33696   ,340.5,340,339.7
XS GIS Cut Line= 2
     2323273.595      518541.833     2322844.365      518915.025
#Sta/Elev= 30
       0 3006.06    47.8 2998.16    72.2 2992.26    84.4 2990.71     114 2984.63
   133.8 2979.71     148 2974.03   163.6 2969.98   171.5 2968.79   184.8 2968.39
     198 2965.26   230.7 2963.77   288.1 2965.44   312.4 2964.17   329.4 2966.64
   349.3 2963.64   360.6 2966.11   378.2 2967.14   388.8 2965.88   408.8 2965.88
   413.6 2964.58   419.7 2961.69   448.5 2960.93   457.7  2961.5     463 2962.63
   473.6 2969.84   479.7 2972.83   505.4 2988.48   533.6 3001.97   568.8 3020.59
#Mann= 5 ,-1,0
       0      .1       0     130     .06       0     270      .1       0
   419.7    .045       0   457.7      .1       0
#XS Ineff= 2 , 0
          296.91  2969.3
Permanent Ineff=
       F       F
Bank Sta=419.7,457.7
XS Rating Curve= 0 ,0
Exp/Cntr=0.3,0.1

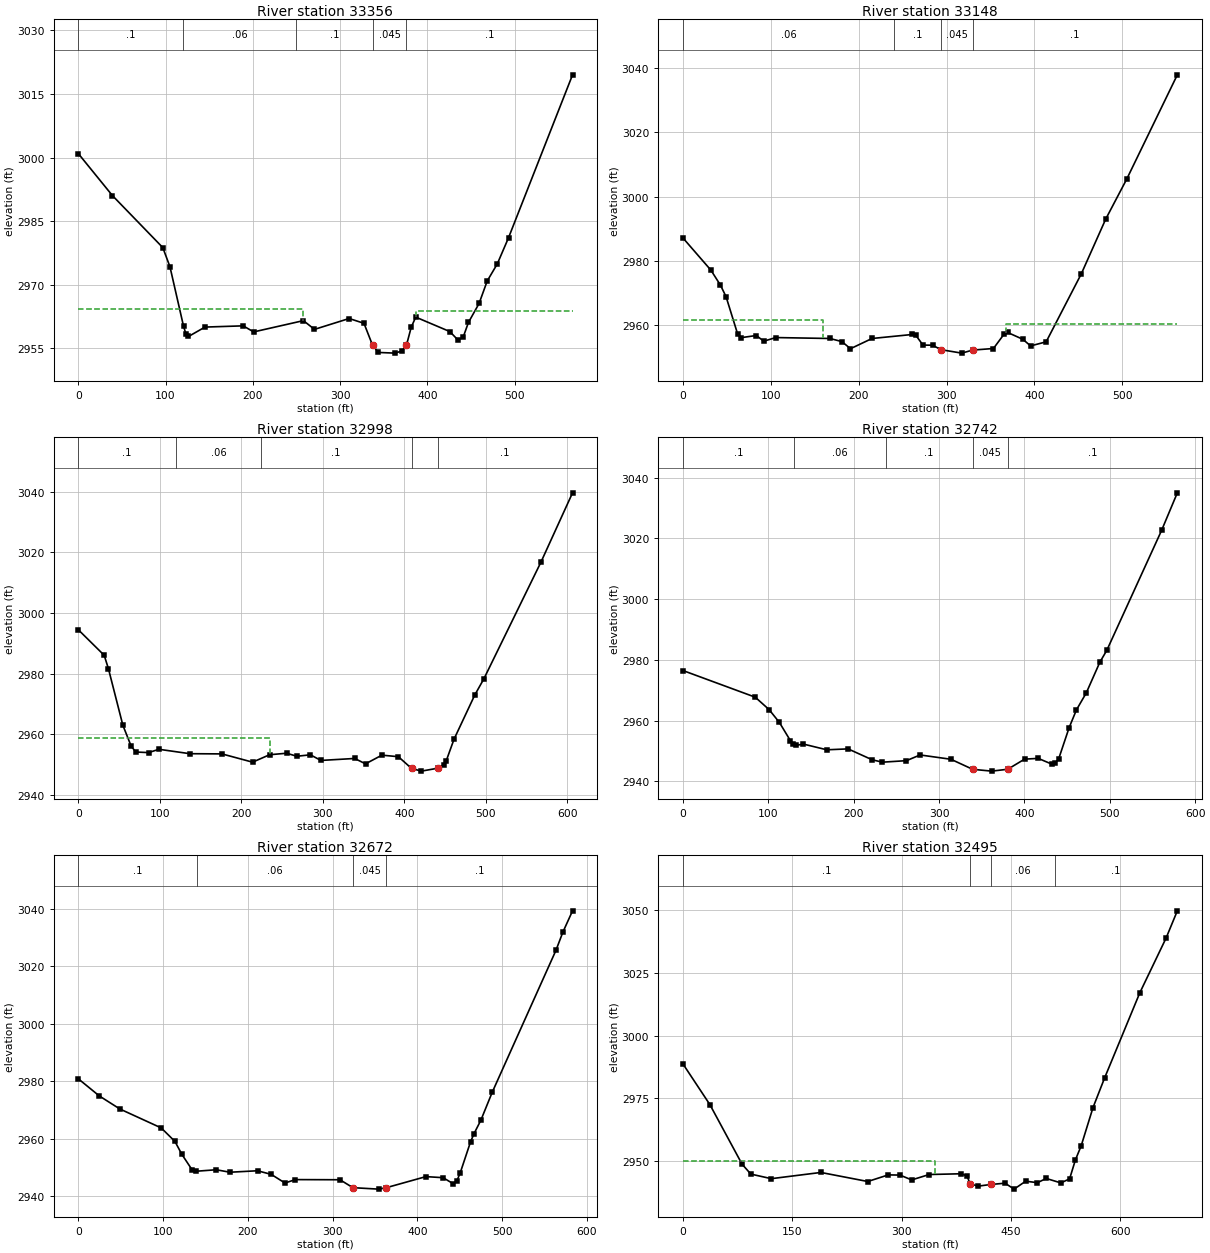
Type RM Length L Ch R = 1 ,33356   ,232.8,208.1,189.3
XS GIS Cut Line= 3
     2322968.365      518351.064     2322671.481      518616.949
     2322607.096      518771.948
#Sta/Elev= 30
       0 3000.95    39.1 2991.05    96.9 2978.77   105.1 2974.24   120.6 2960.28
   123.4 2958.39   126.3 2957.82   145.2 2960.04     189 2960.33     201  2958.9
     258 2961.56   270.7  2959.5   310.4 2962.06   327.4 2960.93   337.2 2955.78
   343.9 2954.06   362.9  2953.9   370.8  2954.4   376.1 2955.77   381.5 2959.98
   386.7 2962.39   425.7 2958.99   434.9 2957.04     441 2957.62   447.1 2961.13
   459.3 2965.61   468.6  2970.9   480.2 2974.95   493.1 2981.13   566.4  3019.5
#Mann= 5 ,-1,0
       0      .1       0     120     .06       0     250      .1       0
   337.2    .045       0   376.1      .1       0
#XS Ineff= 2 , 0
          257.05 2964.29  386.94         2963.82
Permanent Ineff=
       F       F
Bank Sta=337.2,376.1
XS Rating Curve= 0 ,0
Exp/Cntr=0.3,0.1

Type RM Length L Ch R = 1 ,33148   ,153.7,149.9,149.8
XS GIS Cut Line= 4
2322666.00674018518230.6425424272322522.33684959518429.680218205
2322511.87090043518557.0159329682322430.06045196 518727.74464972
#Sta/Elev= 30
       0  2987.1    31.8 2977.07    42.6 2972.42      49 2968.81    62.3 2957.07
    66.2 2956.07    83.4 2956.74    91.9 2954.97   105.6  2956.1   167.2 2955.81
   180.8 2954.84   190.6 2952.63   215.1 2955.81     261 2957.06     265 2956.79
   273.1 2953.75   284.1 2953.72   293.42952.334   317.2 2951.25   329.7  2952.2
   353.3 2952.69   365.4 2957.17   369.4 2957.69   386.7 2955.57   395.6  2953.5
   413.3 2954.77   453.3 2975.95   481.1 2993.01   505.1 3005.52   562.6 3037.95
#Mann= 4 ,-1,0
       0     .06       0     240      .1       0   293.4    .045       0
   329.7      .1       0
#XS Ineff= 2 , 0
          159.34 2961.56  367.21         2960.41
Permanent Ineff=
       F       F
Bank Sta=293.4,329.7
XS Rating Curve= 0 ,0
Exp/Cntr=0.3,0.1

Type RM Length L Ch R = 1 ,32998   ,243.9,256.2,273
XS GIS Cut Line= 5
     2322530.803      518136.567     2322433.553      518255.503
     2322368.635      518473.872     2322366.251      518559.718
     2322311.405      518687.295
#Sta/Elev= 30
       0 2994.51    31.8 2986.08      37 2981.67    54.7 2963.05    64.8 2956.22
    70.5 2954.23    86.3 2954.04    98.9 2955.13   136.9 2953.68   176.2 2953.61
   213.8 2950.89   234.7 2953.34   255.5 2953.83   268.1 2952.84   284.7 2953.31
   297.6 2951.46     339 2952.11   352.3 2950.34   372.4  2953.2   392.6 2952.69
   408.7 2948.84   420.8 2947.94   440.8 2948.89   448.8    2950   451.3 2951.34
   460.8 2958.42   486.3 2973.01   497.4 2978.31   567.5 3016.79   606.2 3039.57
#Mann= 5 ,-1,0
       0      .1       0     120     .06       0   223.7      .1       0
   408.7    .045       0   440.8      .1       0
#XS Ineff= 2 , 0
          235.74    2959
Permanent Ineff=
       F       F
Bank Sta=408.7,440.8
XS Rating Curve= 0 ,0
Exp/Cntr=0.3,0.1

Type RM Length L Ch R = 1 ,32742   ,82.2,70.6,57.4
XS GIS Cut Line= 5
 2322107.0938744518093.2826735682322134.09822528518298.864183491
2322141.06709003518410.3660193812322101.86722585518480.054666813
2322118.41827961518659.502933949
#Sta/Elev= 30
       0 2976.47    84.6  2967.7   100.8 2963.62   112.9 2959.38   125.7 2953.42
     129 2952.26   132.8 2951.85   141.1 2952.24   168.5 2950.36   193.4 2950.66
   221.7 2947.06   233.7 2946.28   261.8 2946.78   277.8 2948.66   313.9 2947.24
   339.4 2943.93   361.7 2943.33   380.5 2943.95   400.2 2947.28   416.2 2947.53
   432.3 2945.62   436.3 2945.97   440.3 2947.49   452.4 2957.65     461 2963.53
   472.5 2969.11   488.5 2979.28   496.6 2983.16   560.8  3022.7   579.2 3035.05
#Mann= 5 ,-1,0
       0      .1       0     130     .06       0  237.35      .1       0
   339.4    .045       0   380.5      .1       0
Bank Sta=339.4,380.5
XS Rating Curve= 0 ,0
Exp/Cntr(USF)=0,0
Exp/Cntr=0.3,0.1

Type RM Length L Ch R = 1 ,32672   ,184.5,177.1,170.5
XS GIS Cut Line= 4
2322036.00175834518088.6982422242322073.12065878 518307.57526442
2322028.69414604518573.2632327522322036.85829768518664.684189022
#Sta/Elev= 30
       0 2980.86    24.8 2974.88    49.1 2970.32    97.9 2963.72   114.1    2959
   122.2 2954.53   134.4 2949.07   138.4 2948.61   162.8 2949.14     179 2948.28
   211.5 2948.79   227.7 2947.53   243.9 2944.52   256.1 2945.71   308.8 2945.66
  324.03  2942.9   354.3 2942.39   363.2 2942.87   410.2 2946.75   430.5 2946.38
   442.6 2944.23   446.7 2945.27   450.7 2948.09   462.9 2958.92     467 2961.75
   475.1 2966.46   488.3 2976.07   563.6 3025.61   571.9 3032.04   583.2 3039.39
#Mann= 4 ,-1,0
       0      .1       0     140     .06       0  324.03    .045       0
   363.2      .1       0
Bank Sta=324.03,363.2
XS Rating Curve= 0 ,0
Exp/Cntr=0.3,0.1

Type RM Length L Ch R = 1 ,32495   ,228.1,230.1,235.2
XS GIS Cut Line= 2
     2321845.213       518012.45     2321898.867      518688.487
#Sta/Elev= 30
       0 2988.71    36.8 2972.55      81 2948.77      93 2944.82   121.1 2942.99
   189.1 2945.47   253.5 2941.86   281.6  2944.5   297.7 2944.42   313.7 2942.49
   337.8 2944.65   381.9 2944.95   389.8 2943.99   393.8 2940.95   404.9 2940.01
   422.1 2940.67   441.9 2941.19   454.2 2938.82   470.2 2941.99   486.3 2941.39
   498.3 2943.08   518.4  2941.3   530.4 2942.92   538.4 2950.52   546.2 2956.03
   562.5 2971.35   578.5 2983.23   626.7 3017.11   662.8 3038.98   678.2 3049.82
#Mann= 4 ,-1,0
       0      .1       0   393.8    .045       0   422.1     .06       0
     510      .1       0
#XS Ineff= 2 , 0
          346.39 2949.96
Permanent Ineff=
       F       F
Bank Sta=393.8,422.1
XS Rating Curve= 0 ,0
Exp/Cntr=0.3,0.1

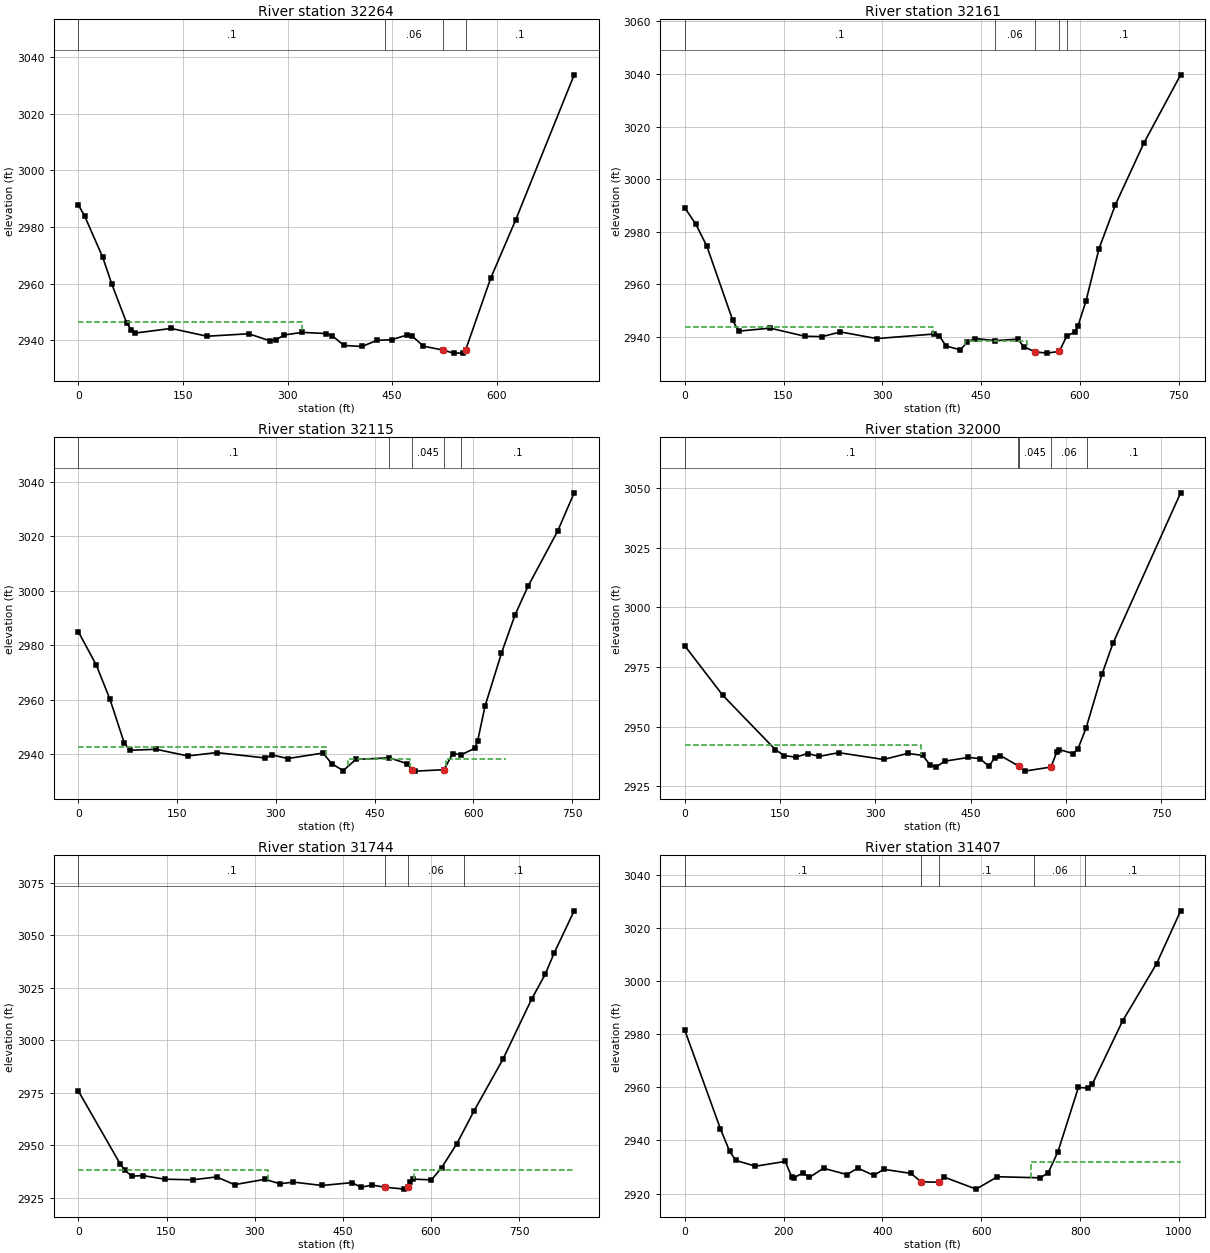
Type RM Length L Ch R = 1 ,32264   ,92,103.2,112.9
XS GIS Cut Line= 3
     2321840.444       518012.45     2321674.713      518454.795
     2321668.752      518693.256
#Sta/Elev= 30
       0 2987.79     9.3  2983.7      35 2969.25    47.8 2959.96    69.1 2946.19
    75.9 2943.68    81.9 2942.55   133.2 2944.17   184.5 2941.42   244.3 2942.29
   274.2 2939.84   282.7  2940.1   295.5 2941.88   320.8 2942.78   355.3 2942.36
   363.9  2941.6   380.9 2938.17   406.6  2937.8   427.9 2939.95   449.3  2940.2
   470.6 2941.81   478.8 2941.44   494.8 2937.91   522.92936.538   537.9 2935.46
   550.8 2935.47   555.32936.637   591.2 2961.93   626.8 2982.36   710.8 3033.66
#Mann= 4 ,-1,0
       0      .1       0     440     .06       0   522.9    .045       0
   555.3      .1       0
#XS Ineff= 2 , 0
          320.73 2946.35
Permanent Ineff=
       F       F
Bank Sta=522.9,555.3
XS Rating Curve= 0 ,0
Exp/Cntr=0.5,0.3

Type RM Length L Ch R = 1 ,32161   ,46.9,45.9,45.8
XS GIS Cut Line= 3
     2321799.906      517994.565     2321560.252      518535.872
     2321551.906      518696.833
#Sta/Elev= 30
       0 2989.13    16.9 2982.82    33.5 2974.52    72.9 2946.28    81.6 2942.21
   129.7 2943.35   182.2 2940.28   208.5 2940.12   236.5 2941.91   291.6 2939.38
   379.1 2941.13   386.9 2940.34   396.6  2936.6   418.4 2935.09   429.3 2938.07
   440.3 2939.41   471.8  2938.6   505.9 2939.17   514.7 2936.34   531.6 2934.37
   549.7 2933.85   568.8 2934.49   580.3 2940.37   593.3 2941.94   597.3 2944.22
   609.3 2953.55   629.3 2973.62   654.2 2990.35   697.4 3013.76   753.2  3039.7
#Mann= 5 ,-1,0
       0      .1       0   471.8     .06       0   531.6    .045       0
   568.8     .06       0   580.3      .1       0
#XS Ineff= 3 ,-1
       0  377.55 2943.91     425   519.5  2938.4   580.5     750  2938.2
Permanent Ineff=
       F       F       F
Bank Sta=531.6,568.8
XS Rating Curve= 0 ,0
Exp/Cntr=0.5,0.3

Type RM Length L Ch R = 1 ,32115   ,120.2,115.8,113.9
XS GIS Cut Line= 3
     2321752.213        517989.2      2321512.56      518530.506
     2321504.214      518691.468
#Sta/Elev= 30
       0 2984.97    27.3 2972.74    48.1 2960.12      70 2943.94    78.7 2941.44
   118.1 2941.82   166.2 2939.36     210  2940.6   284.3 2938.61   294.1 2939.72
   318.4 2938.42   371.8 2940.43   384.9 2936.51   402.4 2933.97   421.5 2938.08
   472.4 2938.68   498.7 2936.59   507.4 2934.28   511.8 2933.79   555.5 2934.31
   568.7 2940.26   581.8 2939.82   602.5  2942.2   606.7 2944.98   617.7 2957.56
   642.7 2977.05   663.4 2991.17   683.1 3001.64   728.2 3021.96   753.2 3035.97
#Mann= 5 ,-1,0
       0      .1       0   472.4     .06       0   507.4    .045       0
   555.5     .06       0   581.8      .1       0
#XS Ineff= 3 ,-1
       0  375.72 2942.58     410     504  2938.4   558.5     650  2938.2
Permanent Ineff=
       F       F       F
Bank Sta=507.4,555.5
XS Rating Curve= 0 ,0
Exp/Cntr=0.5,0.3

Type RM Length L Ch R = 1 ,32000   ,243.8,255.7,263.8
XS GIS Cut Line= 3
     2321686.637      517961.181     2321442.214      518390.411
     2321351.599      518662.256
#Sta/Elev= 30
       0 2983.89    59.8 2963.14   142.7 2940.31   156.5 2937.88   174.7 2937.18
   193.3 2938.73   211.7 2937.53   242.3 2939.08     313 2936.23   350.8 2938.76
   374.3 2937.95     386 2934.04   394.8    2933   409.5 2935.51   446.5 2937.09
   464.9 2936.57   478.7 2933.32   487.9 2937.01   496.9 2937.84   526.7  2933.3
   534.8 2931.34   576.3 2933.05   585.4 2939.21   589.5 2940.34   611.6 2938.73
   619.1 2940.83   631.8 2949.52   657.1 2972.28   673.9 2984.92   780.5 3048.07
#Mann= 5 ,-1,0
       0      .1       0   523.9     .06       0   526.7    .045       0
   576.3     .06       0   633.9      .1       0
#XS Ineff= 2 , 0
          371.13 2942.21
Permanent Ineff=
       F       F
Bank Sta=526.7,576.3
XS Rating Curve= 0 ,0
Exp/Cntr=0.3,0.1

Type RM Length L Ch R = 1 ,31744   ,329.1,336.5,339
XS GIS Cut Line= 3
     2321518.521       517888.45     2321139.368       518410.68
     2321089.291      518602.641
#Sta/Elev= 30
       0 2975.84    70.9 2941.21    79.5 2937.99      91  2935.2   109.6 2935.55
     147  2933.8   194.6 2933.51   235.5 2934.88   265.7 2931.19   317.2 2933.75
     343 2931.62   365.9 2932.42   414.6  2930.8   465.5 2932.17   480.4 2930.01
   500.2 2930.97   521.52930.012   554.5 2929.07   560.92930.149   564.4 2932.52
   569.2 2933.83   600.7 2933.48   617.9 2939.24     644 2950.73   672.7 2966.11
   722.3 2990.92   771.3 3019.68   794.3 3031.44   809.2 3041.39   843.5 3061.65
#Mann= 4 ,-1,0
       0      .1       0   521.5    .045       0   560.9     .06       0
   655.3      .1       0
#XS Ineff= 2 , 0
          321.88 2938.01  570.45          2938.3
Permanent Ineff=
       F       F
Bank Sta=521.5,560.9
XS Rating Curve= 0 ,0
Exp/Cntr=0.3,0.1

Type RM Length L Ch R = 1 ,31407   ,311.3,313.2,306
XS GIS Cut Line= 5
     2321363.522      517775.181      2321238.33      517926.604
     2321030.868       518027.95     2320831.753      518227.065
     2320779.292      518516.795
#Sta/Elev= 30
       0 2981.45      72 2944.41    90.8 2935.88   103.2 2932.49     143  2930.3
   203.3  2932.1   216.7 2926.14   220.6 2925.95   238.9 2927.75   252.3 2926.14
   280.8 2929.53     328 2927.17   350.2 2929.58   382.4 2926.84   402.8 2929.13
   457.4 2927.61   478.2 2924.44     514 2924.26   525.3 2926.18   589.6 2921.68
   632.8 2926.34   719.2 2925.94   735.5 2927.83   755.2  2935.8   796.5 2959.94
   816.3  2959.7   824.9 2961.27   885.8 2984.88   954.8  3006.5  1003.4 3026.37
#Mann= 5 ,-1,0
       0      .1       0   478.2    .045       0     514      .1       0
   707.4     .06       0   808.9      .1       0
#XS Ineff= 2 , 0
                          699.66         2931.96
Permanent Ineff=
       F       F
Bank Sta=478.2,514
XS Rating Curve= 0 ,0
Exp/Cntr=0.3,0.1

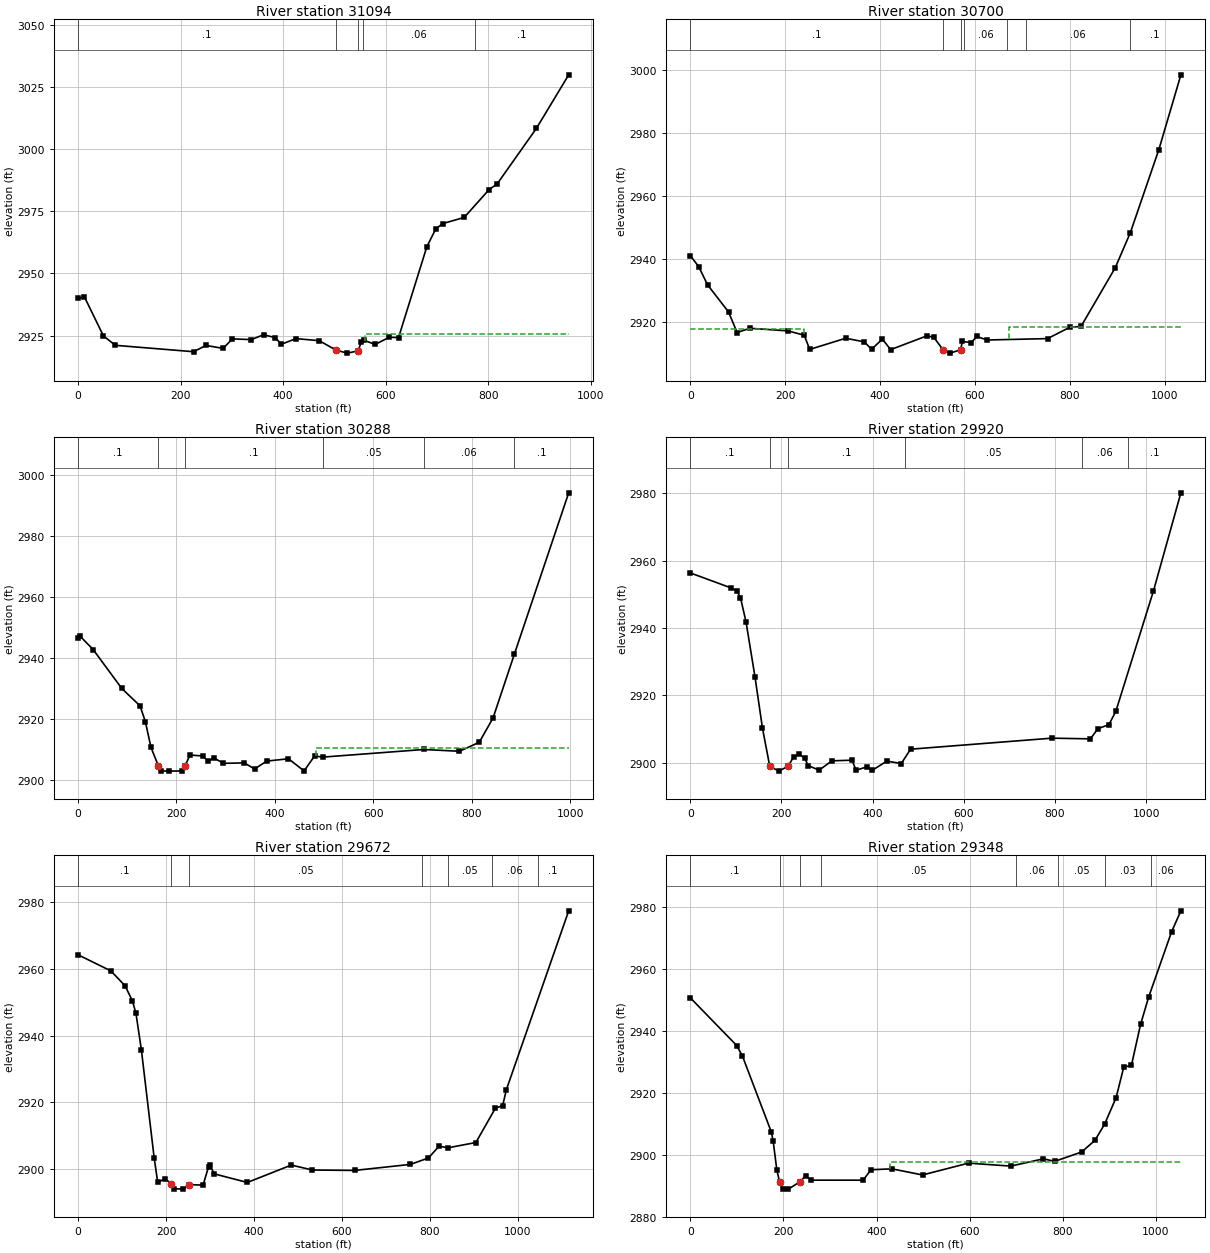
Type RM Length L Ch R = 1 ,31094   ,388.3,394.4,399.6
XS GIS Cut Line= 4
     2320841.292      517592.758     2320810.292      517956.411
     2320639.792      518272.372     2320614.754       518503.68
#Sta/Elev= 30
       0    2940    12.5  2940.5    49.5 2924.84    72.7 2921.08   225.2 2918.51
   249.3 2921.03   282.6 2919.86   301.1 2923.66   337.6 2923.38   361.7 2925.33
     384 2924.19   396.6 2921.52   424.9 2923.78   470.2 2922.94   502.9 2919.17
   524.9 2917.94   546.4 2918.87   552.2 2922.58   556.7 2923.16   579.5 2921.44
   606.7 2924.33   624.9 2924.18     680 2960.69   697.6 2967.94   711.3 2970.05
     753 2972.52   801.3 2983.68   817.3 2986.03   893.8 3008.36   956.7 3029.87
#Mann= 5 ,-1,0
       0      .1       0   502.9    .045       0   546.4      .1       0
     555     .06       0     774      .1       0
#XS Ineff= 2 , 0
                          560.14         2925.57
Permanent Ineff=
       F       F
Bank Sta=502.9,546.4
XS Rating Curve= 0 ,0
Exp/Cntr=0.3,0.1

Type RM Length L Ch R = 1 ,30700   ,410.9,411.8,414.2
XS GIS Cut Line= 5
2320796.96553179517554.0284508562320616.66607689517641.547664107
     2320525.331      517729.873     2320228.447      518117.373
     2320233.216      518335.565
#Sta/Elev= 30
       0 2941.13    17.9 2937.61    36.4 2931.87    80.8 2923.24    98.7 2916.75
   125.7 2918.09   205.6 2917.27   240.2  2915.9   251.7  2911.4   327.5 2914.93
   366.9 2913.79     382 2911.41   404.8 2914.67   422.3 2911.33     499 2915.71
   513.3 2915.21   533.2 2911.19   547.5 2910.22  569.57 2911.27   573.5 2913.91
   592.5 2913.56   603.7 2915.51   625.3 2914.38   752.9 2914.82   800.3 2918.45
   823.4 2918.66   895.5 2937.25   927.5 2948.43   987.5 2974.71  1033.9  2998.4
#Mann= 7 ,-1,0
       0      .1       0   533.2    .045       0  569.57      .1       0
  577.48     .06       0  667.48      .1       0  707.48     .06       0
  925.63      .1       0
#XS Ineff= 2 , 0
          238.78 2918.02   671.4         2918.41
Permanent Ineff=
       F       F
Bank Sta=533.2,569.57
XS Rating Curve= 0 ,0
Exp/Cntr=0.3,0.1

Type RM Length L Ch R = 1 ,30288   ,393.8,367.9,348.6
XS GIS Cut Line= 3
     2320237.985      517458.028      2319919.64      517825.258
     2319967.332      518334.372
#Sta/Elev= 30
       0 2946.45     4.2 2947.12    30.6 2942.76    88.9 2929.97   125.9 2924.28
   136.8 2919.08   148.1 2910.67     163 2904.65   168.3 2902.91   184.2 2902.84
   210.6  2902.9   217.62904.614   227.5 2908.13   253.1 2907.81   264.4 2906.09
   275.7 2907.17   295.6  2905.4   337.7 2905.54   358.9 2903.56   383.5 2906.13
   427.7  2906.9   459.4  2902.9   480.6 2907.79     498 2907.45   702.5 2909.94
   775.2 2909.36   815.4  2912.3   843.5 2920.28   886.8 2941.21   997.3  2994.2
#Mann= 6 ,-1,0
       0      .1       0     163    .045       0   217.6      .1       0
     498     .05       0   702.5     .06       0   886.8      .1       0
#XS Ineff= 2 , 0
                          484.54         2910.52
Permanent Ineff=
       F       F
Bank Sta=163,217.6
XS Rating Curve= 0 ,0
Exp/Cntr=0.3,0.1

Type RM Length L Ch R = 1 ,29920   ,257.4,247.6,237.8
XS GIS Cut Line= 3
     2319790.871      517267.259     2319753.909      517756.104
     2319824.255      518337.949
#Sta/Elev= 30
       0 2956.36    90.1 2951.87   102.2 2951.01   110.2 2948.99   122.3 2941.83
   141.9 2925.56   158.4 2910.23   174.4 2898.88   194.4 2897.44   215.4 2898.96
   226.6 2901.71   238.6  2902.5   250.9 2901.33   258.7 2899.08   282.7 2897.73
   310.8  2900.5   354.9 2900.69   363.7 2897.72     387 2898.68   399.6  2897.7
   431.1 2900.41     463  2899.7   483.3 2903.96   793.5 2907.24   877.9 2907.03
   894.2 2910.05   918.4 2911.26   933.5 2915.18    1016 2950.93  1076.3 2980.16
#Mann= 6 ,-1,0
       0      .1       0   174.4    .045       0   215.4      .1       0
     470     .05       0   860.2     .06       0   960.2      .1       0
Bank Sta=174.4,215.4
XS Rating Curve= 0 ,0
Exp/Cntr=0.3,0.1

Type RM Length L Ch R = 1 ,29672   ,323.3,324.6,323.9
XS GIS Cut Line= 4
     2319480.871      517293.489     2319554.794      517585.604
     2319529.756      518238.988     2319572.679      518393.987
#Sta/Elev= 30
       0 2964.14    74.9  2959.3     107 2954.85   123.5 2950.39   131.7 2946.62
   144.1 2935.63     173 2903.53   181.2  2896.1   197.7 2897.22   212.3  2895.7
   218.4 2894.23   239.5  2894.1   253.3 2895.44   284.4  2895.3   296.8 2900.81
   300.9 2901.27   308.9 2898.69     385 2896.09     485 2901.29   533.1 2899.81
   629.1 2899.69     756 2901.49   796.9 2903.41   821.3 2906.95   841.3 2906.45
   904.8 2908.03   949.4 2918.32   965.8 2919.03   974.1 2923.78    1116 2977.28
#Mann= 7 ,-1,0
       0      .1       0   212.3    .045       0   253.3     .05       0
   781.3     .06       0   841.3     .05       0   941.3     .06       0
  1045.2      .1       0
Bank Sta=212.3,253.3
XS Rating Curve= 0 ,0
Exp/Cntr=0.3,0.1

Type RM Length L Ch R = 1 ,29348   ,219.1,224.6,228.5
XS GIS Cut Line= 2
     2319176.833      517360.259     2319423.641      518384.449
#Sta/Elev= 30
       0 2950.81    99.7 2935.38     112 2931.99   173.8 2907.55   177.9 2904.65
   185.9 2895.18   191.9 2891.24   198.4    2889   210.8 2888.98   235.5 2891.36
   247.8 2893.27   260.2 2891.88   371.3 2891.87   388.1 2895.25     433 2895.53
   498.8 2893.56   597.5 2897.38   688.1 2896.42     758 2898.76   782.7 2897.97
   840.3 2900.97   868.9 2904.73   889.7 2909.96   914.4 2918.54   930.8 2928.39
   947.3 2928.97     967 2942.24   984.3 2951.04  1033.7  2972.2  1053.5  2978.9
#Mann= 8 ,-1,0
       0      .1       0   191.9    .045       0   235.5      .1       0
     280     .05       0     700     .06       0     790     .05       0
     890     .03       0     990     .06       0
#XS Ineff= 2 , 0
                          428.87         2897.71
Permanent Ineff=
       F       F
Bank Sta=191.9,235.5
XS Rating Curve= 0 ,0
Exp/Cntr=0.3,0.1