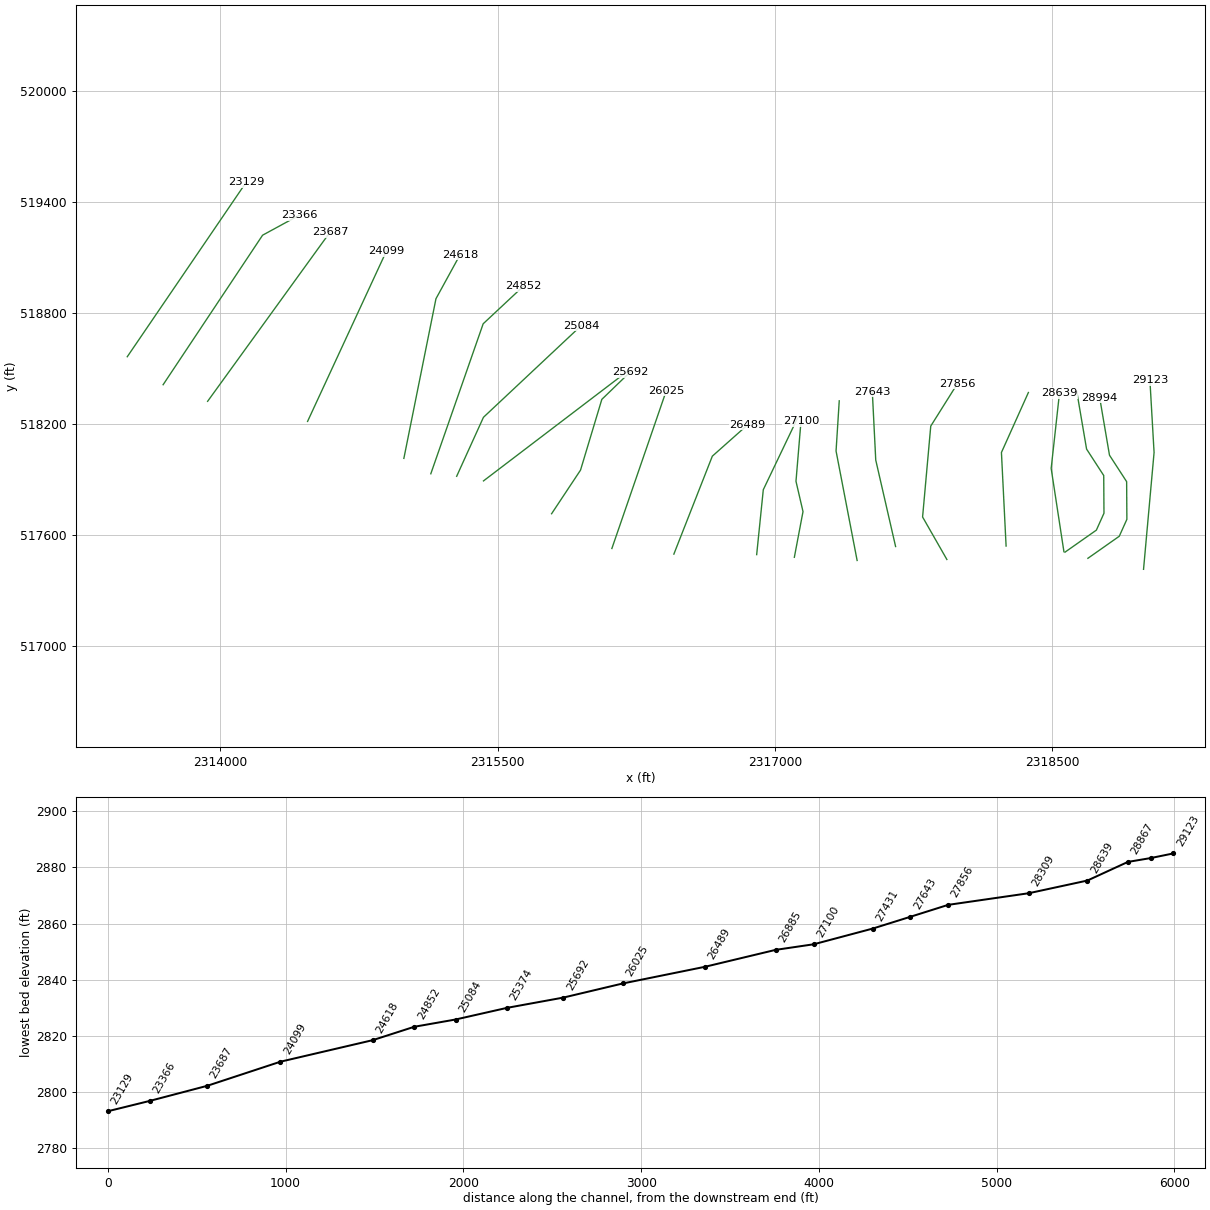
HEC-RAS study NRTHFRK.prj: NRTHFRK

--- NRTHFRK.g01 (geometry) --- (continued)

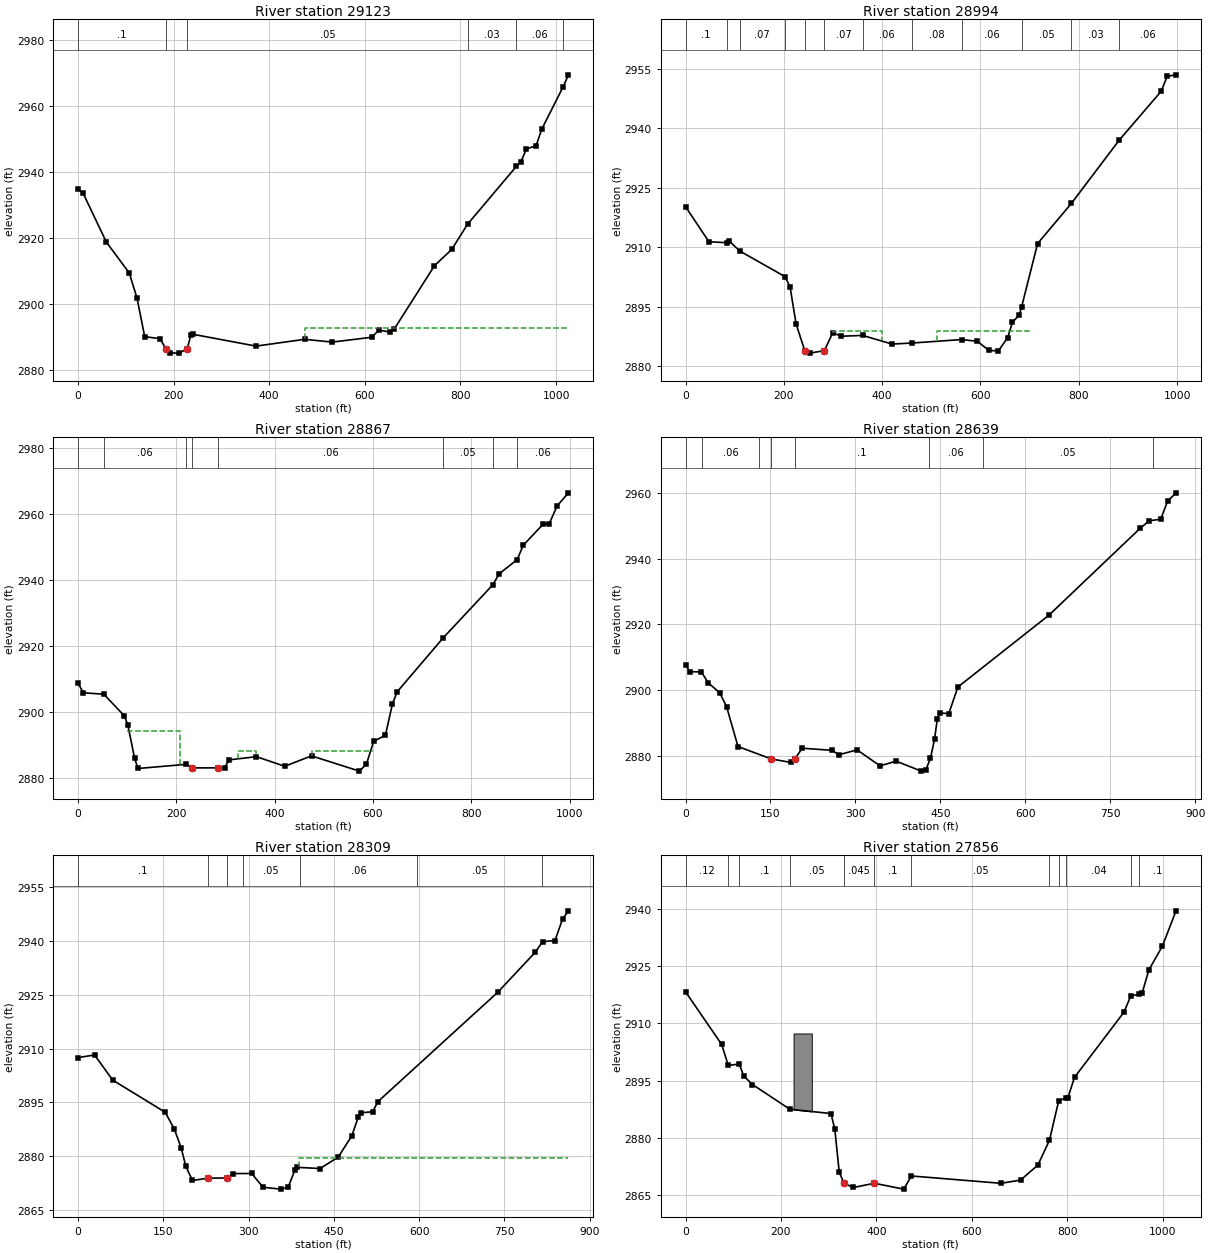
Type RM Length L Ch R = 1 ,29123   ,139.6,128.8,119.1
XS GIS Cut Line= 3
     2318992.423      517414.177     2319049.389      518046.099
     2319026.868       518436.91
#Sta/Elev= 30
       0  2934.8      11 2933.48    59.2 2918.76   107.4  2909.3   123.5 2901.75
   139.6 2890.02   171.7 2889.39   183.7 2886.38   191.8 2885.06   211.9 2885.01
   228.7 2886.37     236  2890.4     240 2890.74   372.5 2887.14   474.1  2889.2
   531.9 2888.36   614.1 2889.82   629.5 2891.97   653.5  2891.4   661.6 2892.33
   745.7 2911.55   781.8 2916.48     815 2924.16   917.1  2941.7   926.5 2943.14
   938.1 2946.99   958.1 2947.92   970.1 2952.99  1014.9 2965.87  1025.9 2969.46
#Mann= 6 ,-1,0
       0      .1       0   183.7    .045       0   228.7     .05       0
     815     .03       0   917.1     .06       0  1014.9      .1       0
#XS Ineff= 2 , 0
                             475         2892.73
Permanent Ineff=
       F       F
Bank Sta=183.7,228.7
XS Rating Curve= 0 ,0
Exp/Cntr=0.5,0.3

Type RM Length L Ch R = 1 ,28994   ,130.1,127.7,127.9
XS GIS Cut Line= 6
     2318691.697      517473.793      2318861.27      517593.023
     2318902.338      517684.433     2318901.013       517888.45
     2318808.278      518031.527     2318755.287      518342.851
#Sta/Elev= 30
       0 2920.24    47.6  2911.4    83.7 2911.15    89.3 2911.53   110.2 2909.07
   202.1 2902.63   212.6  2900.1     225 2890.67   242.5    2884   253.4 2883.34
   282.7 2883.98   299.6 2888.51   316.3 2887.59   360.3  2887.8   420.3 2885.62
   460.3 2885.88   561.8 2886.76   593.4 2886.32   617.3 2884.04   636.3 2883.87
   655.4 2887.24   664.9 2891.08   679.2 2893.03   683.6 2894.92   716.2 2910.93
   785.1 2921.07   882.5 2937.02   967.7  2949.3   979.9 2953.06   997.8 2953.43
#Mann= 12 ,-1,0
       0      .1       0    83.7     .06       0   110.2     .07       0
   202.1      .1       0   242.5    .045       0   282.7     .07       0
   360.3     .06       0   460.3     .08       0   561.8     .06       0
   683.6     .05       0   785.1     .03       0   882.5     .06       0
#XS Ineff= 2 ,-1
  300.38     400    2889     512     700    2889
Permanent Ineff=
       F       F
Bank Sta=242.5,282.7
XS Rating Curve= 0 ,0
Exp/Cntr=0.5,0.3

Type RM Length L Ch R = 1 ,28867   ,204.3,227.7,243.7
XS GIS Cut Line= 6
      2318567.83      517506.912     2318737.402      517626.143
     2318778.471      517717.553     2318777.146       517921.57
     2318684.411      518064.646      2318631.42       518375.97
#Sta/Elev= 30
       0 2908.75    10.9 2905.73    52.6 2905.31    94.3 2898.75   101.3 2896.08
   115.2  2885.9   122.2 2882.77   219.4 2884.02   232.9 2882.95   285.2 2882.96
   298.3 2882.96   307.1 2885.38   363.1 2886.35   420.7 2883.44   475.1  2886.6
   572.7 2881.97   586.9 2884.15   601.6 2891.01   625.5 2892.86   639.8  2902.4
   649.3 2906.03   743.4 2922.46   843.8 2938.47     857 2941.84   893.6 2946.14
   905.7 2950.47   946.3 2956.88   958.5 2956.95   974.7 2962.42   997.8 2966.39
#Mann= 8 ,-1,0
       0      .1       0    52.6     .06       0   219.4      .1       0
   232.9    .045       0   285.2     .06       0   743.4     .05       0
   843.8     .03       0   893.6     .06       0
#XS Ineff= 3 ,-1
     100   207.5  2894.2     325     363    2888  475.15     600    2888
Permanent Ineff=
       F       F       F
Bank Sta=232.9,285.2
XS Rating Curve= 0 ,0
Exp/Cntr=0.5,0.3

Type RM Length L Ch R = 1 ,28639   ,333,329.6,323.3
XS GIS Cut Line= 3
     2318561.869      517509.562      2318492.98      517959.988
     2318538.022      518368.022
#Sta/Elev= 30
       0 2907.76     7.7 2905.57    27.9 2905.54    40.1 2902.22    60.3 2899.17
    72.5 2894.99    92.7 2882.81   151.82879.025   185.8 2877.98   192.82878.922
     206 2882.29   258.6 2881.67   270.7 2880.31     303  2881.8   343.6 2876.93
   371.9 2878.37   416.4 2875.33   424.5 2875.75   432.6 2879.27   439.9 2885.16
   444.7 2891.25   448.8 2893.04   464.9 2892.83     481 2900.92     642 2922.82
     803 2949.24     819 2951.52   839.2 2951.98   851.2 2957.44   866.2 2960.02
#Mann= 8 ,-1,0
       0      .1       0      30     .06       0     130      .1       0
   151.8    .045       0   192.8      .1       0     430     .06       0
   525.6     .05       0   825.6     .06       0
Bank Sta=151.8,192.8
XS Rating Curve= 0 ,0
Exp/Cntr=0.3,0.1

Type RM Length L Ch R = 1 ,28309   ,458.7,453.4,434.1
XS GIS Cut Line= 3
      2318249.22      517540.032     2318224.049      518046.099
     2318369.775      518370.671
#Sta/Elev= 30
       0 2907.47    29.2 2908.22    61.2  2901.2   153.3 2892.26   169.4  2887.6
   181.4 2882.38   189.8 2877.12   201.4 2873.22   229.4 2873.88   262.6 2873.91
   273.5 2875.15   305.5 2875.17   325.5 2871.32   356.9 2870.81   369.6 2871.31
   381.6 2876.19   385.6 2876.89   425.6 2876.55   457.7 2879.73   481.7 2885.72
   493.2 2891.05   497.8 2892.08   518.2  2892.4   527.6 2895.23   738.1 2925.69
   803.8  2936.8     817  2939.8   838.8 2940.13   852.1  2946.1   862.5 2948.41
#Mann= 7 ,-1,0
       0      .1       0   229.4    .045       0   262.6      .1       0
     290     .05       0     390     .06       0   596.6     .05       0
   816.6     .06       0
#XS Ineff= 2 , 0
                           389.4         2879.56
Permanent Ineff=
       F       F
Bank Sta=229.4,262.6
XS Rating Curve= 0 ,0
Exp/Cntr=0.3,0.1

Type RM Length L Ch R = 1 ,27856   ,205.7,212.9,309.9
XS GIS Cut Line= 4
2317929.01005169517467.265446594  2317797.714076517697.175575482
2317841.87780878518188.9788049292317985.35686415518417.426425313
#Sta/Elev= 30
       0 2918.25    75.9 2904.48    89.7 2898.98   112.8 2899.37     122 2896.24
   140.4    2894   218.7 2887.55   304.9 2886.42     313 2882.33   322.3 2871.06
   332.6 2868.17   351.8 2867.09     396 2868.19   457.5 2866.66   473.6  2870.1
   661.3 2868.18   702.5 2869.03   738.7 2872.95   762.9 2879.39   782.4 2889.76
   798.1 2890.55   801.3  2890.4   815.5 2895.88   919.4 2912.96   933.5 2917.19
   950.9 2917.56   957.2 2917.85   971.3 2923.96   999.7 2930.17  1028.3 2939.41
#Mann= 12 ,-1,0
       0     .12       0    89.7    .016       0   112.8      .1       0
   218.7     .05       0   332.6    .045       0     396      .1       0
   473.6     .05       0   762.9     .04       0   782.4    .016       0
   798.1     .04       0   933.5    .016       0   950.9      .1       0
#Block Obstruct= 1 ,-1
  226.56  264.76 2907.35
Bank Sta=332.6,396
XS Rating Curve= 0 ,0
Exp/Cntr(USF)=0,0
Exp/Cntr=0.3,0.1

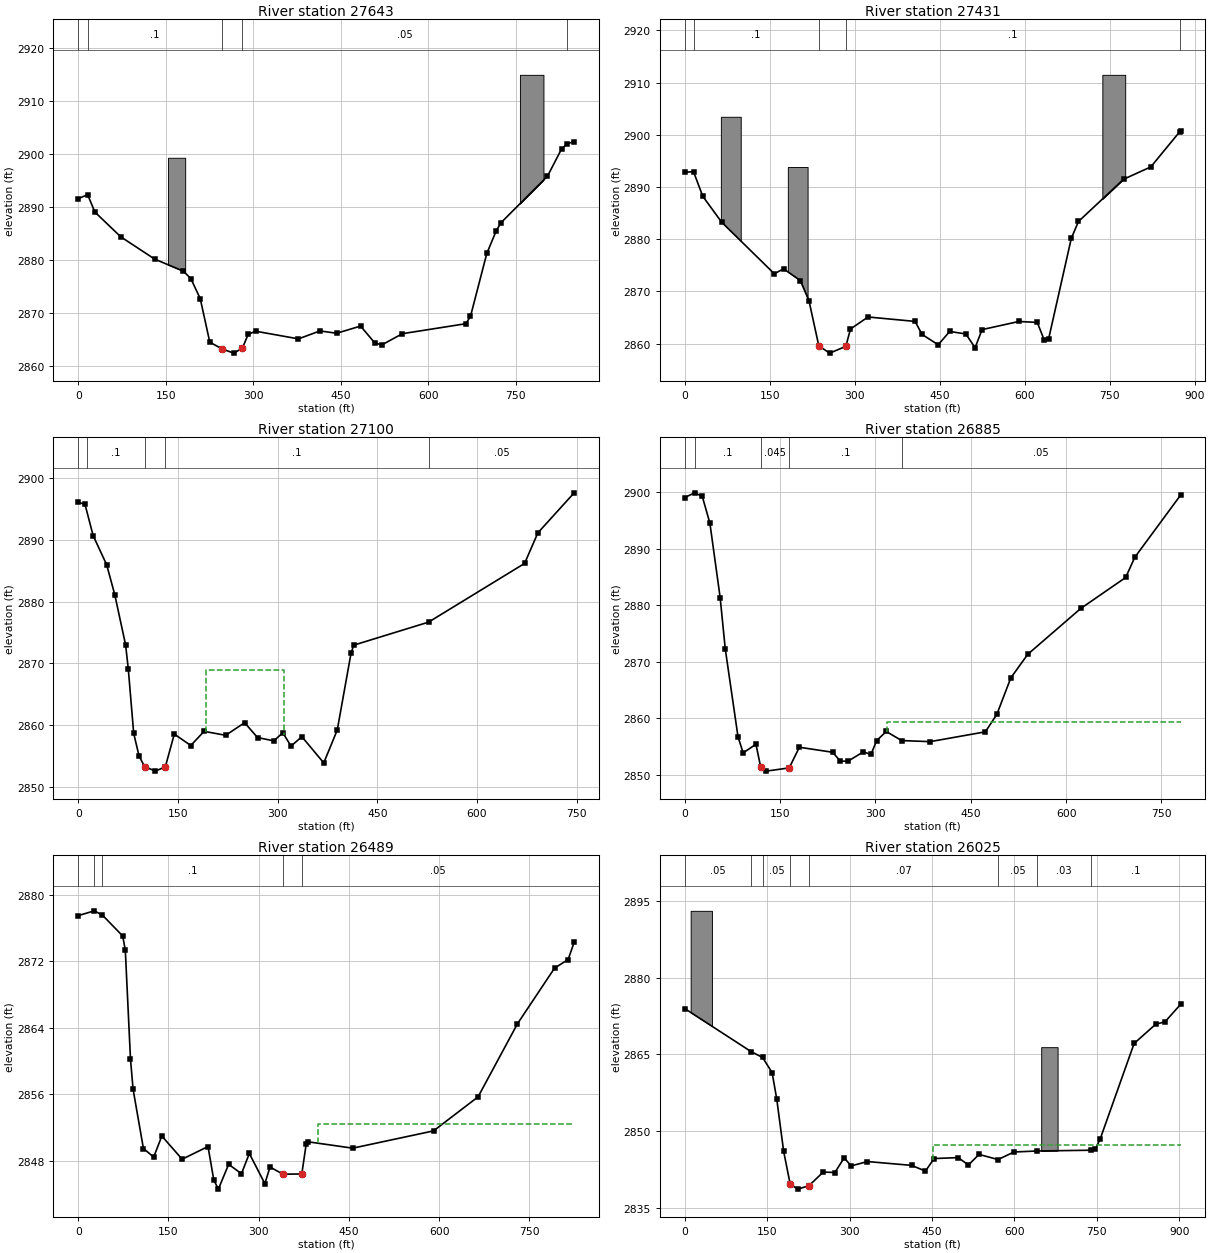
Type RM Length L Ch R = 1 ,27643   ,213.6,212.2,202.4
XS GIS Cut Line= 3
     2317651.742      517537.382     2317544.435      518005.031
     2317525.888      518374.646
#Sta/Elev= 30
       0 2891.55    16.2 2892.31    28.5 2889.03    72.9 2884.35   131.1 2880.14
   180.4 2877.86   193.1 2876.44   209.1 2872.69   225.5 2864.46   246.5  2863.2
   266.3  2862.4   281.2  2863.3   291.2 2865.92   303.9 2866.54   377.4 2865.09
   414.3 2866.59     443 2866.15   483.9 2867.51     508 2864.35     520 2863.94
   555.6 2866.07   664.2 2867.95   672.2 2869.32   700.2 2881.21   716.2 2885.44
   724.2 2886.97   804.2  2895.8   828.4 2900.94   838.1 2901.93   849.9 2902.31
#Mann= 5 ,-1,0
       0    .016       0    16.2      .1       0   246.5    .045       0
   281.2     .05       0   838.1    .016       0
#Block Obstruct= 2 ,-1
  153.93  183.31 2899.27  756.97   797.3 2914.92
Bank Sta=246.5,281.2
XS Rating Curve= 0 ,0
Exp/Cntr=0.3,0.1

Type RM Length L Ch R = 1 ,27431   ,336.1,331.3,266.8
XS GIS Cut Line= 3
     2317443.751      517461.869      2317329.82      518054.048
     2317347.042      518325.629
#Sta/Elev= 30
       0 2892.82    15.6 2892.93    31.9 2888.22    65.2 2883.27   158.2 2873.38
   174.5 2874.33     204 2872.09   219.3 2868.24   236.7 2859.58   255.9 2858.19
   284.4 2859.49   292.6 2862.81   323.6 2865.11   406.6 2864.26   418.9 2861.77
   447.4 2859.79   467.7 2862.34   496.2 2861.86   512.5 2859.22   524.8 2862.69
   589.8 2864.25   622.2 2864.07   634.2 2860.78   642.1 2860.84   682.3 2880.17
   694.9 2883.39   774.5 2891.48   822.6 2893.84   873.5 2900.56   875.2 2900.79
#Mann= 5 ,-1,0
       0    .016       0    15.6      .1       0   236.7    .045       0
   284.4      .1       0   873.5     .04       0
#Block Obstruct= 3 ,-1
   63.86   98.92 2903.44  182.03  216.91 2893.82  737.06  777.41 2911.47
Bank Sta=236.7,284.4
XS Rating Curve= 0 ,0
Exp/Cntr=0.3,0.1

Type RM Length L Ch R = 1 ,27100   ,212.5,214.7,227.2
XS GIS Cut Line= 4
2317104.26707106517479.1328879752317151.10207649517726.397176261
2317113.12883733517890.3010539692317140.27057378518215.542923507
#Sta/Elev= 30
       0 2896.05    10.2 2895.73    22.4 2890.68    42.8 2885.96      55 2881.12
    71.3 2873.01    75.4 2869.08    83.5  2858.7    91.6 2855.03    99.8 2853.34
   116.1  2852.6   131.12853.293   144.6 2858.59   169.4 2856.74   189.4 2859.03
   221.9 2858.39   250.4 2860.43   269.8 2858.03   294.2 2857.49   307.9  2858.8
   320.2 2856.65   336.6 2858.16   369.5 2853.93   389.8 2859.24   410.5 2871.63
   414.6 2872.96   527.2 2876.68   671.7 2886.17   691.7 2891.11   746.3 2897.58
#Mann= 5 ,-1,0
       0    .016       0    13.4      .1       0    99.8    .045       0
   131.1      .1       0   527.2     .05       0
#XS Ineff= 1 ,-1
  192.77  309.812868.902
Permanent Ineff=
       F
Bank Sta=99.8,131.1
XS Rating Curve= 0 ,0
Exp/Cntr=0.3,0.1

Type RM Length L Ch R = 1 ,26885   ,402.1,396.2,351.2
XS GIS Cut Line= 3
     2316900.589      517493.664     2316936.359      517844.732
     2317120.504      518230.244
#Sta/Elev= 30
       0 2899.04    15.6 2899.88    27.7 2899.25    39.7 2894.48    55.8 2881.33
    63.8 2872.27    83.9 2856.67      92 2853.82   112.1 2855.37   119.6 2851.29
   128.2  2850.6   164.4 2851.17   180.4 2854.83   232.7 2853.94   244.8 2852.38
   256.8 2852.35     281 2854.01     293 2853.55     302 2856.01   317.1 2857.62
   341.3 2856.01   386.1 2855.82     473 2857.56   491.1 2860.67     513 2867.11
   539.6 2871.28   623.1 2879.41   693.7 2884.89     708 2888.46   780.1 2899.48
#Mann= 5 ,-1,0
       0    .016       0    15.6      .1       0   119.6    .045       0
   164.4      .1       0   341.3     .05       0
#XS Ineff= 2 , 0
                             318         2859.23
Permanent Ineff=
       F       F
Bank Sta=119.6,164.4
XS Rating Curve= 0 ,0
Exp/Cntr=0.3,0.1

Type RM Length L Ch R = 1 ,26489   ,383.7,463.9,393.1
XS GIS Cut Line= 3
     2316452.813      517496.314     2316660.804      518026.227
     2316851.572        518195.8
#Sta/Elev= 30
       0  2877.5    26.7 2878.08    40.3 2877.56      74 2875.05    78.3 2873.33
    86.9 2860.23    91.2 2856.61   108.4 2849.47   125.5 2848.44     139 2850.97
   172.8 2848.18   215.8 2849.71   225.4 2845.68     233 2844.58   250.1 2847.56
   271.4 2846.44   284.5 2848.87   310.3 2845.24   318.9 2847.24   340.4 2846.38
   371.7  2846.4   379.1 2850.05   382.8 2850.27   456.4 2849.51   590.7 2851.59
   664.8 2855.69   730.3 2864.49   791.9 2871.18   814.5 2872.22   824.5 2874.29
#Mann= 5 ,-1,0
       0     .04       0    26.7    .016       0    40.3      .1       0
   340.4    .045       0   371.7     .05       0
#XS Ineff= 2 , 0
                           398.7         2852.47
Permanent Ineff=
       F       F
Bank Sta=340.4,371.7
XS Rating Curve= 0 ,0
Exp/Cntr=0.3,0.1

Type RM Length L Ch R = 1 ,26025   ,339.6,333.3,319.6
XS GIS Cut Line= 2
     2316117.642      517526.784     2316411.744      518379.945
#Sta/Elev= 30
       0 2873.98     121 2865.53   141.8 2864.39   159.1 2861.42   167.5 2856.27
   180.1    2846     192 2839.57   205.6 2838.61     226 2839.27   252.2 2841.96
   273.3 2841.86   290.2 2844.74   302.9 2843.16   332.6 2844.01   412.9 2843.26
   438.1 2842.14   453.8  2844.6   497.6 2844.78   516.3 2843.34   535.6 2845.41
   570.2  2844.4   599.1 2845.88   641.4 2846.08   740.1 2846.23   747.2 2846.47
   755.9 2848.39   817.8 2867.14   857.2 2870.91   874.1 2871.38   902.4  2874.8
#Mann= 8 ,-1,0
       0     .05       0     121    .016       0   141.8     .05       0
     192    .045       0     226     .07       0   570.2     .05       0
   641.4     .03       0   740.1      .1       0
#XS Ineff= 2 , 0
                           452.5         2847.25
Permanent Ineff=
       F       F
#Block Obstruct= 2 ,-1
   10.89   49.59 2893.11  648.71  678.55 2866.41
Bank Sta=192,226
XS Rating Curve= 0 ,0
Exp/Cntr=0.3,0.1

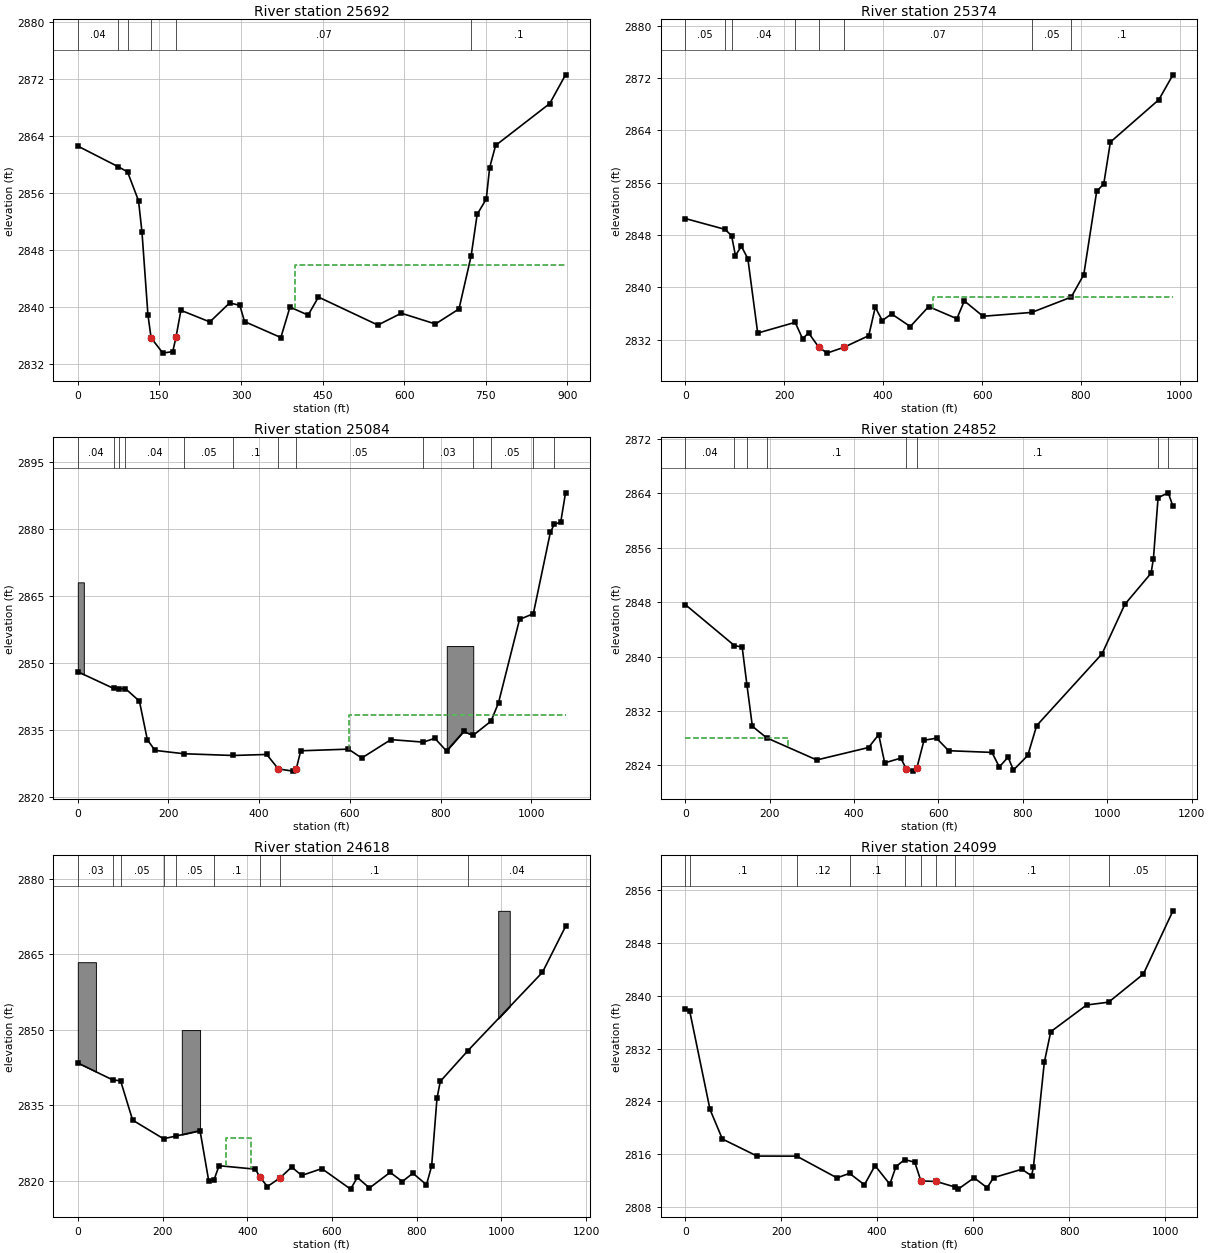
Type RM Length L Ch R = 1 ,25692   ,339.8,317.4,276
XS GIS Cut Line= 4
     2315791.745      517714.903      2315948.07      517950.715
     2316063.326      518333.577     2316217.001      518481.953
#Sta/Elev= 30
       0 2862.65    74.1 2859.76    91.4 2859.03   111.6 2854.98   117.9 2850.62
   128.9 2838.96   134.7 2835.74   156.3 2833.59   174.5 2833.81   180.4 2835.79
   189.5  2839.6   242.7 2837.97     279 2840.63   297.8  2840.3   306.4 2838.02
   373.2 2835.78   389.9 2840.05   423.3 2838.93   442.3 2841.46   551.5 2837.53
   594.6 2839.19   657.3 2837.68   700.6 2839.79   722.9 2847.23     734 2853.07
   750.7 2855.21     757 2859.64   767.9 2862.74   867.4 2868.62   896.4 2872.65
#Mann= 6 ,-1,0
       0     .04       0    74.1    .016       0    91.4     .05       0
   134.7    .045       0   180.4     .07       0   722.9      .1       0
#XS Ineff= 2 , 0
                          399.31         2845.98
Permanent Ineff=
       F       F
Bank Sta=134.7,180.4
XS Rating Curve= 0 ,0
Exp/Cntr=0.3,0.1

Type RM Length L Ch R = 1 ,25374   ,241.4,289.8,289.7
XS GIS Cut Line= 2
     2315423.455      517892.424     2316207.727      518489.902
#Sta/Elev= 30
       0 2850.52    80.5 2848.86    93.7 2847.89   101.5 2844.86   113.5 2846.27
   126.6 2844.38   146.5 2832.99   222.2 2834.63   237.2 2832.13   249.4    2833
   269.42830.889   286.5 2829.92   320.7 2830.81   370.9 2832.59   384.1 2836.94
   398.2 2834.91   417.1 2835.92   454.9 2833.99     492 2837.04     549 2835.19
   564.1 2837.91   601.9 2835.56   700.3 2836.15   780.1 2838.49   805.5 2841.93
   831.6 2854.68   845.9 2855.82   859.3 2862.22   957.2  2868.7   985.7 2872.51
#Mann= 8 ,-1,0
       0     .05       0    80.5    .016       0    93.7     .04       0
   222.2      .1       0   269.4    .045       0   320.7     .07       0
   700.3     .05       0   780.1      .1       0
#XS Ineff= 2 , 0
                           501.7         2838.49
Permanent Ineff=
       F       F
Bank Sta=269.4,320.7
XS Rating Curve= 0 ,0
Exp/Cntr=0.3,0.1

Type RM Length L Ch R = 1 ,25084   ,161,232,242.7
Node Name=I
XS GIS Cut Line= 3
2315278.41787713517917.445689251  2315423.165321518236.480871649
2315951.93659553518732.757822044
#Sta/Elev= 30
       0    2848    78.8 2844.27    91.9 2844.17   105.1 2844.21   135.9 2841.41
   153.4 2832.76   170.3  2830.4   233.8 2829.65   342.3 2829.26   416.6 2829.49
   442.1 2826.26   474.1 2825.76   481.7 2826.26   491.6 2830.31   596.8 2830.68
   626.1 2828.69   690.4 2832.81   761.9 2832.25   787.3  2833.1   813.1 2830.27
   850.9 2834.63   871.6 2833.75   911.3 2836.95   927.7 2841.05   974.1 2859.71
  1004.5 2860.98    1042 2879.16  1050.5 2880.99  1064.9 2881.46  1075.5 2888.03
#Mann= 13 ,-1,0
       0     .04       0    78.8     .05       0    91.9    .016       0
   105.1     .04       0   233.8     .05       0   342.3      .1       0
   442.1    .045       0   481.7     .05       0   761.9     .03       0
   871.6     .04       0   911.3     .05       0  1004.5      .1       0
  1050.5     .04       0
#XS Ineff= 2 , 0
                          598.97         2838.27
Permanent Ineff=
       F       F
#Block Obstruct= 2 ,-1
       0   13.26    2868  813.65  872.02 2853.74
Bank Sta=442.1,481.7
XS Rating Curve= 0 ,0
Exp/Cntr(USF)=0,0
Exp/Cntr=0.3,0.1

Type RM Length L Ch R = 1 ,24852   ,213.3,234.2,235.4
XS GIS Cut Line= 3
2315138.56995983517931.0056719262315421.69011991518742.444924387
 2315637.8890992518944.718609051
#Sta/Elev= 30
       0 2847.65   116.7 2841.61   134.9  2841.4   146.3  2835.8   159.1 2829.76
   192.9 2828.06   311.6 2824.81   434.4 2826.64   458.4 2828.54   472.6 2824.38
   510.7 2825.08   523.4 2823.54     540 2823.17   548.8 2823.63   565.8 2827.71
   595.4 2828.01   624.1 2826.17   726.7 2825.92   744.2 2823.79   764.9 2825.22
   777.6 2823.33   811.5 2825.47   832.7 2829.86   987.6 2840.41  1041.4 2847.66
  1103.7 2852.25  1109.3 2854.41  1120.3 2863.35  1144.4 2864.06  1155.5 2862.08
#Mann= 8 ,-1,0
       0     .04       0   116.7    .016       0   146.3     .06       0
   192.9      .1       0   523.4    .045       0   548.8      .1       0
  1120.3    .016       0  1144.4      .1       0
#XS Ineff= 2 , 0
           243.8    2828
Permanent Ineff=
       F       F
Bank Sta=523.4,548.8
XS Rating Curve= 0 ,0
Exp/Cntr=0.3,0.1

Type RM Length L Ch R = 1 ,24618   ,494.3,518.9,466.9
XS GIS Cut Line= 3
     2314992.901      518014.304     2315166.447      518878.064
     2315296.276        519115.2
#Sta/Elev= 30
       0 2843.44    83.4 2840.03   100.9 2839.93   129.4 2832.09   202.3 2828.39
   232.8 2828.95   288.5    2830   308.9  2820.1   321.2 2820.15   333.4 2823.04
   419.1 2822.35     430 2820.76   447.6  2818.9   478.42820.691   504.8 2822.78
   528.4  2821.1     576 2822.46   643.9 2818.39   659.8 2820.71   688.4 2818.61
   737.3 2821.72   765.9  2819.9   790.9 2821.54     823 2819.26   835.2 2822.98
   847.8 2836.41   855.6 2839.78   921.1 2845.91  1096.8 2861.44  1151.2 2870.53
#Mann= 9 ,-1,0
       0     .03       0    83.4    .016       0   100.9     .05       0
   202.3    .016       0   232.8     .05       0   321.2      .1       0
     430    .045       0   478.4      .1       0   921.1     .04       0
#XS Ineff= 1 ,-1
  349.05  408.95 2828.61
Permanent Ineff=
       F
#Block Obstruct= 3 ,-1
       0   42.73 2863.44  245.49  288.62 2849.96  992.28 1019.55 2873.64
Bank Sta=430,478.4
XS Rating Curve= 0 ,0
Exp/Cntr=0.3,0.1

Type RM Length L Ch R = 1 ,24099   ,446.7,411.9,406.1
XS GIS Cut Line= 2
      2314472.26      518214.347     2314898.841      519136.396
#Sta/Elev= 30
       0    2838     9.3 2837.73    51.6  2822.8    77.4 2818.31   149.7 2815.72
   232.3 2815.71     316 2812.42   342.3  2813.1   373.3 2811.37   395.4 2814.28
   426.2 2811.45     439 2814.12   457.1 2815.19   478.2 2814.79   490.9 2811.95
     523 2811.87   561.9 2811.03   568.6 2810.71   601.7 2812.43     629 2810.92
   642.2 2812.45   701.1 2813.72   721.5 2812.73   725.3 2814.05     748 2829.94
   761.4 2834.58   836.1 2838.63   881.9 2839.06   954.3 2843.32  1015.9 2852.91
#Mann= 9 ,-1,0
       0    .016       0     9.3      .1       0   232.3     .12       0
   342.3      .1       0   457.1     .12       0   490.9    .045       0
     523     .12       0   561.9      .1       0   881.9     .05       0
Bank Sta=490.9,523
XS Rating Curve= 0 ,0
Exp/Cntr=0.3,0.1

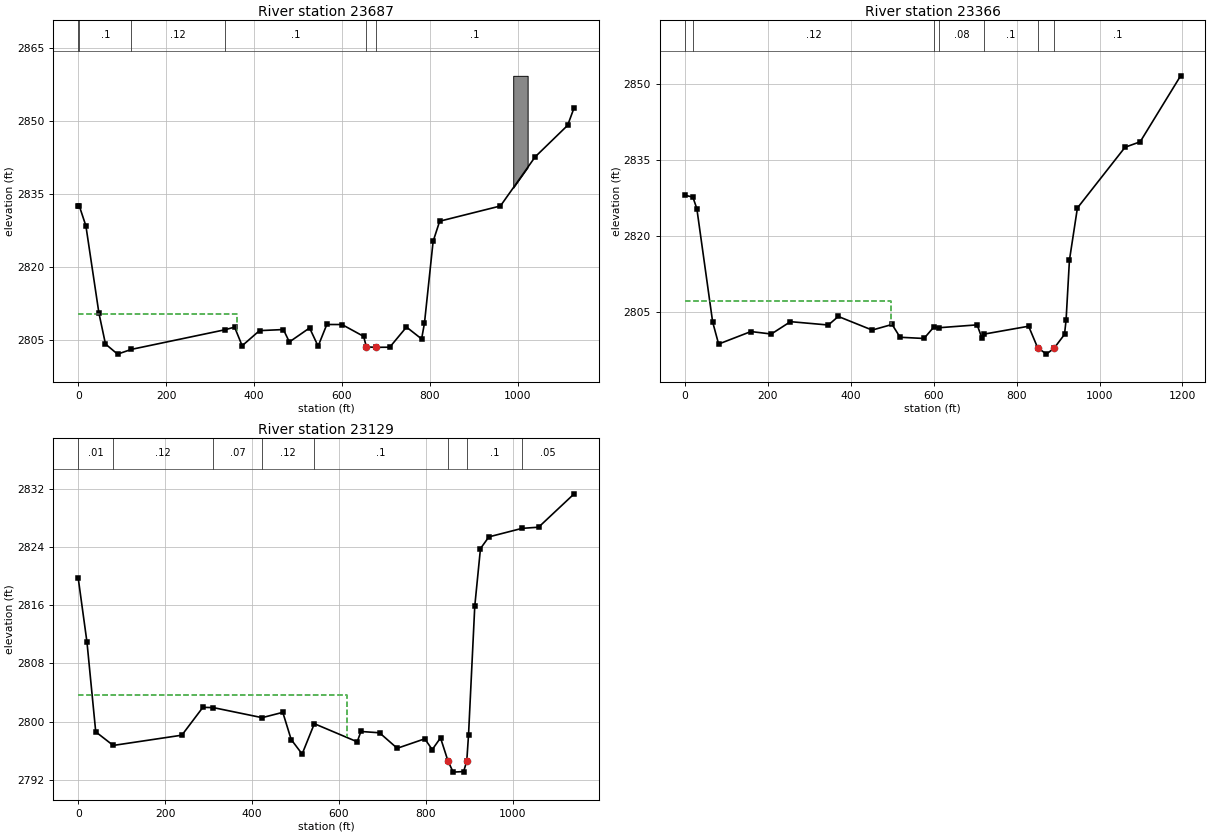
Type RM Length L Ch R = 1 ,23687   ,284.1,321.7,312.2
XS GIS Cut Line= 2
     2313931.749      518322.979     2314592.816       519237.08
#Sta/Elev= 30
       0 2832.48     2.7 2832.49    17.5 2828.45    47.1 2810.54      62 2804.19
    89.5 2802.11   121.2 2803.09   333.5 2807.11   355.7 2807.66   372.9 2803.83
   412.4 2806.94   466.7 2807.16   480.3 2804.61   526.3 2807.49   545.7 2803.75
   565.5  2808.2     600 2808.19   649.2 2805.76   655.5 2803.59   676.5 2803.51
   708.6 2803.53   746.7 2807.67   781.1 2805.23   787.6 2808.47   807.3 2825.28
   822.2 2829.42   960.4 2832.55  1039.4 2842.64  1113.3 2849.12  1128.1 2852.76
#Mann= 6 ,-1,0
       0    .016       0     2.7      .1       0   121.2     .12       0
   333.5      .1       0   655.5    .045       0   676.5      .1       0
#XS Ineff= 2 , 0
          360.14 2810.41
Permanent Ineff=
       F       F
#Block Obstruct= 1 ,-1
  989.49 1022.27 2859.29
Bank Sta=655.5,676.5
XS Rating Curve= 0 ,0
Exp/Cntr=0.3,0.1

Type RM Length L Ch R = 1 ,23366   ,274,237.2,237.1
XS GIS Cut Line= 3
2313691.13592708518412.798863748  2314228.969099519221.734935348
2314425.73733264519328.864306992
#Sta/Elev= 30
       0 2828.14    19.7 2827.76    29.3 2825.49    67.4 2803.11    81.8 2798.74
   159.7 2801.21   208.8 2800.72     255 2803.16   346.3  2802.5   370.3 2804.19
     452  2801.5     500 2802.61   519.2 2800.08   576.9 2799.84   600.9 2802.13
   612.7 2801.96     705 2802.53   716.2 2799.99   722.3 2800.71   829.1 2802.26
   850.7 2798.04   871.9 2796.75   890.5 2797.92   915.6 2800.64   919.4 2803.49
   927.5 2815.32   946.7 2825.61  1061.6 2837.61    1098 2838.68  1195.5 2851.71
#Mann= 7 ,-1,0
       0    .016       0    19.7     .12       0   600.9      .1       0
   612.7     .08       0   722.3      .1       0   850.7    .045       0
   890.5      .1       0
#XS Ineff= 2 , 0
          497.99 2807.34
Permanent Ineff=
       F       F
Bank Sta=850.7,890.5
XS Rating Curve= 0 ,0
Exp/Cntr(USF)=0,0
Exp/Cntr=0.3,0.1

Type RM Length L Ch R = 1 ,23129   ,413.9,472.8,485.2
XS GIS Cut Line= 2
     2313497.219       518564.09      2314139.74      519507.336
#Sta/Elev= 30
       0 2819.72    20.2 2810.89    40.3 2798.58    80.6 2796.71   238.5 2798.12
   286.9 2801.95   311.1 2801.91   423.2 2800.53   470.8 2801.26   490.1 2797.52
   515.3 2795.53   543.4  2799.7     642 2797.21   650.6 2798.63   693.4 2798.45
   734.1 2796.32   797.5 2797.62   814.7 2796.14   833.8 2797.75   850.8  2794.6
   862.8 2793.04     887 2793.12   894.22794.581   898.2 2798.13   912.6 2815.88
   925.7 2823.78   945.1 2825.39  1021.3 2826.56  1059.4 2826.72  1141.3 2831.31
#Mann= 8 ,-1,0
       0     .01       0    80.6     .12       0   311.1     .07       0
   423.2     .12       0   543.4      .1       0   850.8    .045       0
   894.2      .1       0  1021.3     .05       0
#XS Ineff= 2 , 0
          617.56 2803.66
Permanent Ineff=
       F       F
Bank Sta=850.8,894.2
XS Rating Curve= 0 ,0
Exp/Cntr=0.3,0.1