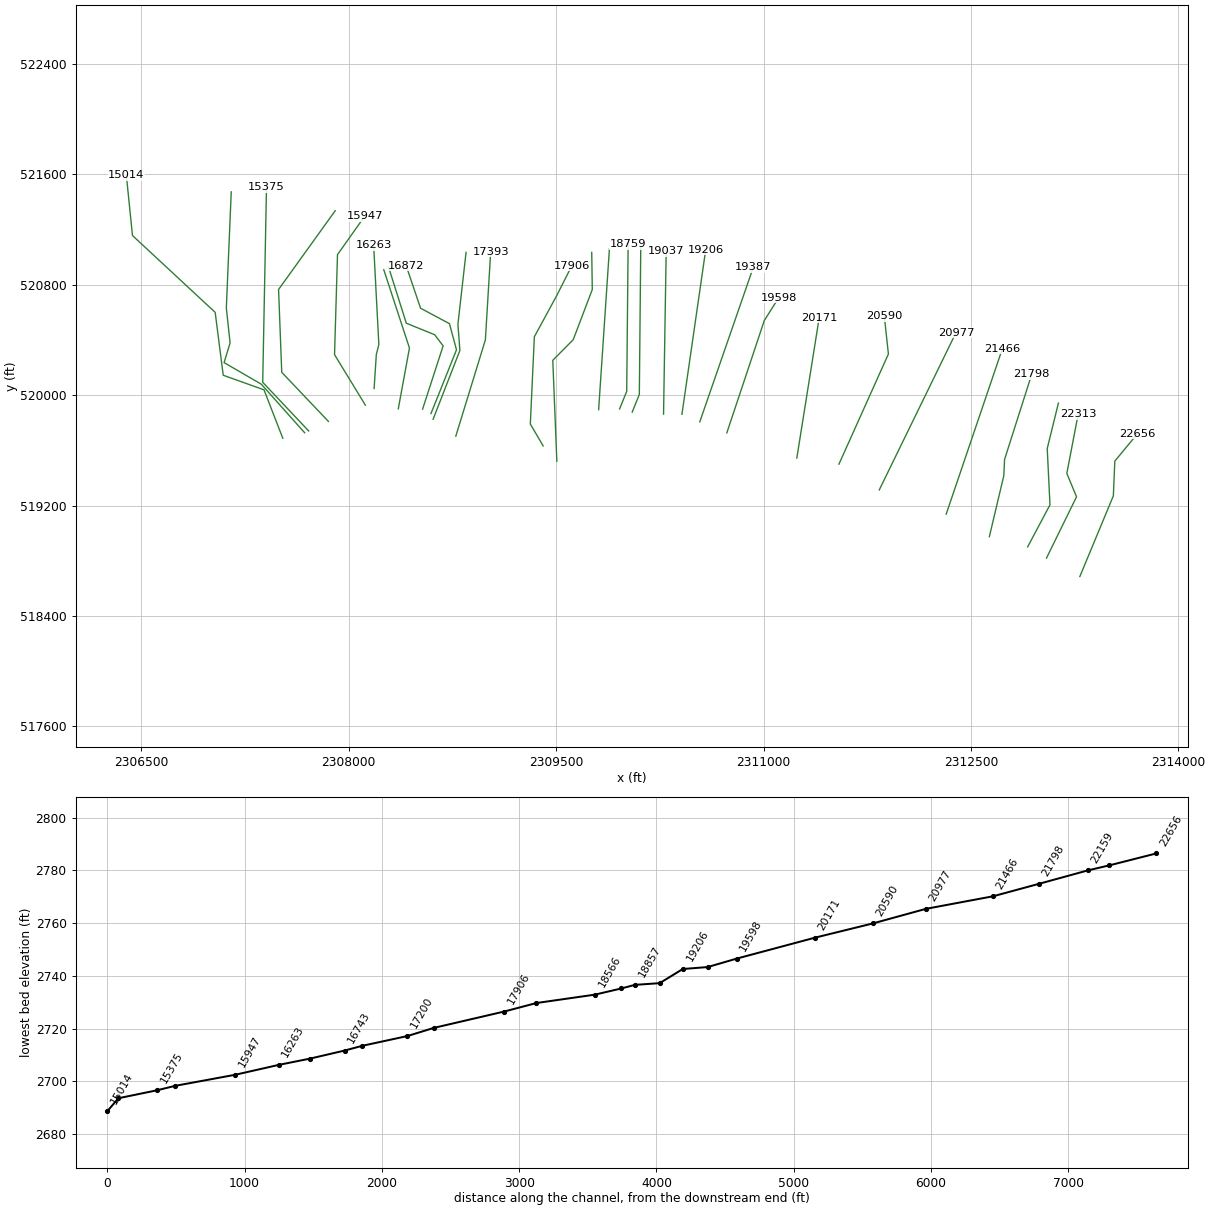
HEC-RAS study NRTHFRK.prj: NRTHFRK

--- NRTHFRK.g01 (geometry) --- (continued)

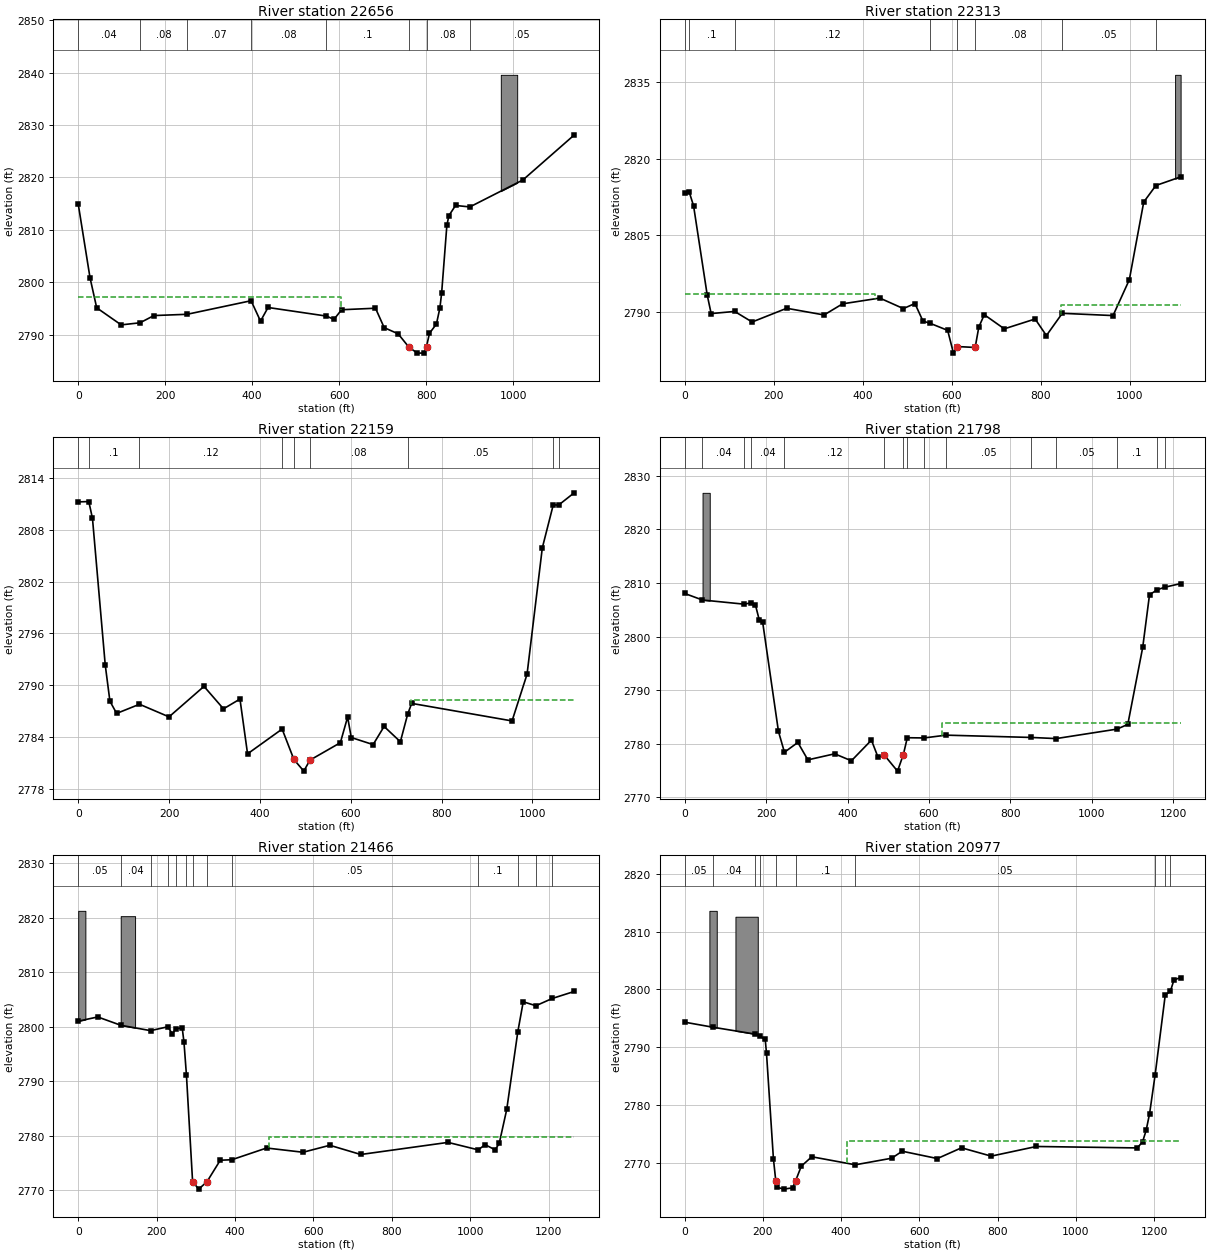
Type RM Length L Ch R = 1 ,22656   ,306.8,342.4,336.1
XS GIS Cut Line= 4
     2313287.904       518685.97     2313530.339        519270.2
     2313540.937      519521.909     2313703.886      519719.301
#Sta/Elev= 30
       0 2814.94    27.1 2800.88    42.5 2795.12    98.8 2791.86   142.1 2792.26
   174.1 2793.64   250.3 2793.88   397.5 2796.47   419.2 2792.58   436.5 2795.18
   570.8 2793.54   588.1 2792.91   605.6 2794.75   683.6 2795.04   703.6 2791.33
   735.6 2790.16   760.1 2787.64   779.6 2786.47   795.7 2786.49   800.9 2787.72
   807.7 2790.26   823.7 2792.02   831.7  2795.1   835.7 2797.95   847.7 2810.85
   852.3  2812.7   867.7 2814.65   900.5 2814.37  1022.6 2819.52  1140.4 2828.09
#Mann= 8 ,-1,0
       0     .04       0   142.1     .08       0   250.3     .07       0
   397.5     .08       0   570.8      .1       0   760.1    .045       0
   800.9     .08       0   900.5     .05       0
#XS Ineff= 2 , 0
           604.8 2797.25
Permanent Ineff=
       F       F
#Block Obstruct= 1 ,-1
  971.72 1009.42 2839.58
Bank Sta=760.1,800.9
XS Rating Curve= 0 ,0
Exp/Cntr=0.3,0.1

Type RM Length L Ch R = 1 ,22313   ,176.5,154.4,152.2
XS GIS Cut Line= 4
     2313046.793      518819.773     2313264.057      519263.576
     2313193.844      519433.148     2313275.981      519862.378
#Sta/Elev= 30
       0 2813.35    10.5 2813.44      20  2810.8    50.6 2793.35    59.5 2789.69
   112.3 2790.11   151.6 2788.04   229.3 2790.73   313.3 2789.42   354.9  2791.6
   438.6 2792.73   491.5 2790.67   517.5 2791.66   535.6 2788.22   552.1 2787.77
   591.1  2786.4   604.1 2781.94   612.8 2783.23   652.9 2783.05   661.1 2787.04
   673.4 2789.47   718.4  2786.7   787.7 2788.63     813 2785.38   848.7 2789.74
   962.8  2789.3   999.4 2796.32  1031.8 2811.55  1059.1 2814.79  1114.7 2816.48
#Mann= 8 ,-1,0
       0    .016       0    10.5      .1       0   112.3     .12       0
   552.1     .08       0   612.8    .045       0   652.9     .08       0
   848.7     .05       0  1059.1     .04       0
#XS Ineff= 2 , 0
           427.5 2793.51   846.8         2791.44
Permanent Ineff=
       F       F
#Block Obstruct= 1 ,-1
 1102.31 1114.68 2836.48
Bank Sta=612.8,652.9
XS Rating Curve= 0 ,0
Exp/Cntr=0.3,0.1

Type RM Length L Ch R = 1 ,22159   ,379.1,360.5,314.9
Node Name=H
XS GIS Cut Line= 4
      2312910.34      518900.585     2313071.964      519205.285
     2313052.092      519613.319     2313132.904      519941.865
#Sta/Elev= 30
       0 2811.22    23.3 2811.26    31.4 2809.31    59.5 2792.34    69.8 2788.15
    84.6 2786.74   134.9  2787.8   199.9 2786.34   276.9 2789.87   319.8 2787.27
   356.1  2788.4   372.8 2782.06   448.9 2784.93   474.8 2781.41   496.6 2780.06
   510.1 2781.33   577.1 2783.35   593.1 2786.32   601.1 2783.95   649.2 2783.13
   673.4 2785.23   709.2 2783.46   725.3 2786.65   734.1  2787.9   955.1 2785.87
   988.1 2791.27  1021.7  2805.9  1045.8 2810.88  1057.5 2810.85  1091.8 2812.27
#Mann= 9 ,-1,0
       0    .016       0    23.3      .1       0   134.9     .12       0
   448.9     .08       0   474.8    .045       0   510.1     .08       0
   725.3     .05       0  1045.8    .016       0  1057.5      .1       0
#XS Ineff= 2 , 0
                           732.6         2788.33
Permanent Ineff=
       F       F
Bank Sta=474.8,510.1
XS Rating Curve= 0 ,0
Exp/Cntr=0.3,0.1

Type RM Length L Ch R = 1 ,21798   ,333.7,332.2,300.5
XS GIS Cut Line= 4
      2312633.46      518974.773     2312738.118      519417.251
     2312743.417      519533.832     2312939.485      520149.856
#Sta/Elev= 30
       0 2808.05    43.6 2806.83   146.3 2806.05   162.8  2806.3   173.8 2805.88
   183.3 2803.07   191.5 2802.69   230.3 2782.31     245 2778.43   277.9 2780.26
   302.5 2777.01   368.3 2778.14   409.4 2776.84   458.6 2780.69   474.6 2777.55
   490.7 2777.86   522.7 2774.91     537    2778   546.7 2781.14   587.7  2781.1
   642.1 2781.62   851.7 2781.19   912.2 2780.98  1061.8 2782.75  1088.2 2783.63
  1124.8 2797.99  1141.5 2807.81  1160.6 2808.74  1178.8 2809.21  1217.9 2809.89
#Mann= 15 ,-1,0
       0     .05       0    43.6     .04       0   146.3    .016       0
   162.8     .04       0     245     .12       0   490.7    .045       0
     537     .12       0   546.7     .05       0   587.7     .08       0
   642.1     .05       0   851.7     .03       0   912.2     .05       0
  1061.8      .1       0  1160.6    .016       0  1178.8     .04       0
#XS Ineff= 2 , 0
                           631.8         2783.95
Permanent Ineff=
       F       F
#Block Obstruct= 1 ,-1
   43.86   61.54 2826.82
Bank Sta=490.7,537
XS Rating Curve= 0 ,0
Exp/Cntr=0.3,0.1

Type RM Length L Ch R = 1 ,21466   ,494.6,489.5,483.1
XS GIS Cut Line= 2
     2312321.253      519138.016      2312727.52      520336.209
#Sta/Elev= 30
       0 2801.01    49.8 2801.78   108.9 2800.25   184.6 2799.27   228.7 2799.98
   239.9 2798.67   248.3 2799.54   265.2 2799.84   269.8 2797.16   276.1 2791.12
   291.8 2771.59   307.4 2770.21   328.6 2771.58   362.4 2775.51   391.9  2775.6
   480.6 2777.75   573.5 2776.97   641.9 2778.25   720.8 2776.56   943.4 2778.78
  1020.4 2777.41  1038.1 2778.36  1063.5 2777.42    1074 2778.58  1093.2 2784.82
  1121.4 2799.04  1135.3 2804.56  1167.6 2803.84  1209.7 2805.18  1265.2 2806.45
#Mann= 13 ,-1,0
       0     .05       0   108.9     .04       0   184.6     .05       0
   228.7    .016       0   248.3     .05       0   276.1      .1       0
   291.8    .045       0   328.6      .1       0   391.9     .05       0
  1020.4      .1       0  1121.4     .04       0  1167.6    .016       0
  1209.7      .1       0
#XS Ineff= 2 , 0
                           487.5         2779.74
Permanent Ineff=
       F       F
#Block Obstruct= 2 ,-1
       0   18.29 2821.24  108.41   145.1 2820.26
Bank Sta=291.8,328.6
XS Rating Curve= 0 ,0
Exp/Cntr=0.3,0.1

Type RM Length L Ch R = 1 ,20977   ,376.6,386.8,477.9
XS GIS Cut Line= 2
     2311836.971      519313.181     2312391.908      520452.496
#Sta/Elev= 30
       0 2794.33    71.2 2793.47   178.9 2792.28   191.3 2791.92   205.8 2791.36
   209.1 2788.93   226.8 2770.67   232.8 2766.86   235.7 2765.76   253.6 2765.44
   275.9 2765.67   283.6 2766.91   298.1 2769.42   324.8 2771.04     436 2769.65
     529 2770.79   555.9    2772   645.7 2770.73   707.4 2772.59   783.3 2771.15
   898.7 2772.82  1156.8 2772.57  1170.2 2773.65  1179.1 2775.59    1188  2778.5
  1202.2 2785.24    1228 2799.02  1241.3  2799.7  1250.2 2801.63  1267.3 2802.06
#Mann= 10 ,-1,0
       0     .05       0    71.2     .04       0   178.9    .016       0
   191.3     .04       0   232.8    .045       0   283.6      .1       0
     436     .05       0  1202.2     .04       0    1228    .016       0
  1241.3     .04       0
#XS Ineff= 2 , 0
                           415.4         2773.71
Permanent Ineff=
       F       F
#Block Obstruct= 2 ,-1
   63.15   81.94  2813.6  129.73  186.75 2812.58
Bank Sta=232.8,283.6
XS Rating Curve= 0 ,0
Exp/Cntr=0.3,0.1

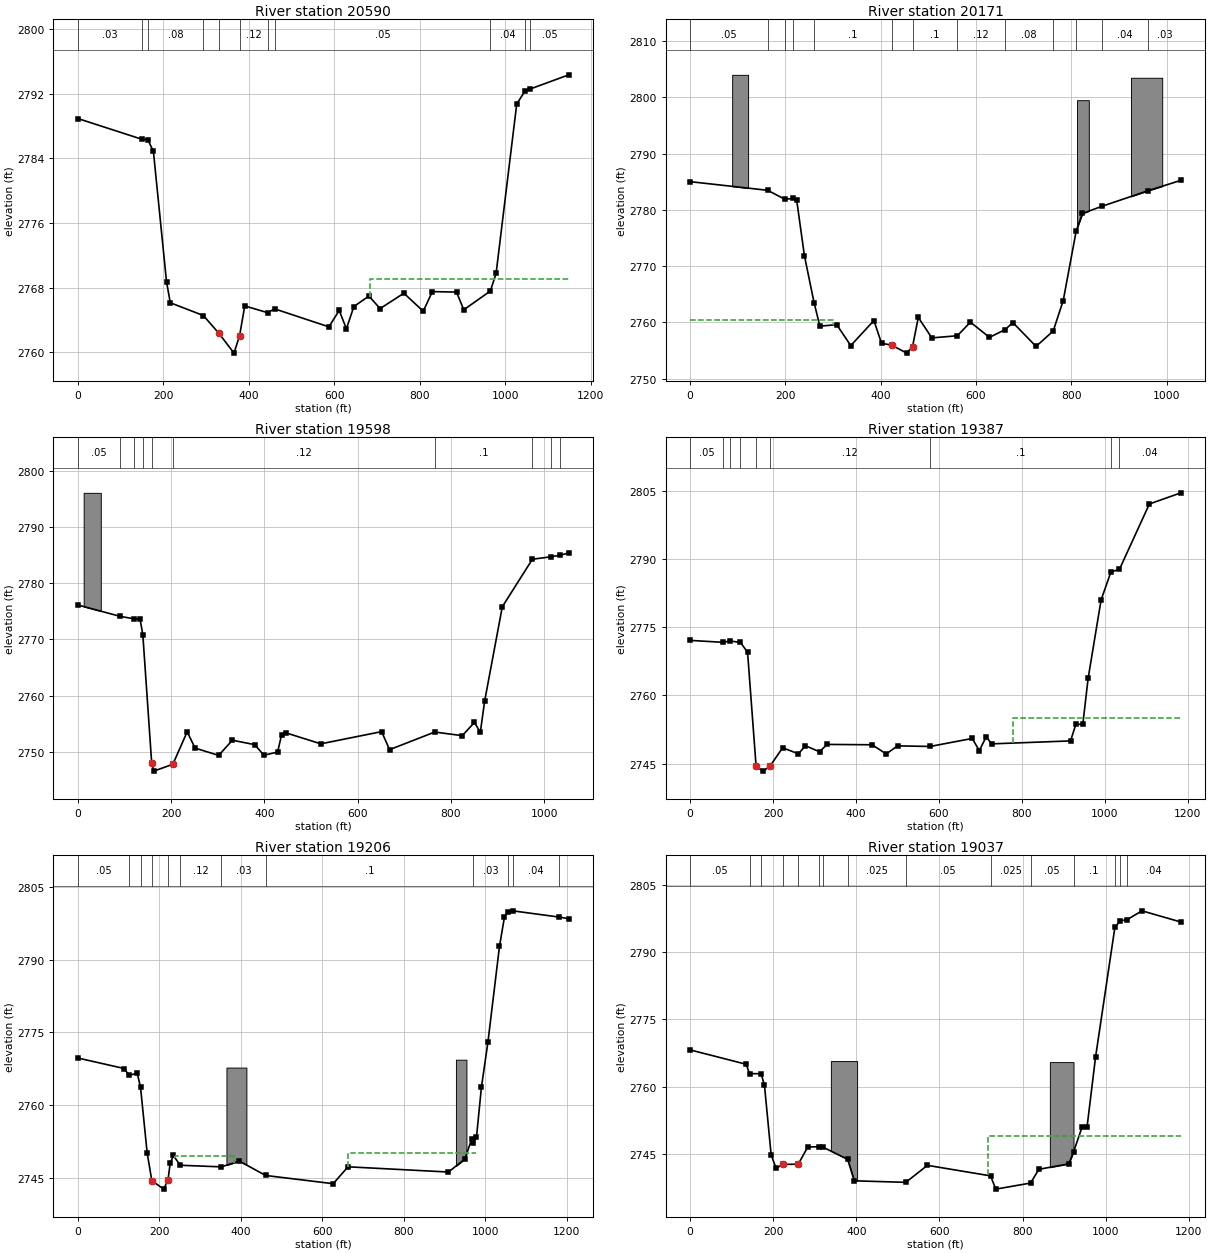
Type RM Length L Ch R = 1 ,20590   ,390.4,419.3,487.3
XS GIS Cut Line= 3
     2311545.518      519500.123      2311903.21      520297.938
      2311873.77      520570.254
#Sta/Elev= 30
       0 2788.91   150.2 2786.34   163.4 2786.31   176.5 2784.84   207.2 2768.72
     216 2766.13   293.4 2764.55   329.9 2762.34     365  2759.9   378.1 2762.05
   390.2 2765.74   443.9  2764.9   459.8 2765.38     587 2763.15   611.2 2765.18
     628 2762.91   645.5 2765.66   680.6 2766.96   706.9 2765.41   762.5 2767.31
   807.7 2765.08   829.1 2767.51   885.6 2767.45   902.6 2765.26   964.8 2767.58
   978.2 2769.76  1026.5 2790.72    1046 2792.33  1058.6 2792.58  1148.2 2794.32
#Mann= 11 ,-1,0
       0     .03       0   150.2    .016       0   163.4     .08       0
   293.4      .1       0   329.9    .045       0   378.1     .12       0
   443.9      .1       0   459.8     .05       0   964.8     .04       0
    1046    .016       0  1058.6     .05       0
#XS Ineff= 2 , 0
                           683.2          2769.1
Permanent Ineff=
       F       F
Bank Sta=329.9,378.1
XS Rating Curve= 0 ,0
Exp/Cntr=0.3,0.1

Type RM Length L Ch R = 1 ,20171   ,513.1,573.1,476.4
XS GIS Cut Line= 2
     2311240.818      519544.283     2311402.736      520561.422
#Sta/Elev= 30
       0 2785.03   162.9 2783.49   199.4 2781.87   215.6 2782.07   223.7 2781.73
   239.9 2771.86   260.1 2763.53   272.3 2759.33   307.7 2759.59   337.1 2755.87
   385.7 2760.33   401.7 2756.28   423.12755.956   454.5 2754.53   466.72755.664
   478.8 2760.88   507.2 2757.24   560.7 2757.62   588.2 2760.04   628.1 2757.33
   660.6  2758.7   677.3 2759.96   725.9 2755.72   761.9 2758.47   782.9 2763.89
   810.1 2776.27   823.1 2779.37   863.3 2780.62   960.5 2783.41  1029.7 2785.26
#Mann= 13 ,-1,0
       0     .05       0   162.9     .04       0   199.4    .016       0
   215.6     .04       0   260.1      .1       0   423.1    .045       0
   466.7      .1       0   560.7     .12       0   660.6     .08       0
   761.9      .1       0   810.1     .05       0   863.3     .04       0
   960.5     .03       0
#XS Ineff= 2 , 0
           300.6  2760.5
Permanent Ineff=
       F       F
#Block Obstruct= 3 ,-1
   88.32  121.76 2804.03  811.81  836.57 2799.52  925.03  990.54 2803.51
Bank Sta=423.1,466.7
XS Rating Curve= 0 ,0
Exp/Cntr=0.3,0.1

Type RM Length L Ch R = 1 ,19598   ,210.5,210.7,210.4
Node Name=G
XS GIS Cut Line= 4
     2310734.456      519726.808     2310874.294      520146.323
2311005.10076714520539.4393445572311109.62693535520705.878210672
#Sta/Elev= 30
       0 2776.12      91 2774.09   120.6 2773.66   133.2 2773.62   139.2 2770.83
   158.22748.001   162.7 2746.55   203.62747.772   234.4 2753.55   251.3 2750.65
   301.9 2749.35   331.4 2752.05   379.5 2751.26   398.8 2749.38   428.4 2749.94
   436.8 2752.99     446 2753.37   521.1 2751.41   651.6 2753.58   668.6 2750.37
   765.6 2753.51   824.6 2752.86   850.8 2755.23   863.3 2753.45   872.7 2759.06
   910.5 2775.81   975.1 2784.27  1014.4  2784.7  1034.1 2784.98  1053.1 2785.38
#Mann= 10 ,-1,0
       0     .05       0      91     .04       0   120.6    .016       0
   139.2     .04       0   158.2    .045       0   203.6     .12       0
   765.6      .1       0   975.1     .04       0  1014.4    .016       0
  1034.1     .04       0
#Block Obstruct= 1 ,-1
   12.24   48.98 2796.09
Bank Sta=158.2,203.6
XS Rating Curve= 0 ,0
Exp/Cntr=0.3,0.1

Type RM Length L Ch R = 1 ,19387   ,175.9,180.7,264.7
XS GIS Cut Line= 2
2310538.76050091519806.344438066 2310925.4383901  520924.4741669
#Sta/Elev= 30
       0 2772.08    79.2 2771.65    96.1 2771.95   121.5 2771.63   138.6 2769.46
   159.22744.373   176.3 2743.35   192.32744.394   223.1 2748.48   261.2 2747.16
   278.1 2748.93     312 2747.61   330.4 2749.22   438.9 2749.14   472.8 2747.13
   500.2  2748.9   578.6 2748.77   680.2 2750.53   697.1 2747.86     714  2750.9
   726.7 2749.34   917.2 2749.99   929.9 2753.63   946.7 2753.65   959.5 2763.71
   990.8 2780.98  1014.6 2787.14  1034.9 2787.67  1107.2 2802.05  1183.1  2804.5
#Mann= 9 ,-1,0
       0     .05       0    79.2      .1       0    96.1    .016       0
   121.5     .04       0   159.2    .045       0   192.3     .12       0
   578.6      .1       0  1014.6    .016       0  1034.9     .04       0
#XS Ineff= 2 , 0
                          779.49         2754.95
Permanent Ineff=
       F       F
#Block Obstruct= 2 , 0
           21.58 2792.08
Bank Sta=159.2,192.3
XS Rating Curve= 0 ,0
Exp/Cntr=0.3,0.1

Type RM Length L Ch R = 1 ,19206   ,159.4,168.8,241.4
XS GIS Cut Line= 2
2310409.72378732519861.1591879682310581.80608438521053.385026189
#Sta/Elev= 30
       0 2769.69   113.2 2767.53   125.3 2766.12   145.5 2766.56   153.6 2763.64
   169.8 2750.14   181.3 2744.36   210.6 2742.62   221.1 2744.58   226.3 2747.95
   234.4 2749.57   250.6 2747.55   351.8 2747.22   396.1 2748.41   460.7 2745.44
   626.4 2743.74   662.8 2747.23   909.3 2746.15   949.8 2748.85   965.9  2752.9
     970 2752.13   978.1 2753.32   990.2 2763.64  1006.3 2773.04  1034.6 2792.78
  1046.8 2798.82  1054.6  2799.9    1067 2800.09  1180.1 2798.81  1204.6 2798.46
#Mann= 12 ,-1,0
       0     .05       0   125.3    .016       0   153.6     .04       0
   181.3    .045       0   221.1     .04       0   250.6     .12       0
   351.8     .03       0   460.7      .1       0     970     .03       0
  1054.6    .016       0    1067     .04       0  1180.1     .05       0
#XS Ineff= 2 ,-1
   238.5     384 2749.56  662.82   976.2    2750
Permanent Ineff=
       F       F
#Block Obstruct= 2 ,-1
  364.44  413.41 2767.72  927.66  953.46 2769.35
Bank Sta=181.3,221.1
XS Rating Curve= 0 ,0
Exp/Cntr(USF)=0,0
Exp/Cntr=0.3,0.1

Type RM Length L Ch R = 1 ,19037   ,178.4,180.3,184.8
XS GIS Cut Line= 2
      2310276.67      519862.231     2310295.805      521042.761
#Sta/Elev= 30
       0 2768.23     135 2765.03     143 2762.95     171 2762.92     179 2760.32
     195  2744.9     207 2741.87     223 2742.75  260.33  2742.8     283 2746.62
   309.5 2746.69     319 2746.62     379 2743.89     395  2739.1     519 2738.76
     571 2742.54   722.8  2740.2   735.5 2737.25   819.1  2738.6   839.1 2741.66
   911.1 2742.88   922.5 2745.53   942.8 2750.98   955.1 2751.16   975.4  2766.6
    1022 2795.52  1035.1 2796.95  1051.1  2797.2  1087.1 2799.17  1180.7 2796.68
#Mann= 15 ,-1,0
       0     .05       0     143    .016       0     171     .04       0
     223    .045       0  260.33     .05       0   309.5    .016       0
     319     .05       0     379    .025       0     519     .05       0
   722.8    .025       0   819.1     .05       0   922.5      .1       0
    1022     .04       0  1035.1    .016       0  1051.1     .04       0
#XS Ineff= 2 , 0
                          715.61         2749.12
Permanent Ineff=
       F       F
#Block Obstruct= 2 ,-1
  338.72  401.87 2765.74  865.52  922.43 2765.51
Bank Sta=223,260.33
XS Rating Curve= 0 ,0
Exp/Cntr=0.5,0.3

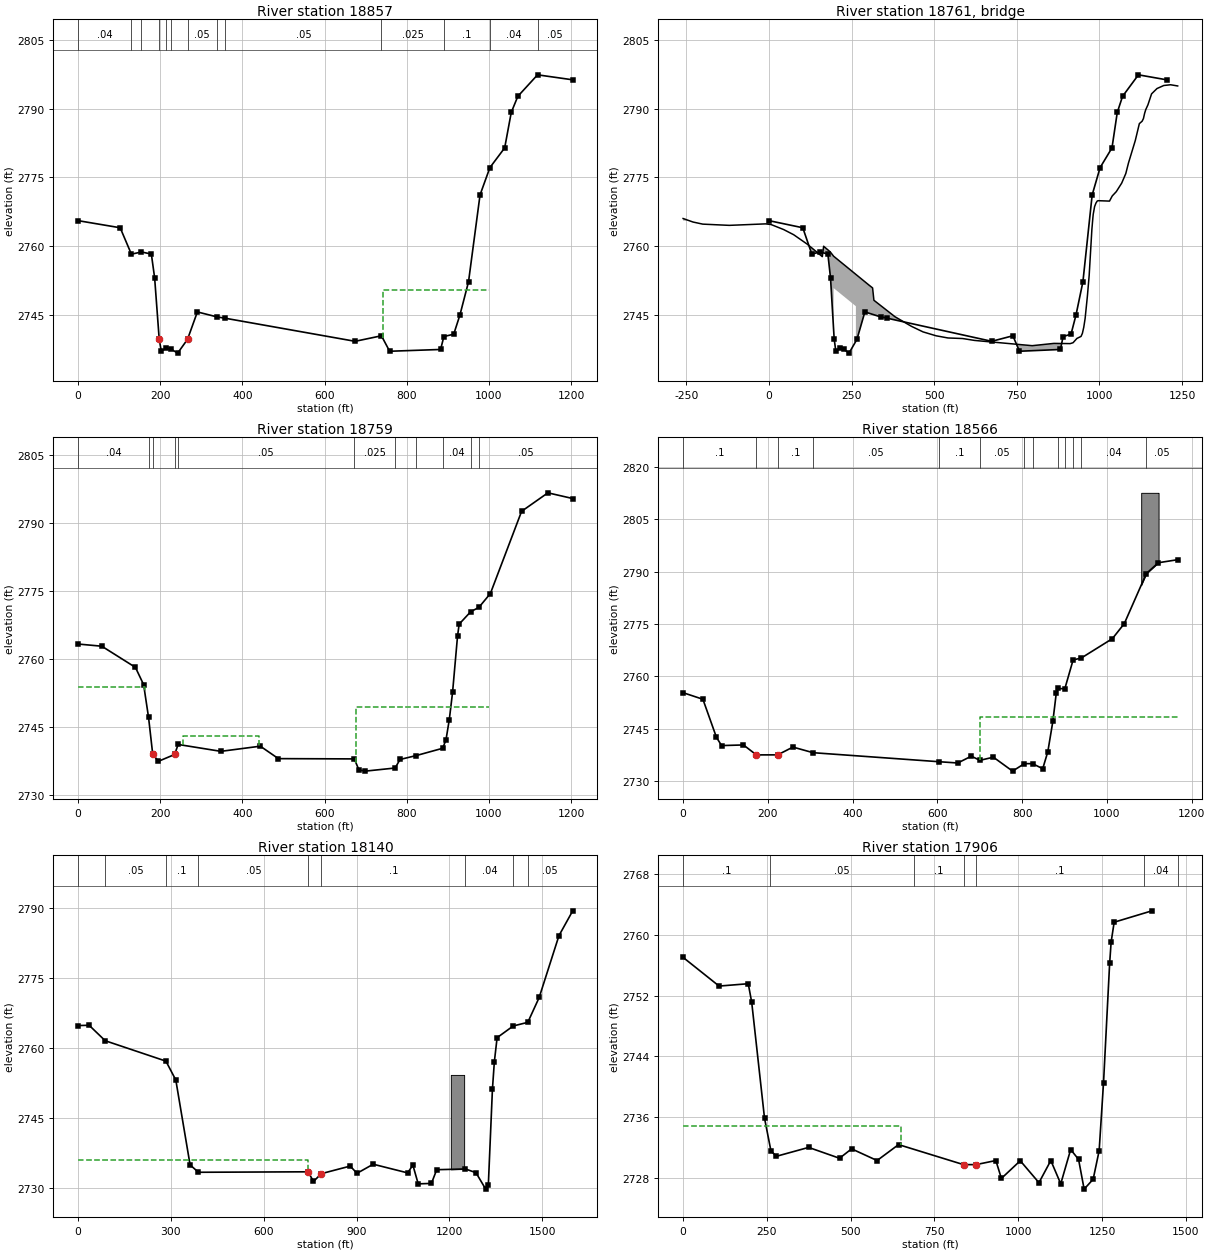
Type RM Length L Ch R = 1 ,18857   ,92,97.8,91.6
BEGIN DESCRIPTION:
Merged US Survey NOR052BU
END DESCRIPTION:
XS GIS Cut Line= 3
     2310049.984      519876.951     2310101.504      520005.013
     2310111.808      521070.728
#Sta/Elev= 30
       0 2765.54   102.3 2763.99   129.6 2758.22   154.2  2758.7   178.2 2758.24
   186.2 2753.03  197.27 2739.69   202.2 2737.07   214.2 2737.62   226.2 2737.48
   242.2  2736.6   266.2 2739.61   290.2  2745.6   338.2 2744.51   358.2 2744.22
   674.2 2739.18   738.2 2740.39   758.2 2737.01   882.2  2737.4   890.2 2740.22
   914.2 2740.74   929.3 2744.94   950.2 2752.19   978.2 2771.16  1002.2 2777.13
  1038.2 2781.44  1054.2 2789.19  1070.2  2792.7  1118.2  2797.4  1203.8 2796.31
#Mann= 13 ,-1,0
       0     .04       0   129.6    .016       0   154.2     .04       0
  197.27    .045       0   214.2     .05       0   226.2    .045       0
   266.2     .05       0   338.2    .016       0   358.2     .05       0
   738.2    .025       0   890.2      .1       0  1002.2     .04       0
  1118.2     .05       0
#XS Ineff= 3 ,-1
       0  155.65  2753.8  293.24  430.242742.677  741.35    10002750.348
Permanent Ineff=
       F       F       F
Bank Sta=197.27,266.2
XS Rating Curve= 0 ,0
Exp/Cntr=0.5,0.3

Type RM Length L Ch R = 3 ,18761   ,,,
BEGIN DESCRIPTION:
North Fork Road.
Bridge 54075NOR050
Merged Survey NOR048-052: 2.5' high railing (extends 90' LOB, 60' ROB from aerial imagery).
From photographs: shallow flows with cobbled channel below.
END DESCRIPTION:
Bridge Culvert--1,0,-1,-1, 0
Deck Dist Width WeirC Skew NumUp NumDn MinLoCord MaxHiCord MaxSubmerge Is_Ogee
34.08172,26,2.6,0, 60, 60, , , 0.98, 0, 0,0,,
    -260-230.006-200.427-120.241 -10.475   6.412  44.407  74.646 116.177 161.386
  165.39 185.414  195.65     263 301.552 313.567 317.572  381.33 430.967 466.208
 505.796 541.696 585.891 621.879 796.669 862.364 911.636 920.346 932.165 944.483
 948.589 952.695 956.801 963.683 969.119 977.331 980.351 981.437 985.543 989.648
 993.686 997.0191030.708 1038.921051.2381067.6611079.9791088.1911108.7211121.039
 1129.251133.3561137.0321140.3661147.0331157.9921174.4161194.9451215.4751237.041
2766.0072765.2412764.7812764.5132764.8382764.6882763.594 2762.472760.3852757.675
2759.9482758.7112757.769  2753.82751.5282750.8442748.1472744.5492742.4622741.241
2740.3872739.9122739.7912739.3772738.2282738.7252738.679 2738.872739.8182740.249
2740.9122742.2232744.1262748.993 2753.562763.6352766.1542766.9462768.6122769.383
2769.8422769.9022769.8142770.933 2771.882773.7532775.828 2778.162783.0452786.743
2787.2512787.8352789.004 2789.792790.8522793.2412794.4042795.0672795.2312794.969
                                                                                
                 2750.81 2746.85
                                                                                
                                                                                
                                                                                
                                                                                
    -280-250.006-220.427-140.241 -30.475 -13.588  24.407  54.646  96.177 141.386
  145.39 165.414  175.65     243 281.552 293.567 297.572  361.33 410.967 446.208
 485.796 521.696 565.891 601.879 776.669 842.364 891.636 900.346 912.165 924.483
 928.589 932.695 936.801 943.683 949.119 957.331 960.351 961.437 965.543 969.648
 973.686 977.0191010.708 1018.921031.2381047.6611059.9791068.1911088.7211101.039
 1109.251113.3561117.0321120.3661127.0331137.9921154.4161174.9451195.4751217.041
2766.0072765.2412764.7812764.5132764.8382764.6882763.594 2762.472760.3852757.675
2759.9482758.7112757.769  2753.82751.5282750.8442748.1472744.5492742.4622741.241
2740.3872739.9122739.7912739.3772738.2282738.7252738.679 2738.872739.8182740.249
2740.9122742.2232744.1262748.993 2753.562763.6352766.1542766.9462768.6122769.383
2769.8422769.9022769.8142770.933 2771.882773.7532775.828 2778.162783.0452786.743
2787.2512787.8352789.004 2789.792790.8522793.2412794.4042795.0672795.2312794.969
                                                                                
                 2750.81 2746.85
                                                                                
                                                                                
                                                                                
                                                                                
BR Coef=-1 ,-1 , 0 ,, 0 ,,,0.8,0,1.2,0,
WSPro=,,,, 1 ,,,, 0 ,,,, 0 ,,,,-1 ,-1 ,-1 , 0 , 0 , 0 , 0 , 0
BR U #Sta/Elev= 30
       0 2765.54   102.3 2763.99   129.6 2758.22   154.2  2758.7   178.2 2758.24
   186.2 2753.03  197.27 2739.69   202.2 2737.07   214.2 2737.62   226.2 2737.48
   242.2  2736.6   266.2 2739.61   290.2  2745.6   338.2 2744.51   358.2 2744.22
   674.2 2739.18   738.2 2740.39   758.2 2737.01   882.2  2737.4   890.2 2740.22
   914.2 2740.74   929.3 2744.94   950.2 2752.19   978.2 2771.16  1002.2 2777.13
  1038.2 2781.44  1054.2 2789.19  1070.2  2792.7  1118.2  2797.4  1203.8 2796.31
BR U #Mann= 13
       0     .04   129.6    .016   154.2     .04  197.27     .04   214.2     .05
   226.2     .04   266.2     .05   338.2    .016   358.2     .05   738.2    .025
   890.2      .1  1002.2     .04  1118.2     .05
BR D #Sta/Elev= 30
       0 2763.32    57.6 2762.84   139.4 2758.17   159.4 2754.35   171.4  2747.1
   181.5 2738.99  195.33 2737.42   234.82738.923   243.4 2741.14   347.4 2739.62
   443.4 2740.76   487.4 2738.01   672.2 2737.95   683.4 2735.52   698.9 2735.25
   771.6 2735.94   783.4 2737.82   823.4  2738.7   887.4  2740.3   895.4  2742.2
   903.4 2746.63   911.4  2752.7   923.4 2765.03   927.4 2767.72   955.4 2770.45
   975.4 2771.42  1003.4 2774.48  1079.4 2792.64  1143.4 2796.72  1203.8 2795.46
BR D #Mann= 11
       0     .04   171.4      .1   181.5     .04   234.8      .1   243.4     .05
   672.2    .025   771.6     .04   823.4    .016   887.4     .04   955.4    .016
   975.4     .05
BC Design=,, 0 ,, 0 ,,,,,,
BC Use User HTab Curves=0
BC User HTab FreeFlow(D)= 0

Type RM Length L Ch R = 1 ,18759   ,194,193.4,166.9
BEGIN DESCRIPTION:
Merged DS Survey NOR048BD
END DESCRIPTION:
XS GIS Cut Line= 3
     2309958.721      519899.766     2310010.241      520027.829
     2310020.545      521093.544
#Sta/Elev= 30
       0 2763.32    57.6 2762.84   139.4 2758.17   159.4 2754.35   171.4  2747.1
   181.5 2738.99  195.33 2737.42   234.82738.923   243.4 2741.14   347.4 2739.62
   443.4 2740.76   487.4 2738.01   672.2 2737.95   683.4 2735.52   698.9 2735.25
   771.6 2735.94   783.4 2737.82   823.4  2738.7   887.4  2740.3   895.4  2742.2
   903.4 2746.63   911.4  2752.7   923.4 2765.03   927.4 2767.72   955.4 2770.45
   975.4 2771.42  1003.4 2774.48  1079.4 2792.64  1143.4 2796.72  1203.8 2795.46
#Mann= 11 ,-1,0
       0     .04       0   171.4      .1       0   181.5    .045       0
   234.8      .1       0   243.4     .05       0   672.2    .025       0
   771.6     .04       0   823.4    .016       0   887.4     .04       0
   955.4    .016       0   975.4     .05       0
#XS Ineff= 3 ,-1
       0 162.317  2753.8 256.333     440    2743  675.88    10002749.351
Permanent Ineff=
       F       F       F
Bank Sta=181.5,234.8
XS Rating Curve= 0 ,0
Exp/Cntr=0.5,0.3

Type RM Length L Ch R = 1 ,18566   ,389.8,426.3,181.5
XS GIS Cut Line= 2
     2309807.107      519894.614     2309885.122      521058.952
#Sta/Elev= 30
       0 2755.36    46.7 2753.48    78.7 2742.56    90.8 2740.21   142.4 2740.39
  172.84 2737.54   223.1 2737.55   259.1 2739.78   306.7 2738.17   603.2 2735.59
     648 2735.22   680.1 2737.18   700.1 2735.98   732.1 2736.88   777.4 2732.89
   805.1 2735.03   824.4 2735.03   848.5 2733.59   860.5 2738.45   872.5 2747.23
   880.5 2755.28   884.5 2756.57   900.6 2756.48   920.2 2764.76     939 2765.26
  1012.8 2770.84  1040.9 2775.14  1092.9 2789.49  1121.1 2792.59  1166.9 2793.46
#Mann= 13 ,-1,0
       0      .1       0  172.84    .045       0   223.1      .1       0
   306.7     .05       0   603.2      .1       0   700.1     .05       0
   805.1    .016       0   824.4     .04       0   884.5    .016       0
   900.6     .04       0   920.2    .016       0     939     .04       0
  1092.9     .05       0
#XS Ineff= 2 , 0
                          701.66         2748.29
Permanent Ineff=
       F       F
#Block Obstruct= 1 ,-1
  1080.8 1121.81 2812.62
Bank Sta=172.84,223.1
XS Rating Curve= 0 ,0
Exp/Cntr=0.3,0.1

Type RM Length L Ch R = 1 ,18140   ,170.2,234,244.9
XS GIS Cut Line= 5
2309504.78219039519521.7040569772309475.43048972520252.097233113
2309623.38274962520401.595041228     2309761.232      520765.077
     2309757.193      521033.628
#Sta/Elev= 30
       0 2764.84    35.5  2764.9    87.5 2761.58   283.7  2757.2   315.7 2753.14
   361.8 2734.92   388.8 2733.33   743.6 2733.43   760.6 2731.35     786 2733.03
   879.4 2734.66   901.3 2733.11   953.7 2735.06  1064.9  2733.2    1082 2734.86
  1099.2 2730.84  1141.9 2730.94    1159 2733.88  1251.8 2734.04  1285.9 2733.24
  1317.3 2729.71  1325.9 2730.68  1339.1 2751.19  1345.3 2757.06  1354.2 2762.24
  1406.3 2764.75  1453.4 2765.53  1490.2 2770.87  1554.2 2784.16  1598.6 2789.48
#Mann= 9 ,-1,0
       0      .1       0    87.5     .05       0   283.7      .1       0
   388.8     .05       0   743.6    .045       0     786      .1       0
  1251.8     .04       0  1406.3    .016       0  1453.4     .05       0
#XS Ineff= 2 , 0
          741.54 2735.97
Permanent Ineff=
       F       F
#Block Obstruct= 1 ,-1
 1204.64 1247.65 2754.24
Bank Sta=743.6,786
XS Rating Curve= 0 ,0
Exp/Cntr=0.3,0.1

Type RM Length L Ch R = 1 ,17906   ,361.7,512.7,477.2
XS GIS Cut Line= 5
2309405.78257617519631.8752342362309313.00853614519790.665405373
 2309342.1488661520422.6463114482309506.29297443520725.287080995
2309613.51922833520937.776434236
#Sta/Elev= 30
       0 2757.04   107.4 2753.26   194.4 2753.57   204.7 2751.12   242.9 2735.85
   262.1 2731.53   278.5 2730.82   374.6 2731.99   466.7 2730.56   502.8  2731.8
   578.8 2730.26   642.9 2732.36  836.79 2729.72     874 2729.72   933.2 2730.26
   949.7  2727.9    1006 2730.23  1061.8 2727.34  1097.2 2730.26  1126.8 2727.19
  1156.4 2731.71    1180 2730.41  1196.6 2726.49  1223.5 2727.79  1241.4 2731.55
  1254.5 2740.54  1272.7 2756.24  1277.2 2759.08  1286.2 2761.68  1398.9 2763.18
#Mann= 7 ,-1,0
       0      .1       0     260     .05       0   689.3      .1       0
  836.79    .045       0     874      .1       0 1375.72     .04       0
 1475.72     .05       0
#XS Ineff= 2 , 0
          648.74 2734.77
Permanent Ineff=
       F       F
Bank Sta=836.79,874
XS Rating Curve= 0 ,0
Exp/Cntr(USF)=0,0
Exp/Cntr=0.3,0.1

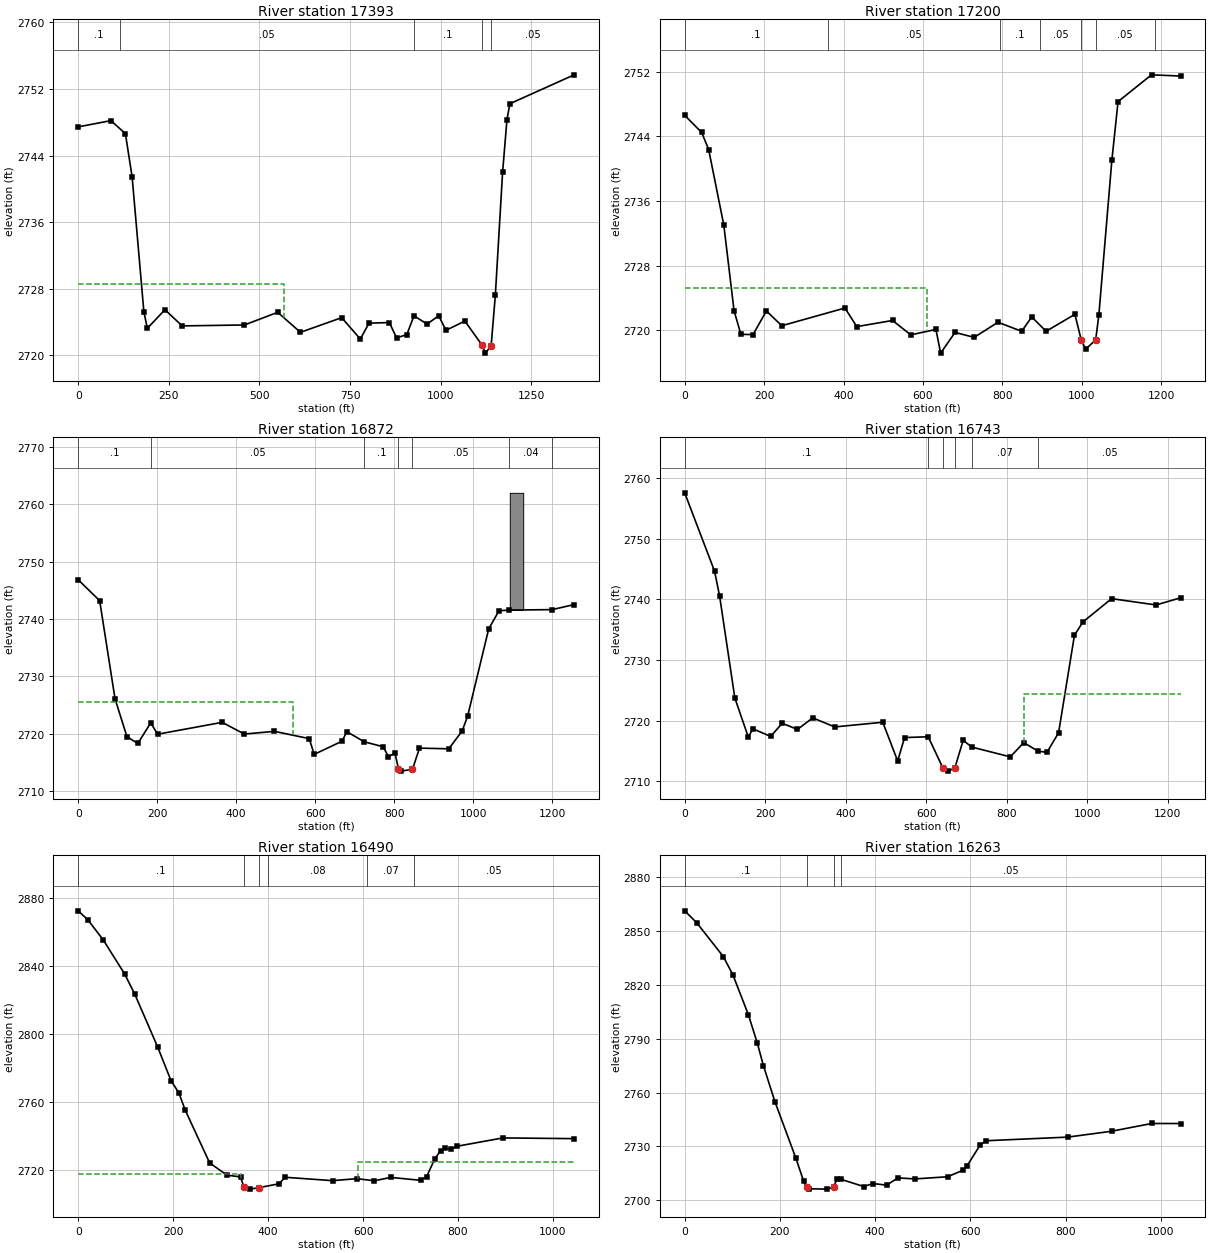
Type RM Length L Ch R = 1 ,17393   ,191.8,192.5,189
XS GIS Cut Line= 3
2308774.00578549519702.8821647532308987.88822439520400.157634614
2309026.35611291521038.277575855
#Sta/Elev= 30
       0 2747.45    90.3  2748.2   130.2 2746.64   148.8 2741.43   181.2 2725.25
   190.7 2723.26   239.3 2725.49   286.9 2723.55   458.5 2723.66   550.5 2725.18
   613.3 2722.78   727.2 2724.54   778.5 2721.97   802.5 2723.88   858.6 2723.95
   878.6 2722.11   906.7  2722.5   926.7 2724.76   962.8 2723.77   994.8 2724.77
  1014.9 2723.02    1067 2724.13  1115.1  2721.2  1123.6 2720.28  1139.5 2721.14
  1151.1 2727.23  1171.2 2742.04  1183.2 2748.33  1191.2 2750.23  1368.6  2753.7
#Mann= 5 ,-1,0
       0      .1       0   115.7     .05       0   925.6      .1       0
  1115.1    .045       0  1139.5     .05       0
#XS Ineff= 2 , 0
          568.67 2728.54
Permanent Ineff=
       F       F
Bank Sta=1115.1,1139.5
XS Rating Curve= 0 ,0
Exp/Cntr(USF)=0,0
Exp/Cntr=0.3,0.1

Type RM Length L Ch R = 1 ,17200   ,39.8,328.3,355.7
XS GIS Cut Line= 4
2308609.84583182519825.3091035262308803.61331058520323.890020343
2308789.31712863520513.5853739192308848.12847956521033.763707297
#Sta/Elev= 30
       0 2746.61    42.8 2744.49    60.4 2742.38    98.6    2733   124.3 2722.43
   141.5 2719.52   172.1 2719.48   205.7 2722.41   244.5 2720.58   403.5 2722.77
   433.3 2720.47   523.4 2721.23   569.2 2719.45   632.5 2720.12   644.5 2717.19
   680.6 2719.75   728.8 2719.14   788.8 2721.01   848.5 2719.89   873.7 2721.67
   909.9 2719.89   982.4 2721.99   998.3 2718.84  1009.5 2717.69  1034.7 2718.81
  1042.7 2721.89  1075.5 2741.06  1091.1 2748.31  1175.3 2751.62  1248.6 2751.47
#Mann= 7 ,-1,0
       0      .1       0     360     .05       0  793.43      .1       0
  893.43     .05       0   998.3    .045       0  1034.7     .05       0
 1183.43     .04       0
#XS Ineff= 2 , 0
          609.64 2725.23
Permanent Ineff=
       F       F
Bank Sta=998.3,1034.7
XS Rating Curve= 0 ,0
Exp/Cntr=0.3,0.1

Type RM Length L Ch R = 1 ,16872   ,98.6,129,171.3
XS GIS Cut Line= 5
 2308594.3892202519866.6245373872308779.01126657520328.179653315
2308727.99728007 520517.660174592308519.08285918520629.405097394
2308414.62564873 520937.91825383
#Sta/Elev= 30
       0 2746.83    54.4 2743.18    93.2  2726.1   123.4 2719.49     151 2718.31
   183.7 2721.91   200.9 2719.92   364.6 2721.99   420.6 2719.95   497.1 2720.42
   585.1 2719.15   597.6 2716.41     668  2718.7   680.4 2720.35   724.9 2718.59
   772.6 2717.73   785.6 2715.99   802.2 2716.65   811.1 2713.84     817 2713.49
   846.5  2713.8   864.3  2717.5   938.5 2717.38   972.3 2720.48     986 2723.01
  1039.6 2738.28  1065.7 2741.43  1090.5 2741.55  1200.3 2741.63    1256 2742.51
#Mann= 7 ,-1,0
       0      .1       0   183.7     .05       0   724.9      .1       0
   811.1    .045       0   846.5     .05       0  1090.5     .04       0
  1200.3     .05       0
#XS Ineff= 2 , 0
          544.58 2725.46
Permanent Ineff=
       F       F
#Block Obstruct= 1 ,-1
 1092.95    1127 2761.98
Bank Sta=811.1,846.5
XS Rating Curve= 0 ,0
Exp/Cntr(USF)=0,0
Exp/Cntr=0.3,0.1

Type RM Length L Ch R = 1 ,16743   ,288.5,252.7,41
Node Name=F
XS GIS Cut Line= 5
2308533.82888492519898.6382226162308682.30640149520356.797416603
2308621.11083217520437.4953386662308415.97126188520520.810551234
2308287.19997187520928.643625128
#Sta/Elev= 30
       0 2757.53    74.2 2744.63    86.8 2740.52   124.6 2723.74   158.2 2717.26
     169 2718.67   213.5 2717.41   242.3 2719.57   280.2 2718.56     318 2720.46
   372.7 2718.97   492.1 2719.74   529.1 2713.36   546.2 2717.22   604.9 2717.35
   641.7 2712.18     653 2711.69   670.92712.168   691.8 2716.76   713.4 2715.65
   808.9 2714.04   842.4 2716.39   877.8 2714.97   900.1 2714.79   928.8    2718
   968.3 2734.08   989.3 2736.26  1060.6  2740.1  1171.1 2739.06    1232 2740.24
#Mann= 6 ,-1,0
       0      .1       0   604.9     .08       0   641.7    .045       0
   670.9     .08       0   713.4     .07       0   877.8     .05       0
#XS Ineff= 2 , 0
                          843.37         2724.43
Permanent Ineff=
       F       F
Bank Sta=641.7,670.9
XS Rating Curve= 0 ,0
Exp/Cntr(USF)=0,0
Exp/Cntr=0.3,0.1

Type RM Length L Ch R = 1 ,16490   ,228.7,227.1,179
XS GIS Cut Line= 3
     2308357.901      519900.868     2308438.669      520341.049
     2308252.904      520908.439
#Sta/Elev= 30
       0  2872.3    20.7  2866.9    53.2    2855    97.9  2835.1   119.1 2823.31
   167.2 2792.31   195.5 2772.41   211.7 2765.36   225.6 2754.95   276.9 2724.01
   313.5 2716.81   341.9 2715.83   349.3  2709.6   362.3 2708.62   381.1 2709.51
   423.3 2711.78   435.5  2715.6   536.1  2713.6   586.6 2714.78     624 2713.53
   658.1 2715.52   721.2 2713.81   733.9 2716.03   751.2 2726.47   763.5 2731.33
   771.8 2732.64   785.7 2732.14     797 2733.79   894.4 2738.74  1044.6 2738.31
#Mann= 6 ,-1,0
       0      .1       0   349.3    .045       0   381.1      .1       0
     400     .08       0   607.5     .07       0   707.5     .05       0
#XS Ineff= 2 , 0
           343.7 2717.76  589.23         2724.68
Permanent Ineff=
       F       F
Bank Sta=349.3,381.1
XS Rating Curve= 0 ,0
Exp/Cntr=0.3,0.1

Type RM Length L Ch R = 1 ,16263   ,309.6,316,314.1
XS GIS Cut Line= 4
2308182.98729916520048.1880194992308198.96143504 520293.83622353
2308217.25470499520367.0093033332308179.67079213 521085.84435577
#Sta/Elev= 30
       0 2861.22      25 2854.68    81.1 2835.74   101.2 2825.61   133.8 2803.34
   152.6 2787.49   165.3 2775.05   189.4 2755.02   233.5 2723.46   249.6 2710.85
   256.5  2707.4     262 2706.44   298.6 2706.25   312.6 2707.43   319.7 2711.72
   328.5 2711.69   375.8 2707.71   395.9 2709.35   423.9 2708.47   447.9 2712.49
     484 2711.94   552.1 2713.14   584.8 2716.82   592.1 2718.88   620.2 2730.67
   632.2 2733.19   804.6 2735.22   896.5 2738.49   980.7  2742.8  1041.4 2742.78
#Mann= 4 ,-1,0
       0      .1       0   256.5    .045       0   312.6     .08       0
   328.5     .05       0
Bank Sta=256.5,312.6
XS Rating Curve= 0 ,0
Exp/Cntr(USF)=0,0
Exp/Cntr=0.3,0.1

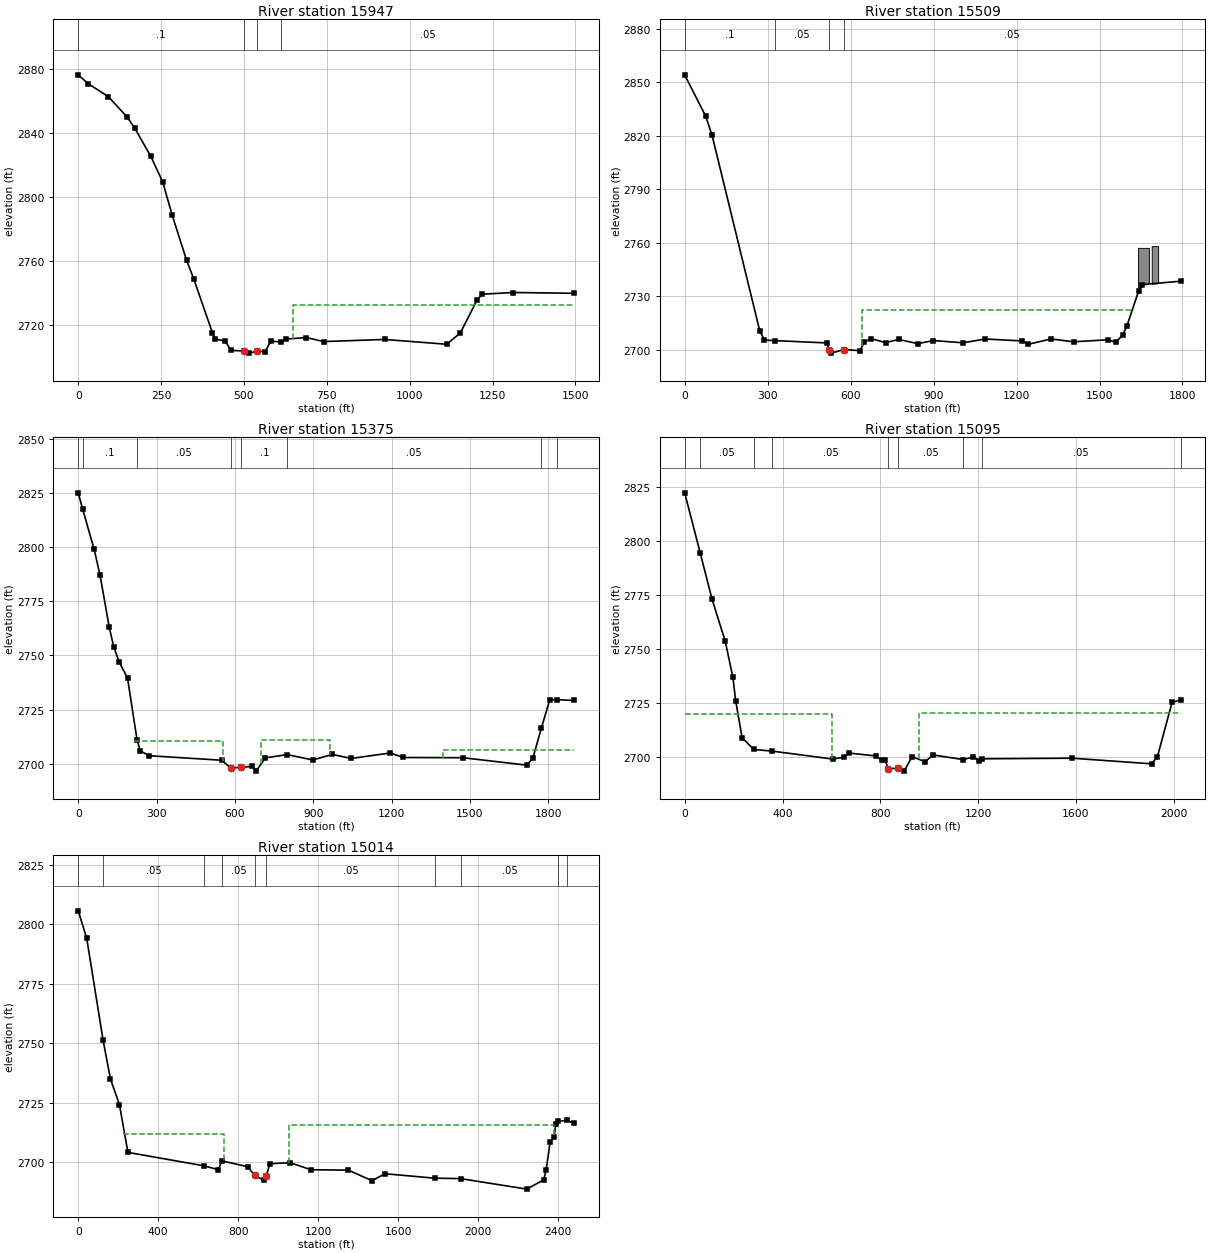
Type RM Length L Ch R = 1 ,15947   ,418.1,438.5,420.9
XS GIS Cut Line= 4
 2308119.7192595519927.5544825352307896.79573529520293.083496509
2307918.10460157521017.5849502162308116.44097238521297.878499048
#Sta/Elev= 30
       0 2876.35      30 2870.87    91.1 2862.66   147.1 2850.09   170.6 2843.04
   219.1 2825.35   254.9 2809.49   283.1 2788.96   326.8 2760.61   348.6 2748.89
   404.8 2715.34     414 2711.27   444.2 2710.03   460.3 2704.22   500.3 2703.83
   516.3 2702.51   540.4 2703.78   564.3 2703.43   580.3 2709.88   612.3 2709.63
   628.3  2711.3   688.4 2712.24   740.4 2709.72   924.5 2711.06  1111.8 2708.05
    1153 2715.14  1202.9  2735.5  1218.9 2739.32    1312 2740.38  1496.3 2739.88
#Mann= 4 ,-1,0
       0      .1       0   500.3    .045       0   540.4     .08       0
   612.3     .05       0
#XS Ineff= 2 , 0
                          647.16         2732.49
Permanent Ineff=
       F       F
Bank Sta=500.3,540.4
XS Rating Curve= 0 ,0
Exp/Cntr(USF)=0,0
Exp/Cntr=0.3,0.1

Type RM Length L Ch R = 1 ,15509   ,135.7,133.6,129.3
XS GIS Cut Line= 4
2307852.53885916519809.5361461842307514.87528571520165.230298796
2307491.92727586520765.1568419112307901.71316597521335.578800938
#Sta/Elev= 30
       0 2854.09    76.1 2830.86      99 2820.26   271.6 2710.66   288.6 2705.61
   324.9 2705.31   514.4    2704   522.4 2699.95   530.4  2698.3   574.5 2700.29
   634.5 2699.67   649.9 2704.65   674.5 2706.36   726.6 2704.22   774.6 2705.94
   842.6 2703.61   899.6 2705.33  1006.8 2704.08  1086.7 2706.21    1220 2705.13
  1242.9 2703.27  1324.3 2706.24    1406 2704.65  1532.4  2705.8  1558.7 2704.28
  1583.4 2708.39  1598.6 2713.38  1641.3 2733.02  1653.4 2736.69  1793.2 2738.55
#Mann= 4 ,-1,0
       0      .1       0   324.9     .05       0   522.4    .045       0
   574.5     .05       0
#XS Ineff= 1 ,-1
  642.04 1623.552722.272
Permanent Ineff=
       F
#Block Obstruct= 2 ,-1
 1639.35  1678.6 2757.23 1688.66 1711.91  2758.2
Bank Sta=522.4,574.5
XS Rating Curve= 0 ,0
Exp/Cntr(USF)=0,0
Exp/Cntr=0.3,0.1

Type RM Length L Ch R = 1 ,15375   ,119.7,280.1,256.5
XS GIS Cut Line= 3
2307709.66986057519740.5014060662307377.18722663520093.107982138
     2307404.624      521507.013
#Sta/Elev= 30
       0 2825.07    17.4 2817.38      61 2798.96    83.6 2787.06   118.8 2763.02
   136.3 2753.83   157.2  2746.9   188.8 2739.55   225.1 2711.17   237.3 2706.04
   270.4 2703.72   548.7 2701.63  583.73  2698.1   624.7  2698.3   665.3 2698.83
   680.7  2696.6   716.8 2702.72   799.9 2704.23   897.8 2701.75   972.8 2704.31
  1044.9 2702.44  1194.1 2704.96  1245.1  2702.9  1472.7 2702.79  1716.9 2699.37
  1740.9 2702.65    1773 2716.33    1805 2729.42  1832.1 2729.62  1898.8 2729.21
#Mann= 8 ,-1,0
       0     .12       0    17.4      .1       0   225.1     .05       0
  583.73    .045       0   624.7      .1       0   799.9     .05       0
    1773     .08       0  1832.1     .05       0
#XS Ineff= 3 ,-1
  212.62  553.28 2710.35   701.2  965.242710.981 1396.35  1898.8 2706.18
Permanent Ineff=
       F       F       F
Bank Sta=583.73,624.7
XS Rating Curve= 0 ,0
Exp/Cntr=0.3,0.1

Type RM Length L Ch R = 1 ,15095   ,116.4,81.3,86.5
BEGIN DESCRIPTION:
structure xs 4
END DESCRIPTION:
XS GIS Cut Line= 6
2307680.57284441519727.4868225662307366.76997703520079.326401147
 2307097.7960907520235.5486078532307141.26661778520378.186274845
2307114.09753836520630.8587135162307149.56828094521472.043600444
#Sta/Elev= 30
       0 2822.12    63.9 2794.19   112.1 2772.89     166 2753.55   197.2 2736.85
   208.5 2726.11   234.7 2709.08   282.3 2703.59   358.8 2702.82   606.1 2699.15
   650.4 2700.02   670.9 2701.94   782.7 2700.59   805.3 2698.51   818.3 2698.91
   832.7 2694.79   873.2 2694.82   897.3 2693.59   930.1 2700.29   983.1  2697.9
  1015.3 2701.07    1140 2698.91  1180.2  2700.2  1204.3  2698.4  1215.4 2699.28
  1584.6 2699.57  1908.9 2696.96  1932.9 2700.22    1993 2725.41  2027.9 2726.42
#Mann= 9 ,-1,0
       0      .1       0    63.9     .05       0   282.3      .1       0
   358.8     .05       0   832.7    .045       0   873.2     .05       0
    1140     .08       0  1215.4     .05       0  2027.9     .05       0
#XS Ineff= 2 , 0
          600.73 2719.94  959.55         2720.58
Permanent Ineff=
       F       F
Bank Sta=832.7,873.2
XS Rating Curve= 0 ,0
Exp/Cntr(USF)=0,0
Exp/Cntr=0.5,0.3

Type RM Length L Ch R = 1 ,15014   ,175.9,117,112.4
XS GIS Cut Line= 6
2307522.46556891519687.695380812 2307386.5213003520038.299168071
 2307091.6281122520143.9325488832307033.30968321520599.476503635
2306435.13040022 521156.038758062306390.77340993521593.133365248
#Sta/Elev= 30
       0 2805.55    42.4 2794.06   124.1 2751.32   160.9 2734.99   205.9 2724.18
   248.5 2704.09   628.8 2698.44   700.3 2696.84   718.4 2700.53   846.7 2698.07
   882.3 2694.47   926.4 2692.38   939.32694.182   958.5 2699.33  1058.9 2699.77
  1163.2 2696.81  1350.3 2696.63  1467.8 2692.23  1534.2 2695.12  1781.5 2693.26
  1910.8 2693.07  2242.7 2688.66  2326.7  2692.6  2338.7 2696.71  2358.7 2708.52
  2378.7 2710.65  2386.7 2715.87  2398.7 2717.07  2442.7 2717.61  2478.7 2716.26
#Mann= 10 ,-1,0
       0      .1       0   124.1     .05       0   628.8      .1       0
   718.4     .05       0   882.3    .045       0   939.3     .05       0
  1781.5     .08       0  1910.8     .05       0  2398.7    .016       0
  2442.7     .05       0
#XS Ineff= 4 ,-1
  224.25  729.73 2711.78   739.2   802.8  2696.5   993.7 1038.76 2694.35
 1052.71 2379.572715.502
Permanent Ineff=
       F       F       F       F
Bank Sta=882.3,939.3
XS Rating Curve= 0 ,0
Exp/Cntr=0.5,0.3