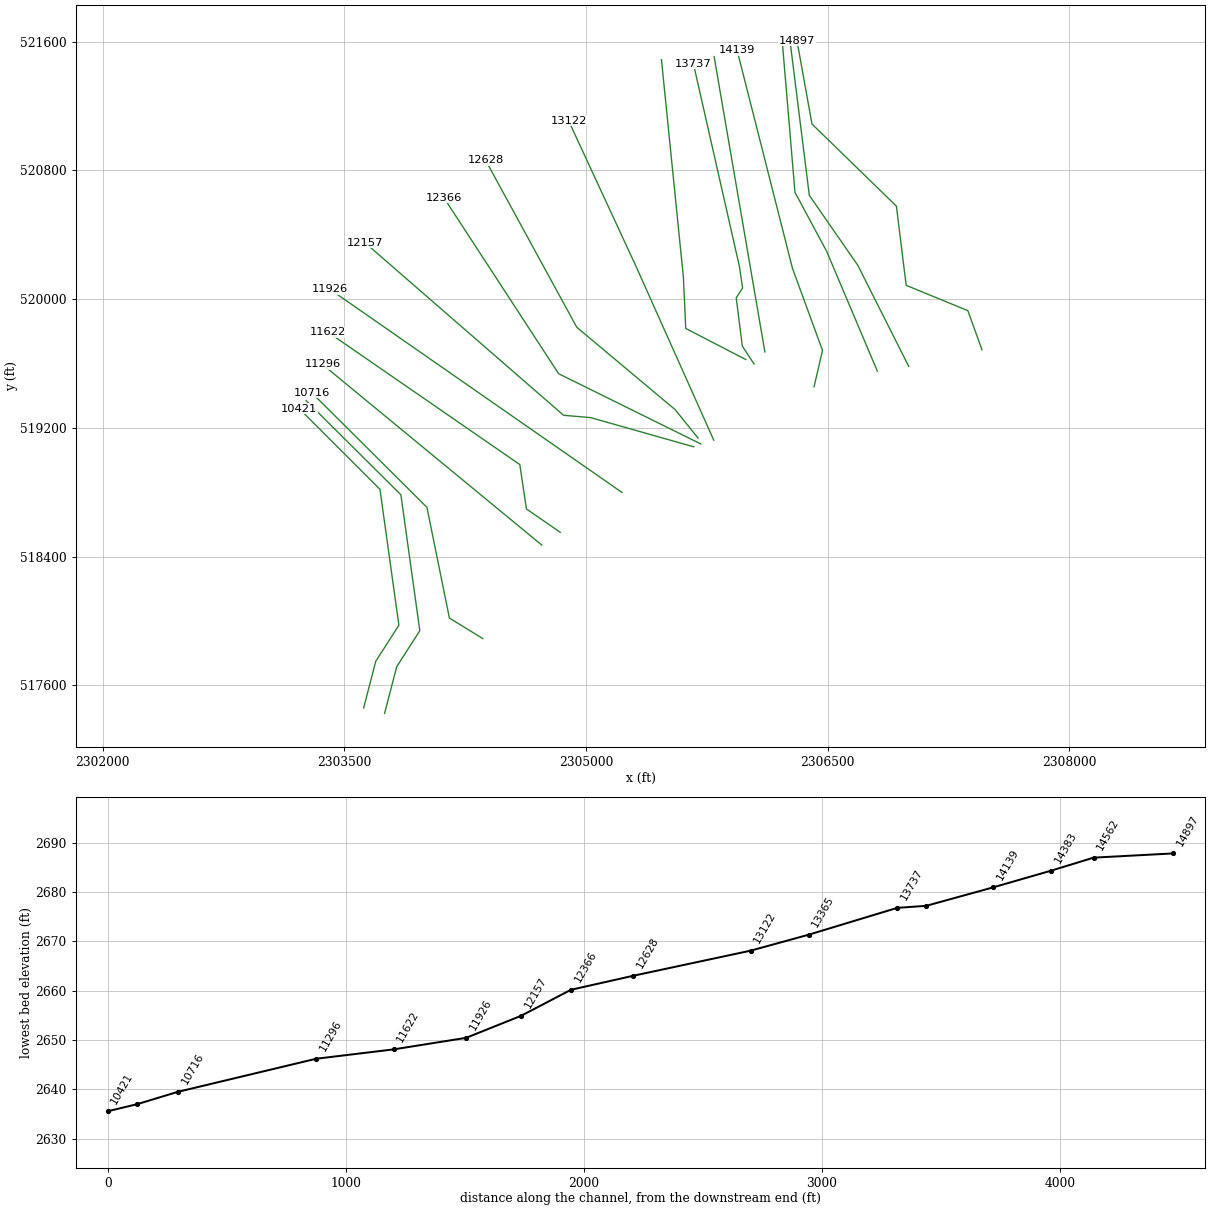
HEC-RAS study NRTHFRK.prj: NRTHFRK

--- NRTHFRK.g01 (geometry) --- (continued)

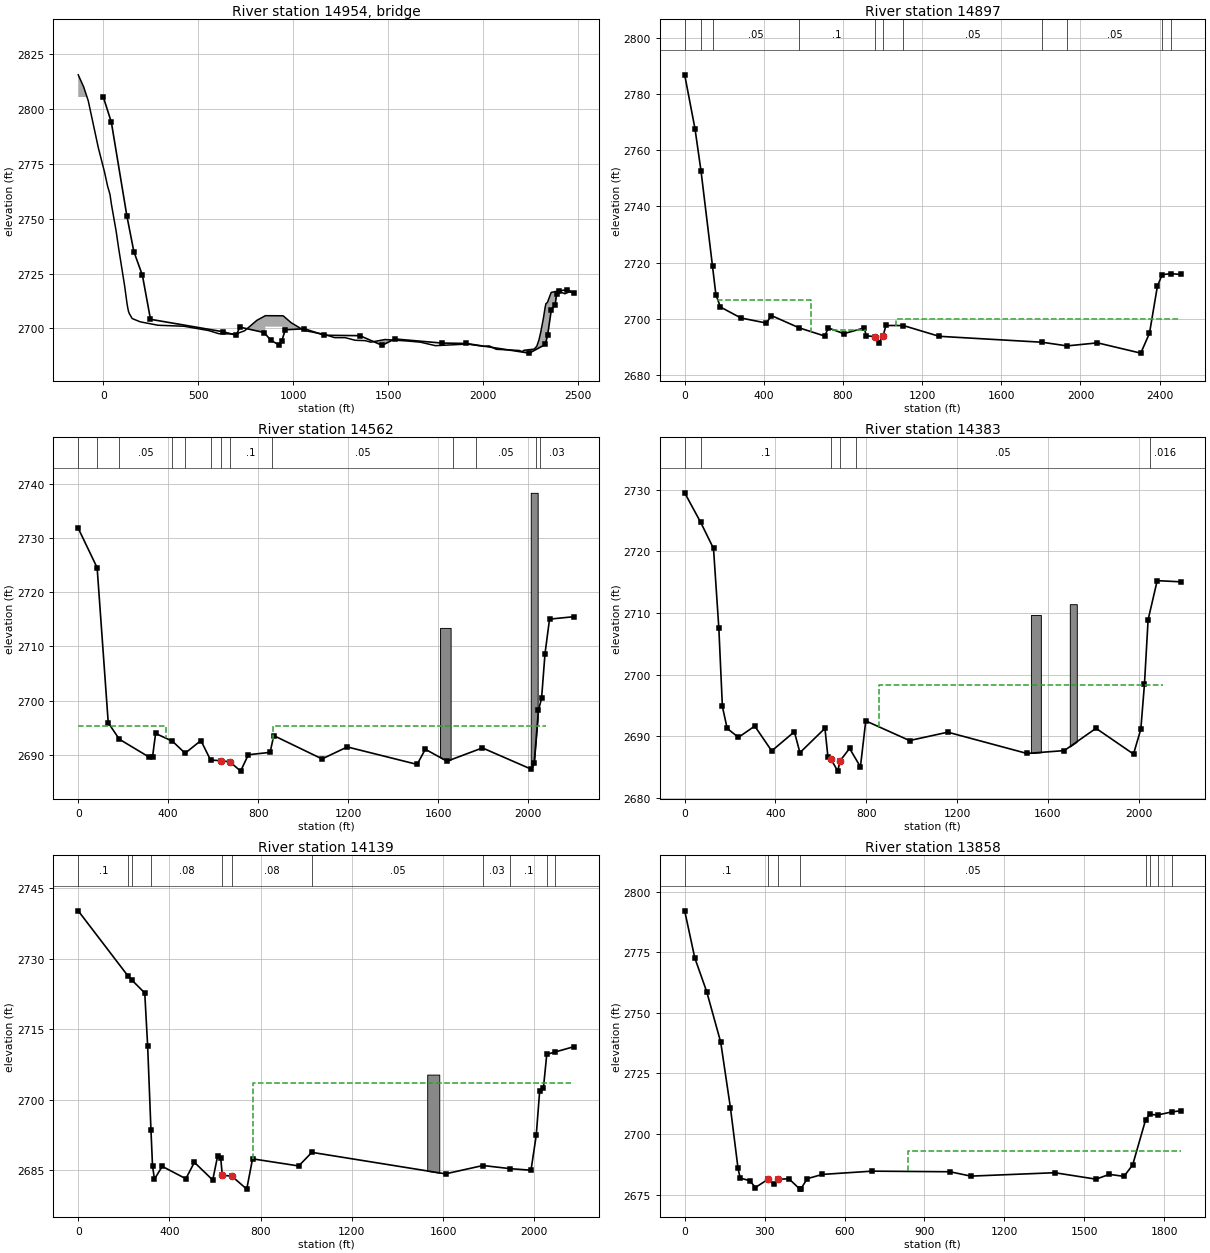
Type RM Length L Ch R = 3 ,14954   ,,,
BEGIN DESCRIPTION:
DRAFT STRUCTURE GEOMETRY
END DESCRIPTION:
Bridge Culvert--1,0,-1,-1, 0
Deck Dist Width WeirC Skew NumUp NumDn MinLoCord MaxHiCord MaxSubmerge Is_Ogee
56.72838,20,2.6,0, 60, 60, , , 0.98, 0, 0,0,,
    -132-103.439     -79  -26.05   6.535  22.827  35.046  43.193  67.631  80.135
 112.435 124.654 128.727 132.801 136.874  151.89 193.897 287.976 425.158 554.564
 608.239 697.705 744.359 808.632 849.124  852.82 945.214 949.231 989.4021057.693
1165.5321217.1251273.6861326.3841377.9791408.3291483.2871605.4821669.5721748.573
1917.376 2002.932031.2962068.4632189.0922205.1052214.3882268.3042282.047 2294.05
2302.0522316.9092326.0582330.0592338.0622357.8582394.0762430.0862450.0912472.699
2815.6812810.1972803.7832782.3452771.2982764.8152761.1742756.393 2744.312736.899
2719.3042711.4652709.3562707.6812706.7392704.458 2702.962701.3822700.928 2698.96
2697.5312697.4012698.8752703.6432705.5562705.755 2705.712705.5262702.5122698.969
2697.2152695.7372695.7132694.5252694.3652693.6762694.8732694.1562693.6562692.061
2692.7932691.7432691.9742690.4062689.8752689.3642689.9572690.5042691.8132694.877
2697.9262704.5872709.602 2711.212711.8022716.377 2717.012715.7532716.5312716.386
                                                                                
                                                                                
                                        2700.755 2700.71
                                                                                
                                                                                
                                                                                
     -56 -27.439      -3   49.95  82.535  98.827 111.046 119.193 143.631 156.135
 188.435 200.654 204.727 208.801 212.874  227.89 269.897 363.976 501.158 630.564
 684.239 773.705 820.359 884.632 925.124  928.821021.2141025.2311065.4021133.693
1241.5321293.1251349.6861402.3841453.9791484.3291559.2871681.4821745.5721824.573
1993.376 2078.932107.2962144.4632265.0922281.1052290.3882344.3042358.047 2370.05
2378.0522392.9092402.0582406.0592414.0622433.8582470.0762506.0862526.0912548.699
2815.6812810.1972803.7832782.3452771.2982764.8152761.1742756.393 2744.312736.899
2719.3042711.4652709.3562707.6812706.7392704.458 2702.962701.3822700.928 2698.96
2697.5312697.4012698.8752703.6432705.5562705.755 2705.712705.5262702.5122698.969
2697.2152695.7372695.7132694.5252694.3652693.6762694.8732694.1562693.6562692.061
2692.7932691.7432691.9742690.4062689.8752689.3642689.9572690.5042691.8132694.877
2697.9262704.5872709.602 2711.212711.8022716.377 2717.012715.7532716.5312716.386
                                                                                
                                                                                
                                        2700.755 2700.71
                                                                                
                                                                                
                                                                                
BR Coef=-1 ,-1 , 0 ,, 0 ,,,0.8,0,1.2,0,
WSPro=,,,, 1 ,,,, 0 ,,,, 0 ,,,,-1 ,-1 ,-1 , 0 , 0 , 0 , 0 , 0
BR U #Sta/Elev= 30
       0 2805.55    42.4 2794.06   124.1 2751.32   160.9 2734.99   205.9 2724.18
   248.5 2704.09   628.8 2698.44   700.3 2696.84   718.4 2700.53   846.7 2698.07
   882.3 2694.47   926.4 2692.38   939.32694.182   958.5 2699.33  1058.9 2699.77
  1163.2 2696.81  1350.3 2696.63  1467.8 2692.23  1534.2 2695.12  1781.5 2693.26
  1910.8 2693.07  2242.7 2688.66  2326.7  2692.6  2338.7 2696.71  2358.7 2708.52
  2378.7 2710.65  2386.7 2715.87  2398.7 2717.07  2442.7 2717.61  2478.7 2716.26
BR U #Mann= 10
       0      .1   124.1     .05   628.8      .1   718.4     .05   882.3    .035
   939.3     .05  1781.5     .08  1910.8     .05  2398.7    .016  2442.7     .05
BR D #Sta/Elev= 30
       0 2786.77    52.1 2767.61    82.7 2752.51   140.7 2718.68   157.7 2708.65
   180.5 2704.25   284.5 2700.34   413.1 2698.55     438 2701.22     578 2696.86
   708.5 2693.91   725.2 2696.84     804 2694.78   908.5 2696.84   916.5 2694.04
   960.7 2693.72   980.7 2691.61 1002.18  2693.9  1016.8 2697.68    1105 2697.66
  1285.8 2693.84    1806 2691.73  1932.3 2690.43  2085.9 2691.51  2304.5 2687.86
  2348.6 2694.93  2388.7 2711.69  2412.8 2715.78  2456.9 2716.07  2505.9 2715.85
BR D #Mann= 11
       0     .05    82.7      .1   140.7     .05     578      .1   960.7    .035
 1002.18      .1    1105     .05    1806     .08  1932.3     .05  2412.8    .016
  2456.9     .05
BC Design=,, 0 ,, 0 ,,,,,,
BC Use User HTab Curves=0
BC User HTab FreeFlow(D)= 0

Type RM Length L Ch R = 1 ,14897   ,222.1,335.3,328.1
XS GIS Cut Line= 6
2307457.75408672519685.3657716792307370.01608454519928.264396392
 2306987.0950791520085.6141198932306926.57595468520577.469549299
2306402.42894919521087.6729728442306309.06123344521606.079427073
#Sta/Elev= 30
       0 2786.77    52.1 2767.61    82.7 2752.51   140.7 2718.68   157.7 2708.65
   180.5 2704.25   284.5 2700.34   413.1 2698.55     438 2701.22     578 2696.86
   708.5 2693.91   725.2 2696.84     804 2694.78   908.5 2696.84   916.5 2694.04
   960.7 2693.72   980.7 2691.61 1002.18  2693.9  1016.8 2697.68    1105 2697.66
  1285.8 2693.84    1806 2691.73  1932.3 2690.43  2085.9 2691.51  2304.5 2687.86
  2348.6 2694.93  2388.7 2711.69  2412.8 2715.78  2456.9 2716.07  2505.9 2715.85
#Mann= 11 ,-1,0
       0     .05       0    82.7      .1       0   140.7     .05       0
     578      .1       0   960.7    .045       0 1002.18      .1       0
    1105     .05       0    1806     .08       0  1932.3     .05       0
  2412.8    .016       0  2456.9     .05       0
#XS Ineff= 3 ,-1
  169.44  637.87 2706.72  742.27   912.1    2696    1070    2500    2700
Permanent Ineff=
       F       F       F
Bank Sta=960.7,1002.18
XS Rating Curve= 0 ,0
Exp/Cntr=0.5,0.3

Type RM Length L Ch R = 1 ,14562   ,165.9,178.3,125.4
XS GIS Cut Line= 4
     2307003.032      519582.062 2306687.1077877520209.487174928
2306385.86496234520644.5863246662306265.34948234521609.725848339
#Sta/Elev= 30
       0 2731.79    84.1 2724.51   133.4 2695.93   182.6 2692.89   312.5 2689.65
   330.4 2689.66     344 2693.94   418.5 2692.53   475.1  2690.3   545.4 2692.64
   588.3 2689.04   633.92688.925   674.6 2688.71   721.7    2687   756.1 2690.02
   852.9 2690.46   869.2 2693.55  1083.8 2689.25  1195.9 2691.46  1506.4 2688.24
  1542.7 2691.03  1639.4 2688.83  1796.6 2691.28  2013.5 2687.36  2026.4 2688.48
  2045.7 2698.26  2059.5 2700.42  2074.8 2708.68  2094.9 2715.03  2204.3 2715.48
#Mann= 13 ,-1,0
       0     .05       0    84.1      .1       0   182.6     .05       0
   418.5      .1       0   475.1     .12       0   588.3      .1       0
   633.9    .045       0   674.6      .1       0     861     .05       0
  1667.1     .04       0  1767.2     .05       0  2036.2    .016       0
  2050.7     .03       0
#XS Ineff= 2 ,-1
       0   389.5 2695.28   864.8  2078.2 2695.39
Permanent Ineff=
       F       F
#Block Obstruct= 2 ,-1
 1608.27 1655.22 2713.41  2011.4 2042.13 2738.32
Bank Sta=633.9,674.6
XS Rating Curve= 0 ,0
Exp/Cntr=0.3,0.1

Type RM Length L Ch R = 1 ,14383   ,262.2,244.1,239.1
XS GIS Cut Line= 4
2306808.40441117519552.1906071982306493.53087685520296.742600863
2306296.83353304 520663.220809872306216.22203634521619.951550938
#Sta/Elev= 30
       0 2729.52    70.6 2724.72     127 2720.49   150.5 2707.53   166.1 2694.85
   187.1 2691.29   236.8 2689.84   308.7 2691.67   383.3 2687.64   483.2 2690.75
   507.6 2687.35   617.8 2691.31   630.8 2686.72   643.92686.323   674.2 2684.36
   684.32686.024   726.4 2688.05   774.1 2685.05   797.6 2692.51   990.5 2689.32
  1158.9 2690.68  1507.3 2687.23  1671.9 2687.69  1811.7 2691.31  1976.9 2687.13
  2009.1 2691.17  2025.1 2698.45  2041.2 2708.93  2081.3 2715.27  2184.4 2715.08
#Mann= 6 ,-1,0
       0     .06       0    70.6      .1       0   643.9    .045       0
   684.3      .1       0   753.3     .05       0  2049.5    .016       0
#XS Ineff= 1 ,-1
  854.18  2108.5 2698.26
Permanent Ineff=
       F
#Block Obstruct= 2 ,-1
 1525.03 1568.81 2709.69 1696.33 1727.13 2711.45
Bank Sta=643.9,684.3
XS Rating Curve= 0 ,0
Exp/Cntr(USF)=0,0
Exp/Cntr=0.3,0.1

Type RM Length L Ch R = 1 ,14139   ,370.3,280.7,264.9
XS GIS Cut Line= 4
2306415.20433289519455.1231359742306467.85915487519681.008030332
2306281.49452547520190.5406862342305936.96094359521547.925412454
#Sta/Elev= 30
       0 2740.15   219.8  2726.2   234.9 2725.44   291.8 2722.68   304.5 2711.42
   319.1 2693.45   325.8 2685.95   334.3 2683.08   368.4  2685.8     472 2683.17
   509.4 2686.66   589.9 2682.89   611.2 2687.96   624.8 2687.62     6322683.863
   672.72683.764     739 2680.96   764.5  2687.4     967 2685.89  1024.6 2688.78
  1610.8 2684.21    1775 2685.98  1895.6 2685.31  1985.7 2684.98  2008.7 2692.42
  2023.5 2701.73    2040 2702.41  2054.8 2709.62    2091 2710.12  2174.9 2711.27
#Mann= 11 ,-1,0
       0      .1       0   219.8     .08       0   234.9      .1       0
   319.1     .08       0     632    .045       0   672.7     .08       0
  1024.6     .05       0    1775     .03       0  1895.6      .1       0
  2054.8    .016       0    2091      .1       0
#XS Ineff= 1 ,-1
  766.03 2162.562703.571
Permanent Ineff=
       F
#Block Obstruct= 1 ,-1
  1530.5 1583.33 2705.32
Bank Sta=632,672.7
XS Rating Curve= 0 ,0
Exp/Cntr=0.3,0.1

Type RM Length L Ch R = 1 ,13858   ,124.5,121.6,69.1
Node Name=E
XS GIS Cut Line= 2
     2306110.105      519671.8032305794.83898045521506.601988197
#Sta/Elev= 30
       0 2792.07    37.9 2772.66    82.6 2758.74   135.3 2737.83   171.9 2710.67
   200.2 2685.84   208.4 2681.79   244.9 2680.68   265.2 2677.88   313.9 2681.34
   334.2 2679.22   351.62681.219     391 2681.53   431.6  2677.3   435.7 2677.22
     460 2681.53   516.8 2683.29   703.5 2684.64   995.8 2684.39  1074.3 2682.59
  1389.4 2683.99  1544.1 2681.33    1594 2683.31  1649.2 2682.49  1681.7 2687.22
  1730.4 2705.86    1745 2708.07    1775 2707.82  1830.2 2709.11  1861.7 2709.55
#Mann= 8 ,-1,0
       0      .1       0   313.9    .045       0   351.6      .1       0
   431.6     .05       0  1730.4     .03       0    1745    .016       0
    1775     .03       0  1830.2      .1       0
#XS Ineff= 2 , 0
                          839.93         2692.91
Permanent Ineff=
       F       F
Bank Sta=313.9,351.6
XS Rating Curve= 0 ,0
Exp/Cntr=0.3,0.1

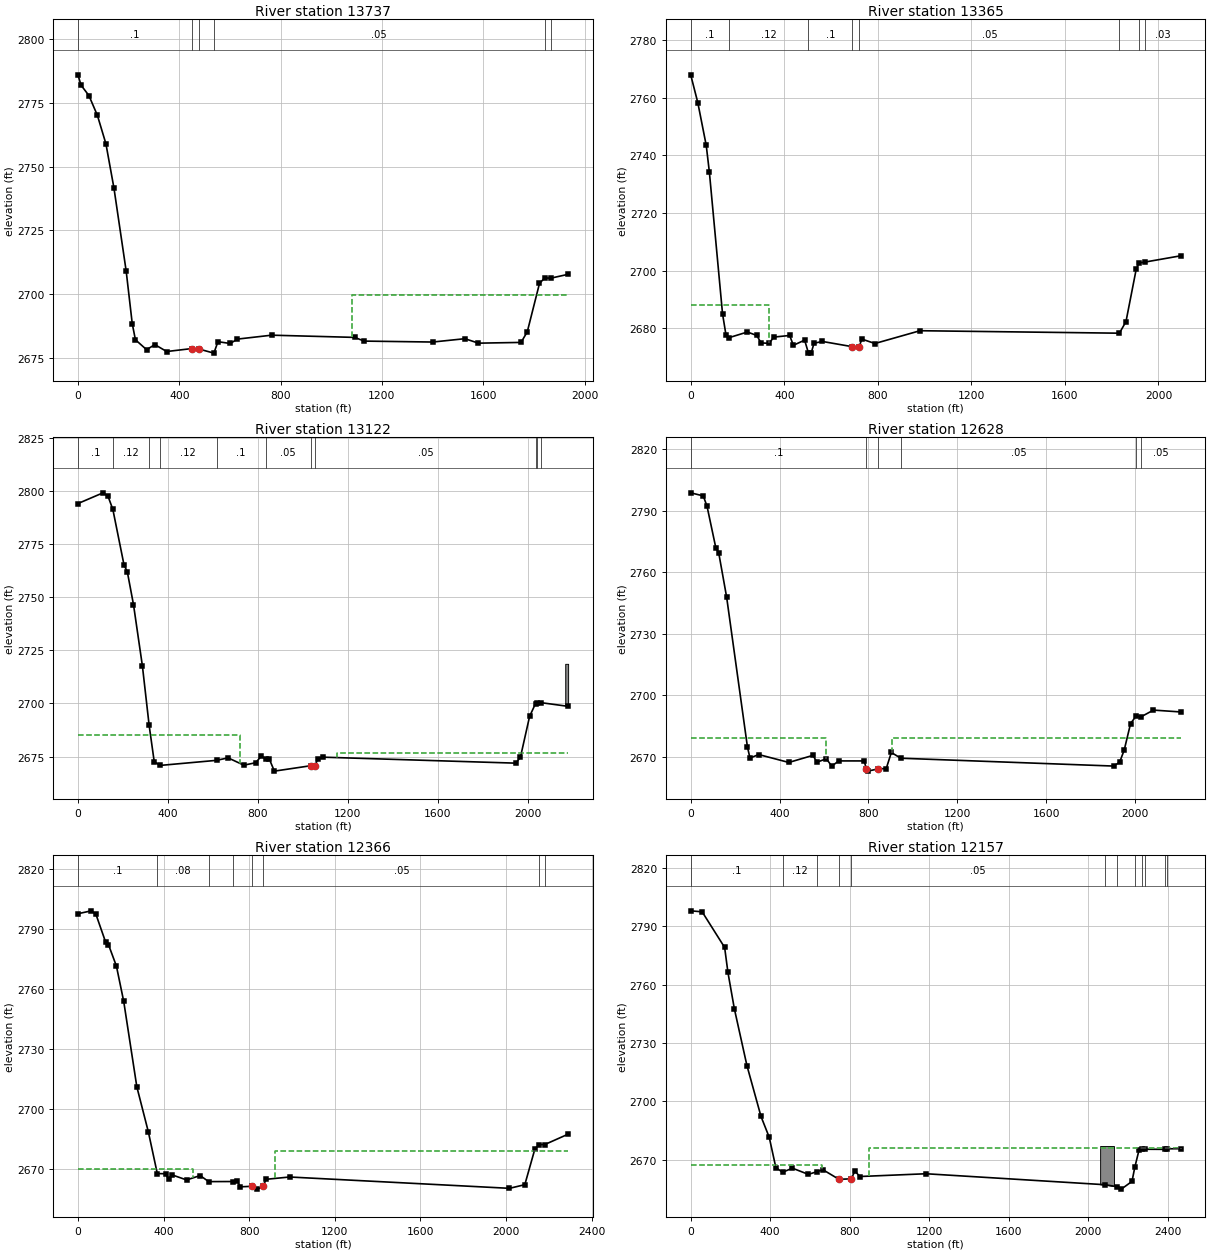
Type RM Length L Ch R = 1 ,13737   ,330.8,372.1,360
XS GIS Cut Line= 6
2306042.90807389519596.8064632362305970.05724898519707.903971221
2305932.05357805520007.8242061532305971.84493538520069.124405283
2305951.87503438520202.9090382372305666.24389691521462.477819927
#Sta/Elev= 30
       0 2785.96    12.3 2781.91    43.5  2777.8      77 2770.01   110.5 2758.91
   142.2 2741.56   190.6  2708.9   214.4 2688.39   226.9 2682.06   271.2 2678.15
   303.5 2680.16   350.4 2677.44   449.22678.591   476.7 2678.45   536.6 2676.81
   552.8  2681.3   601.3 2680.59   629.6 2682.31   764.8 2683.85  1092.5 2682.98
  1129.8 2681.53  1400.5 2681.16  1527.7 2682.47    1581 2680.72  1749.2 2681.01
  1773.8 2685.17    1822 2704.14  1842.1 2706.26  1868.1 2706.24  1935.1 2707.72
#Mann= 6 ,-1,0
       0      .1       0   449.2    .045       0   476.7     .08       0
   536.6     .05       0  1842.1    .016       0  1868.1     .05       0
#XS Ineff= 2 , 0
                         1081.69         2699.75
Permanent Ineff=
       F       F
Bank Sta=449.2,476.7
XS Rating Curve= 0 ,0
Exp/Cntr(USF)=0,0
Exp/Cntr=0.3,0.1

Type RM Length L Ch R = 1 ,13365   ,183.6,243.2,248.7
XS GIS Cut Line= 4
     2305991.198      519624.689     2305618.772      519817.633
2305604.05254341520136.4256971852305467.97893366521486.960691328
#Sta/Elev= 30
       0 2767.97    30.4 2758.31    66.5 2743.44    79.8 2734.24   136.1 2685.02
     151 2677.58   162.9  2676.7   242.2 2678.69   282.7 2677.49   300.7  2674.9
     335 2674.77   355.7 2676.93     423 2677.49     439 2674.08   487.1 2675.87
   503.1 2671.48   515.1 2671.36   527.1 2674.79   563.1 2675.41   691.3 2673.59
     721 2673.64   731.3 2676.25   787.6  2674.7   980.5 2679.14  1832.8 2678.28
    1861 2682.29  1905.2 2700.65  1917.3 2702.66  1944.4    2703  2095.9 2705.16
#Mann= 8 ,-1,0
       0      .1       0   162.9     .12       0   503.1      .1       0
   691.3    .045       0     721     .05       0  1832.8     .03       0
  1917.3    .016       0  1944.4     .03       0
#XS Ineff= 2 , 0
          335.63  2688.1
Permanent Ineff=
       F       F
Bank Sta=691.3,721
XS Rating Curve= 0 ,0
Exp/Cntr=0.3,0.1

Type RM Length L Ch R = 1 ,13122   ,443,493.4,490.7
XS GIS Cut Line= 3
2305792.80965612519123.3246929132305313.01218751520196.785569087
2304891.15754337521108.704967475
#Sta/Elev= 30
       0 2793.97   111.6 2799.02   133.5  2797.5   155.4  2791.2   204.8 2765.24
   219.9 2761.77   247.2 2746.44   286.8 2717.61   316.8 2689.64   339.4 2672.58
   365.2 2670.81   616.6  2673.2     668 2674.37   738.1 2670.93   790.7 2672.08
   816.4 2675.29   834.5 2673.72     852 2673.63   873.9 2668.13  1037.22670.697
  1055.6  2670.7  1066.7 2674.01  1088.6  2674.7  1948.1 2671.88  1968.6 2674.78
  2009.2 2693.88  2035.5 2699.88  2044.2 2700.14  2062.1  2700.3  2180.6  2698.6
#Mann= 11 ,-1,0
       0      .1       0   155.4     .12       0   316.8      .1       0
   365.2     .12       0   616.6      .1       0   834.5     .05       0
  1037.2    .045       0  1055.6     .05       0  2035.5    .016       0
  2044.2    .016       0  2062.1     .05       0
#XS Ineff= 2 , 0
          722.89 2684.93 1151.82         2676.64
Permanent Ineff=
       F       F
#Block Obstruct= 1 ,-1
 2167.62 2180.58  2718.6
Bank Sta=1037.2,1055.6
XS Rating Curve= 0 ,0
Exp/Cntr(USF)=0,0
Exp/Cntr=0.3,0.1

Type RM Length L Ch R = 1 ,12628   ,259.8,262,274.4
XS GIS Cut Line= 4
2305695.11607454519136.7504887292305553.46169278519312.806648923
2304942.32421716519824.786057302 2304375.7066901520862.910312237
#Sta/Elev= 30
       0 2798.73    56.5 2797.24    73.5 2792.17   113.2 2771.85   125.9 2769.56
   161.7 2747.88   255.5 2674.69   266.9 2669.39   305.9 2671.12   441.6 2667.26
   550.4 2670.73   567.9 2667.37   610.5 2669.07   634.7 2665.45     666 2668.01
   780.8    2668  789.86 2664.23   796.4 2663.03   844.4 2664.13   879.9 2664.29
   902.9 2672.12   945.5 2669.32  1903.2  2665.5  1930.1 2667.35  1950.8 2673.33
  1979.5 2686.25  2003.8 2689.82  2027.4 2689.57  2082.3 2692.79  2205.9 2691.88
#Mann= 6 ,-1,0
       0      .1       0  789.86    .045       0   844.4      .1       0
   945.5     .05       0  2003.8    .016       0  2027.4     .05       0
#XS Ineff= 2 , 0
          606.71 2679.12  903.61         2679.12
Permanent Ineff=
       F       F
Bank Sta=789.86,844.4
XS Rating Curve= 0 ,0
Exp/Cntr(USF)=0,0
Exp/Cntr=0.3,0.1

Type RM Length L Ch R = 1 ,12366   ,164.7,208.7,220.3
XS GIS Cut Line= 3
     2305712.003      519100.201     2304829.547      519536.443
     2304116.602      520630.789
#Sta/Elev= 30
       0 2797.55    62.3    2799    84.2 2797.25   129.2 2783.45   142.6 2782.18
   179.8 2771.45     214  2753.8   275.3 2711.18   329.1 2688.71   370.9 2667.95
   410.3 2667.84   423.7 2665.11   441.6 2667.23   507.7 2664.76     571 2666.94
   611.1 2663.93   722.7 2663.97     745 2664.04     759 2661.33   812.8 2661.58
   838.7 2660.18   865.7 2661.56   878.8 2665.07   988.8 2666.23  2016.5 2660.58
  2088.1  2662.4  2135.8 2680.44  2156.7 2682.41  2181.4 2682.42  2290.5  2687.6
#Mann= 8 ,-1,0
       0      .1       0   370.9     .08       0   611.1      .1       0
   722.7     .08       0   812.8    .045       0   865.7     .05       0
  2156.7    .016       0  2181.4     .03       0
#XS Ineff= 2 , 0
          536.98 2670.06  920.83         2679.12
Permanent Ineff=
       F       F
Bank Sta=812.8,865.7
XS Rating Curve= 0 ,0
Exp/Cntr=0.3,0.1

Type RM Length L Ch R = 1 ,12157   ,272.4,231.5,213.5
XS GIS Cut Line= 4
2305668.38168312519082.3034228362305027.76345065519263.811922037
2304860.49091217519278.0478827582303628.92758953520348.947237156
#Sta/Elev= 30
       0  2797.9    57.6 2797.39   170.7 2779.09   187.3 2766.25   219.5 2747.62
   282.9 2718.38   353.6 2692.27   395.2 2681.49   428.4 2665.92   462.5  2663.6
   511.6 2665.68   592.1 2662.48   636.3 2663.94   665.4 2664.86   745.7 2659.96
   807.3 2660.19     826  2664.2   850.7 2661.39    1184 2662.81  2085.1 2657.17
    2143 2656.19  2165.9 2654.91  2219.8 2658.89    2234 2666.19  2254.7 2674.79
  2270.6 2675.51  2286.5  2675.4  2386.9 2675.35  2395.6 2675.62  2465.8 2675.69
#Mann= 12 ,-1,0
       0      .1       0   462.5     .12       0   636.3     .08       0
   745.7    .045       0   807.3     .05       0  2085.1     .03       0
    2143     .05       0    2234     .04       0  2270.6    .016       0
  2286.5     .04       0  2386.9      .1       0  2395.6     .12       0
#XS Ineff= 2 , 0
          661.51 2667.16  895.01          2675.9
Permanent Ineff=
       F       F
#Block Obstruct= 1 ,-1
 2059.52 2129.03 2677.05
Bank Sta=745.7,807.3
XS Rating Curve= 0 ,0
Exp/Cntr(USF)=0,0
Exp/Cntr=0.3,0.1

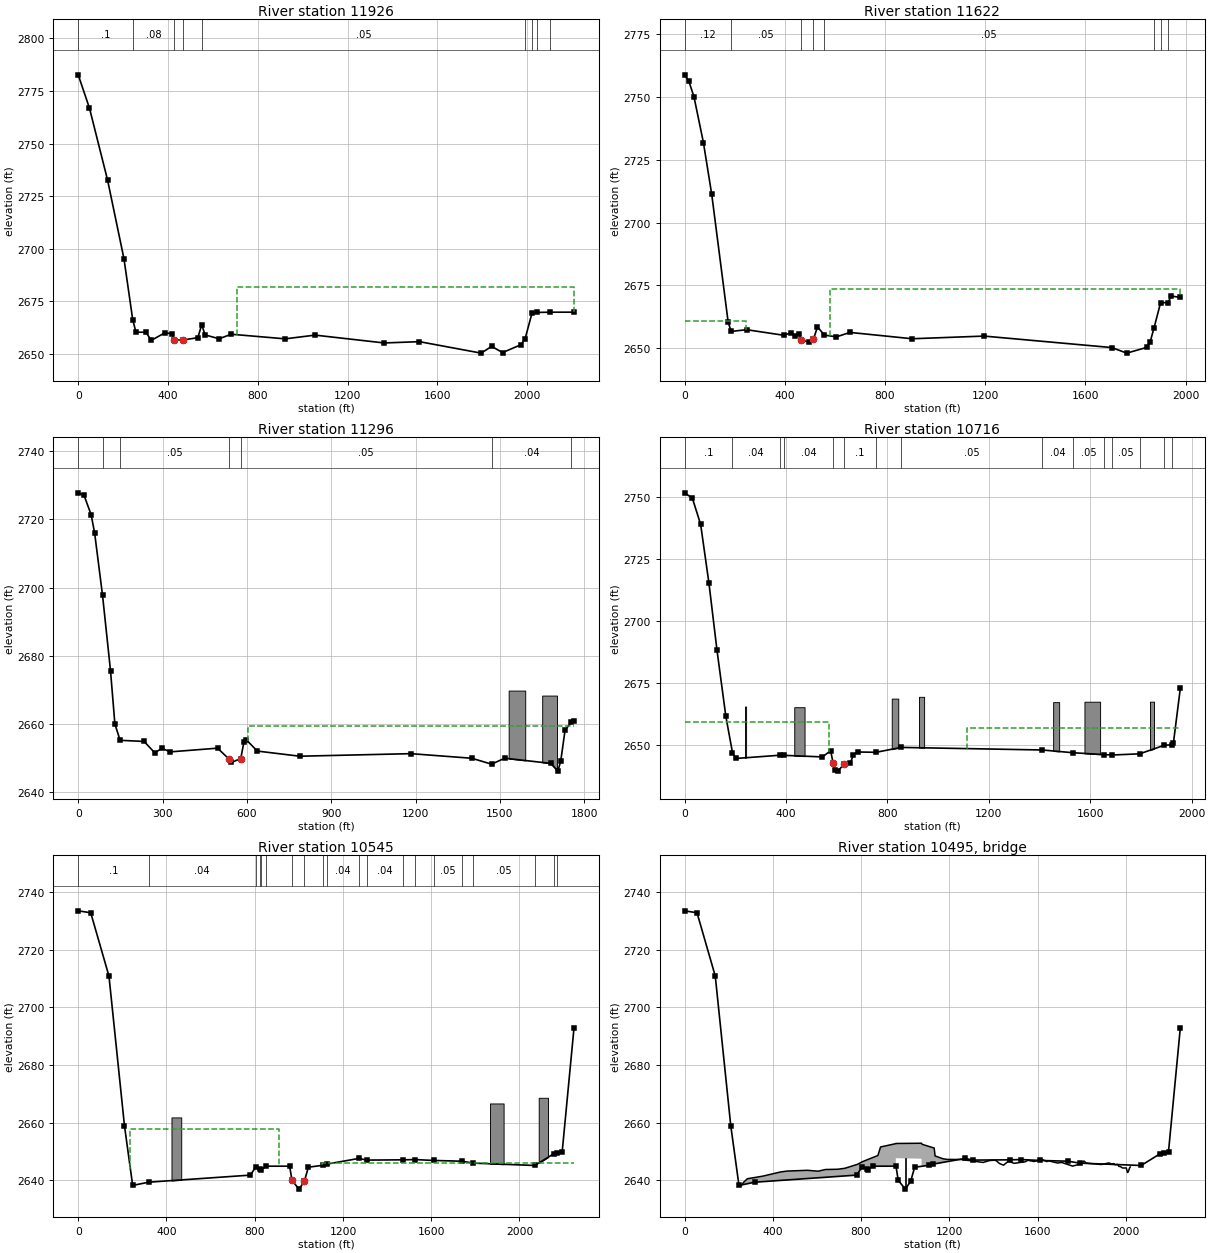
Type RM Length L Ch R = 1 ,11926   ,350.4,304.4,272.5
XS GIS Cut Line= 2
     2305223.411       518798.57     2303411.135      520059.934
#Sta/Elev= 30
       0 2782.68    50.2 2766.83   130.8 2732.67   203.8 2695.27   242.7  2666.4
   257.1 2660.39   301.2 2660.36   325.6  2656.5   386.4 2660.12     418 2659.63
   427.9 2656.59   467.4  2656.7   532.9 2657.76   550.2 2664.01   564.7  2659.1
   627.7 2657.25   681.4 2659.41   921.8 2657.22  1054.9 2658.99    1363 2655.26
  1519.6 2655.88  1794.4 2650.43  1841.2 2653.63    1890  2650.7  1972.5 2654.46
  1990.5 2657.36  2021.4 2669.65  2042.2 2669.77  2101.9 2669.88    2208 2669.89
#Mann= 9 ,-1,0
       0      .1       0   242.7     .08       0   427.9    .045       0
   467.4     .08       0   550.2     .05       0  1990.5     .04       0
  2021.4    .016       0  2042.2     .04       0  2101.9     .07       0
#XS Ineff= 2 , 0
                          705.68         2681.76
Permanent Ineff=
       F       F
Bank Sta=427.9,467.4
XS Rating Curve= 0 ,0
Exp/Cntr=0.3,0.1

Type RM Length L Ch R = 1 ,11622   ,297.3,325.2,346.9
XS GIS Cut Line= 4
2304839.29752482518551.2984271732304629.57813341518696.488775073
2304588.62700965518971.9781531382303399.12939062519793.495001186
#Sta/Elev= 30
       0  2758.8    17.4 2756.27    37.9 2749.99    75.5 2731.84   108.7 2711.21
   174.1 2660.51     186 2656.72     248 2657.41   397.7 2655.17   425.6 2656.23
   441.8 2654.75     458 2655.74   466.1 2653.45   498.4 2652.39   514.6 2653.57
   530.8 2658.53   558.4 2655.26   606.7 2654.57   660.5 2656.33   908.5 2653.81
  1196.1 2654.87  1705.7  2650.3  1765.4 2648.09  1846.7 2650.41    1859  2652.6
  1874.7 2658.28  1900.6 2668.18  1929.3 2668.16  1943.9  2670.8  1979.2 2670.23
#Mann= 8 ,-1,0
       0     .12       0     186     .05       0   466.1    .045       0
   514.6      .1       0   558.4     .05       0  1874.7     .04       0
  1900.6    .016       0  1929.3     .04       0
#XS Ineff= 2 , 0
          243.72    2661  581.76         2673.66
Permanent Ineff=
       F       F
Bank Sta=466.1,514.6
XS Rating Curve= 0 ,0
Exp/Cntr(USF)=0,0
Exp/Cntr=0.3,0.1

Type RM Length L Ch R = 1 ,11296   ,653.6,580.4,550.6
XS GIS Cut Line= 2
     2304724.848      518472.011     2303363.771      519593.778
#Sta/Elev= 30
       0 2727.77    20.7 2727.04    45.9 2721.39    58.4 2716.02    86.6 2697.68
   114.9 2675.64   130.5    2660   149.1 2655.22   234.5 2654.89   272.3 2651.55
   297.4 2652.85   328.1 2651.84   495.7 2652.92   534.7 2649.88   545.1 2648.72
   578.3 2649.88   589.5 2654.71     598 2655.37   637.1 2652.07   788.4 2650.56
  1183.4 2651.31  1400.4 2649.96  1470.4 2648.23  1517.5 2649.98  1681.1 2648.46
  1706.3 2646.19  1716.6 2649.13  1732.1 2658.24  1754.5 2660.52  1763.8 2660.89
#Mann= 7 ,-1,0
       0     .12       0    86.6      .1       0   149.1     .05       0
   534.7    .045       0   578.3     .05       0  1470.4     .04       0
  1754.5    .016       0
#XS Ineff= 2 , 0
                          602.41         2659.51
Permanent Ineff=
       F       F
#Block Obstruct= 2 ,-1
 1531.37 1590.33  2669.8 1650.64 1703.34 2668.34
Bank Sta=534.7,578.3
XS Rating Curve= 0 ,0
Exp/Cntr=0.3,0.1

Type RM Length L Ch R = 1 ,10716   ,279.2,170.7,169.8
Node Name=D
XS GIS Cut Line= 4
     2304358.405      517891.186     2304151.501      518018.319
     2304011.903      518706.336     2303295.891      519419.131
#Sta/Elev= 30
       0 2751.62    30.8 2749.52    63.6  2738.9    96.5  2715.1   128.1 2688.17
     163 2661.56   189.2  2646.9   202.5 2644.58   376.4 2645.89   392.7 2645.84
   543.7 2645.21   576.4 2647.69   586.1 2642.64   592.7 2639.75   604.9 2639.48
   629.4 2642.35   653.9 2642.76   666.2  2646.1   682.4 2647.19   755.9 2647.07
   853.9 2649.04  1410.6    2648  1532.9 2646.89  1655.7 2646.13    1686 2645.97
  1795.2 2646.45  1892.7 2649.94  1920.9 2650.04  1928.2 2650.97  1955.2 2672.78
#Mann= 15 ,-1,0
       0      .1       0   189.2     .04       0   376.4    .016       0
   392.7     .04       0   586.1    .045       0   629.4      .1       0
   755.9     .04       0   853.9     .05       0  1410.6     .04       0
  1532.9     .05       0  1655.7     .04       0    1686     .05       0
  1795.2     .03       0  1892.7    .016       0  1920.9     .04       0
#XS Ineff= 2 , 0
          567.99 2659.27 1112.11         2656.76
Permanent Ineff=
       F       F
#Block Obstruct= 7 ,-1
  238.44  242.84 2665.51  432.74  473.43 2665.24  817.27  842.93  2668.7
  924.73  944.88 2669.42 1453.68 1477.43 2667.28 1577.18 1638.92 2667.45
 1835.56 1851.53 2667.47
Bank Sta=586.1,629.4
XS Rating Curve= 0 ,0
Exp/Cntr=0.5,0.3

Type RM Length L Ch R = 1 ,10545   ,137.5,124,124.7
BEGIN DESCRIPTION:
Merged US Survey NOR022BU
END DESCRIPTION:
XS GIS Cut Line= 5
     2303749.108      517426.277      2303824.24      517716.005
     2303967.775       517939.75     2303850.161      518784.434
     2303262.241      519369.137
#Sta/Elev= 30
       0 2733.49    56.7 2732.82   139.4 2710.86   209.6 2659.01   246.8 2638.26
   319.7 2639.39   780.6 2641.84   804.9 2644.71   825.1 2644.07     830 2643.74
   853.3 2644.93   958.3 2644.94   968.9 2639.99 1001.14 2636.98  1025.32639.769
  1043.1 2644.58  1108.4 2645.24  1125.6 2645.64  1271.1 2647.61  1309.7 2647.05
  1473.6 2647.14  1526.8 2647.23  1612.2 2646.92  1739.5 2646.66  1790.4    2646
  2069.5 2645.18  2156.4 2649.29  2172.3 2649.34  2193.6 2649.95  2247.1 2692.87
#Mann= 20 ,-1,0
       0      .1       0   319.7     .04       0   804.9    .016       0
   825.1     .04       0     830    .016       0   853.3     .04       0
   968.9    .045       0  1025.3     .04       0  1108.4    .016       0
  1125.6     .04       0  1271.1    .016       0  1309.7     .04       0
  1473.6     .05       0  1526.8     .04       0  1612.2     .05       0
  1739.5     .04       0  1790.4     .05       0  2069.5     .03       0
  2156.4    .016       0  2172.3     .04       0
#XS Ineff= 3 ,-1
  236.66     910 2657.76     910     920 2642.63    1105  2247.1    2646
Permanent Ineff=
       F       F       F
#Block Obstruct= 3 ,-1
   422.7  466.94 2661.85 1866.26 1928.05 2666.69 2087.17 2129.13 2668.66
Bank Sta=968.9,1025.3
XS Rating Curve= 0 ,0
Exp/Cntr=0.5,0.3

Type RM Length L Ch R = 3 ,10495   ,,,
BEGIN DESCRIPTION:
Wesley Chapel Road.
Merged Survey NOR018-022: 2.6' high railing (extends 110' LOB, 130' ROB from aerial imagery), 3' circular piers.
From photographs: shallow flows with cobbled channel below.
END DESCRIPTION:
Bridge Culvert--1,0,-1,-1, 0
Deck Dist Width WeirC Skew NumUp NumDn MinLoCord MaxHiCord MaxSubmerge Is_Ogee
43,27,2.6,0, 60, 60, , , 0.98, 0, 0,0,,
 246.088 256.644 268.721 284.958  356.03  433.68 466.113 557.182 606.082 638.657
  693.96 726.755 783.686 807.457 876.365 888.525 957.434   957.6 1074.281076.202
1131.4691135.7851172.2661191.1191253.3341353.355 1381.911404.3091413.5231427.345
1445.773 1468.081493.8521544.2191555.5531583.8871623.7321640.5541651.8881691.555
1708.556 1759.261798.7891810.0831821.3771833.2251889.5161923.8941935.2271946.085
1951.7411962.5511969.2281973.8451985.683 2002.082007.7272011.1382016.7952020.229
2638.804 2638.16 2639.432640.5792641.5052642.9062643.2512643.5092643.2052643.784
2643.873 2644.212645.5742646.5372648.6372651.5972652.7532652.8122652.8932652.542
2651.2262648.4762647.498 2647.282647.2692646.2382646.8762647.0112646.8222645.871
2645.2812646.6722645.9242646.4662646.9832646.5632647.2172646.5332646.751 2646.03
2646.2462644.9642645.7812646.7322646.0312645.903 2645.522646.0672645.6562645.825
2645.3982645.556 2644.832644.8812644.2992644.3262642.7392642.9382644.2592644.656
                                                                                
                                                         2647.71 2647.53
                                                                                
                                                                                
                                                                                
                                                                                
 171.088 181.644 193.721 209.958  281.03  358.68 391.113 482.182 531.082 563.657
  618.96 651.755 708.686 732.457 801.365 813.525 882.434   882.6  999.281001.202
1056.4691060.7851097.2661116.1191178.3341278.355 1306.911329.3091338.5231352.345
1370.773 1393.081418.8521469.2191480.5531508.8871548.7321565.5541576.8881616.555
1633.556 1684.261723.7891735.0831746.3771758.2251814.5161848.8941860.2271871.085
1876.7411887.5511894.2281898.8451910.683 1927.081932.7271936.1381941.7951945.229
2638.804 2638.16 2639.432640.5792641.5052642.9062643.2512643.5092643.2052643.784
2643.873 2644.212645.5742646.5372648.6372651.5972652.7532652.8122652.8932652.542
2651.2262648.4762647.498 2647.282647.2692646.2382646.8762647.0112646.8222645.871
2645.2812646.6722645.9242646.4662646.9832646.5632647.2172646.5332646.751 2646.03
2646.2462644.9642645.7812646.7322646.0312645.903 2645.522646.0672645.6562645.825
2645.3982645.556 2644.832644.8812644.2992644.3262642.7392642.9382644.2592644.656
                                                                                
                                                         2647.71 2647.53
                                                                                
                                                                                
                                                                                
                                                                                
Pier Skew, UpSta & Num, DnSta & Num=  ,1001.14, 2 ,930.36, 2 , 0 , 0 , 0 ,,
       2       2
 2637.02    2650
       2       2
 2635.54    2650
BR Coef=-1 ,-1 , 0 ,, 0 ,,,0.8,0,1.2,0,
WSPro=,,,, 1 ,,,, 0 ,,,, 0 ,,,,-1 ,-1 ,-1 , 0 , 0 , 0 , 0 , 0
BR U #Sta/Elev= 30
       0 2733.49    56.7 2732.82   139.4 2710.86   209.6 2659.01   246.8 2638.26
   319.7 2639.39   780.6 2641.84   804.9 2644.71   825.1 2644.07     830 2643.74
   853.3 2644.93   958.3 2644.94   968.9 2639.99 1001.14 2636.98  1025.32639.769
  1043.1 2644.58  1108.4 2645.24  1125.6 2645.64  1271.1 2647.61  1309.7 2647.05
  1473.6 2647.14  1526.8 2647.23  1612.2 2646.92  1739.5 2646.66  1790.4    2646
  2069.5 2645.18  2156.4 2649.29  2172.3 2649.34  2193.6 2649.95  2247.1 2692.87
BR U #Mann= 20
       0      .1   319.7     .04   804.9    .016   825.1     .04     830    .016
   853.3     .04   968.9     .04  1025.3     .04  1108.4    .016  1125.6     .04
  1271.1    .016  1309.7     .04  1473.6     .05  1526.8     .04  1612.2     .05
  1739.5     .04  1790.4     .05  2069.5     .03  2156.4    .016  2172.3     .04
BR D #Sta/Elev= 30
       0 2679.89    71.1 2667.78   124.8 2653.49   149.1 2642.42   165.6 2642.61
   178.5 2639.72   201.6 2640.21   261.2 2636.91   790.6    2642   899.1 2639.71
  930.36 2635.54   960.3    2640   968.3 2643.31  1037.5 2643.27  1057.2 2645.43
  1166.2 2643.44  1355.3 2645.29  1388.2 2645.81  1473.6 2646.41  1608.4 2644.99
  1688.6  2645.7  1859.3 2645.76  1889.4 2644.01  1904.6 2642.42    2011 2648.63
  2034.7 2648.82  2078.9 2684.57  2094.9    2696  2111.9 2705.06  2126.6 2719.99
BR D #Mann= 12
       0      .1   165.6    .016   201.6     .05   899.1     .04   960.3     .04
  1355.3    .016  1388.2     .04  1473.6     .05  1608.4     .04  1688.6     .05
  1889.4     .03    2011      .1
BC Design=,, 0 ,, 0 ,,,,,,
BC Use User HTab Curves=0
BC User HTab FreeFlow(D)= 0

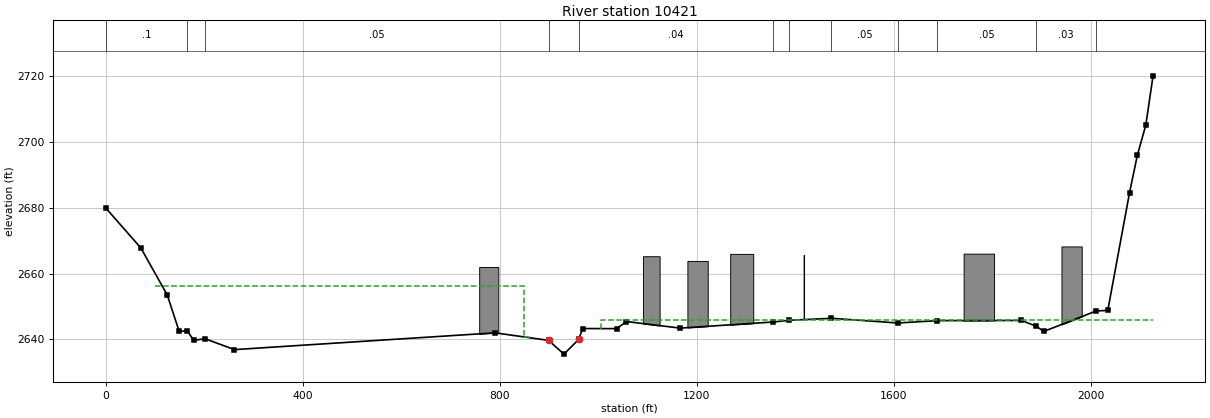
Type RM Length L Ch R = 1 ,10421   ,208.8,211.7,211.7
BEGIN DESCRIPTION:
Merged DS Survey NOR018BD
END DESCRIPTION:
XS GIS Cut Line= 5
     2303619.191      517460.356     2303694.324      517750.083
     2303837.858      517973.828     2303720.244      518818.513
     2303219.188      519319.568
#Sta/Elev= 30
       0 2679.89    71.1 2667.78   124.8 2653.49   149.1 2642.42   165.6 2642.61
   178.5 2639.72   201.6 2640.21   261.2 2636.91   790.6    2642   899.1 2639.71
  930.36 2635.54   960.3    2640   968.3 2643.31  1037.5 2643.27  1057.2 2645.43
  1166.2 2643.44  1355.3 2645.29  1388.2 2645.81  1473.6 2646.41  1608.4 2644.99
  1688.6  2645.7  1859.3 2645.76  1889.4 2644.01  1904.6 2642.42    2011 2648.63
  2034.7 2648.82  2078.9 2684.57  2094.9    2696  2111.9 2705.06  2126.6 2719.99
#Mann= 12 ,-1,0
       0      .1       0   165.6    .016       0   201.6     .05       0
   899.1    .045       0   960.3     .04       0  1355.3    .016       0
  1388.2     .04       0  1473.6     .05       0  1608.4     .04       0
  1688.6     .05       0  1889.4     .03       0    2011      .1       0
#XS Ineff= 3 ,-1
   98.97     850 2656.34     850     860 2640.85    1005  2126.6    2646
Permanent Ineff=
       F       F       F
#Block Obstruct= 7 ,-1
  758.25  797.07 2661.98 1090.96 1124.63 2665.25 1181.04 1222.31 2663.82
 1267.97 1314.75 2665.96 1416.98 1417.97 2665.61 1741.95 1803.77 2666.04
 1940.65 1981.79 2668.22
Bank Sta=899.1,960.3
XS Rating Curve= 0 ,0
Exp/Cntr=0.5,0.3