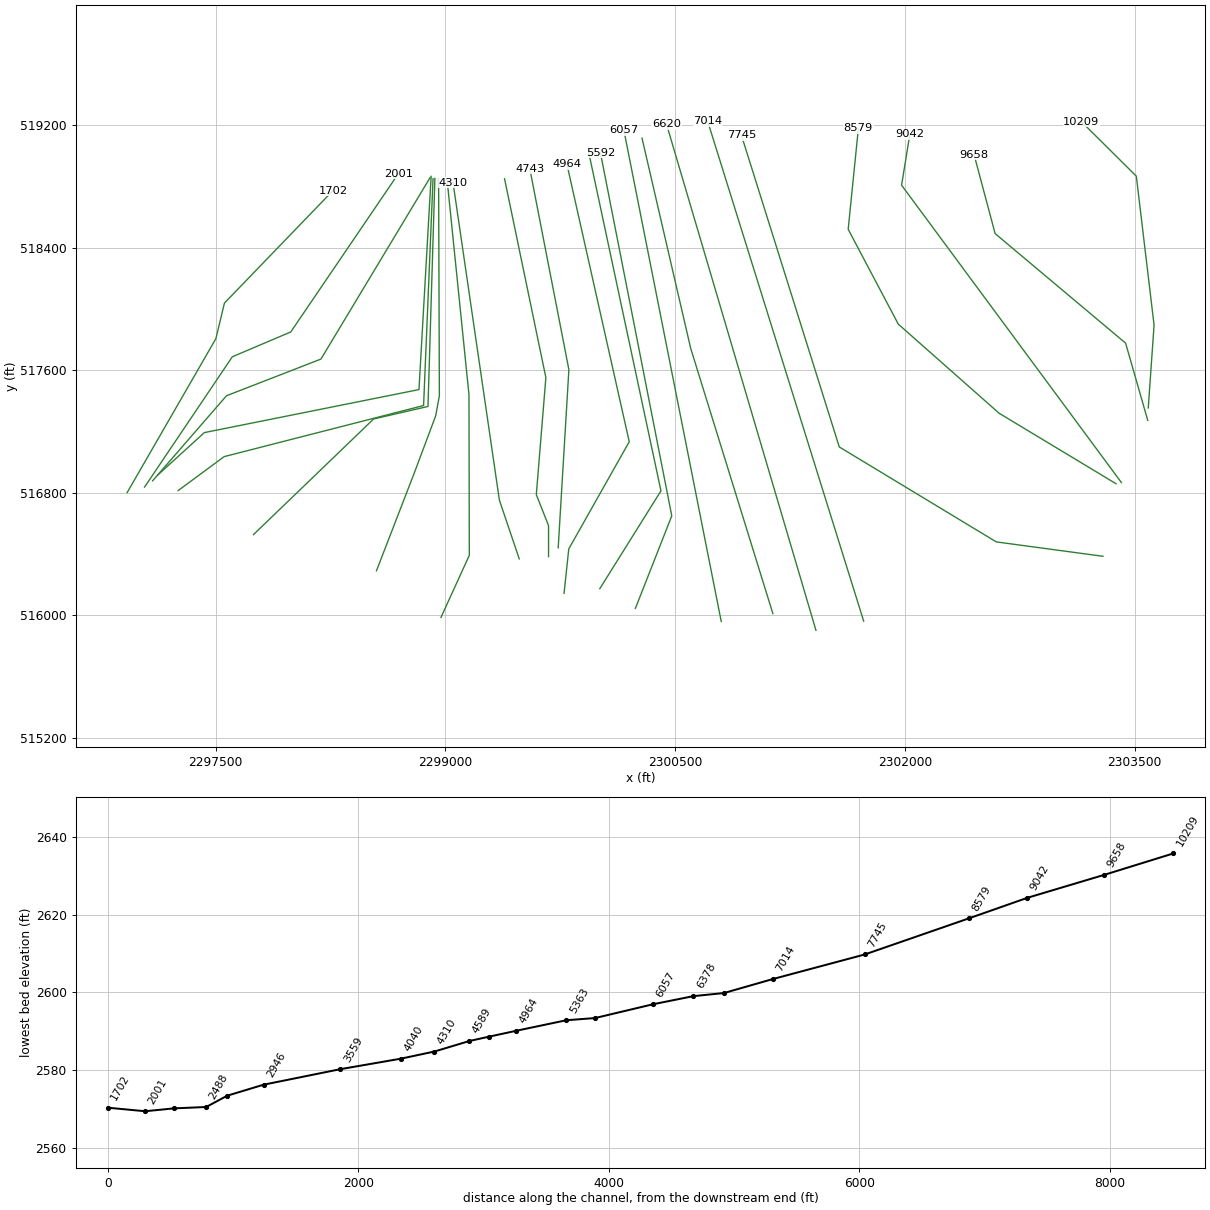
HEC-RAS study NRTHFRK.prj: NRTHFRK

--- NRTHFRK.g01 (geometry) --- (continued)

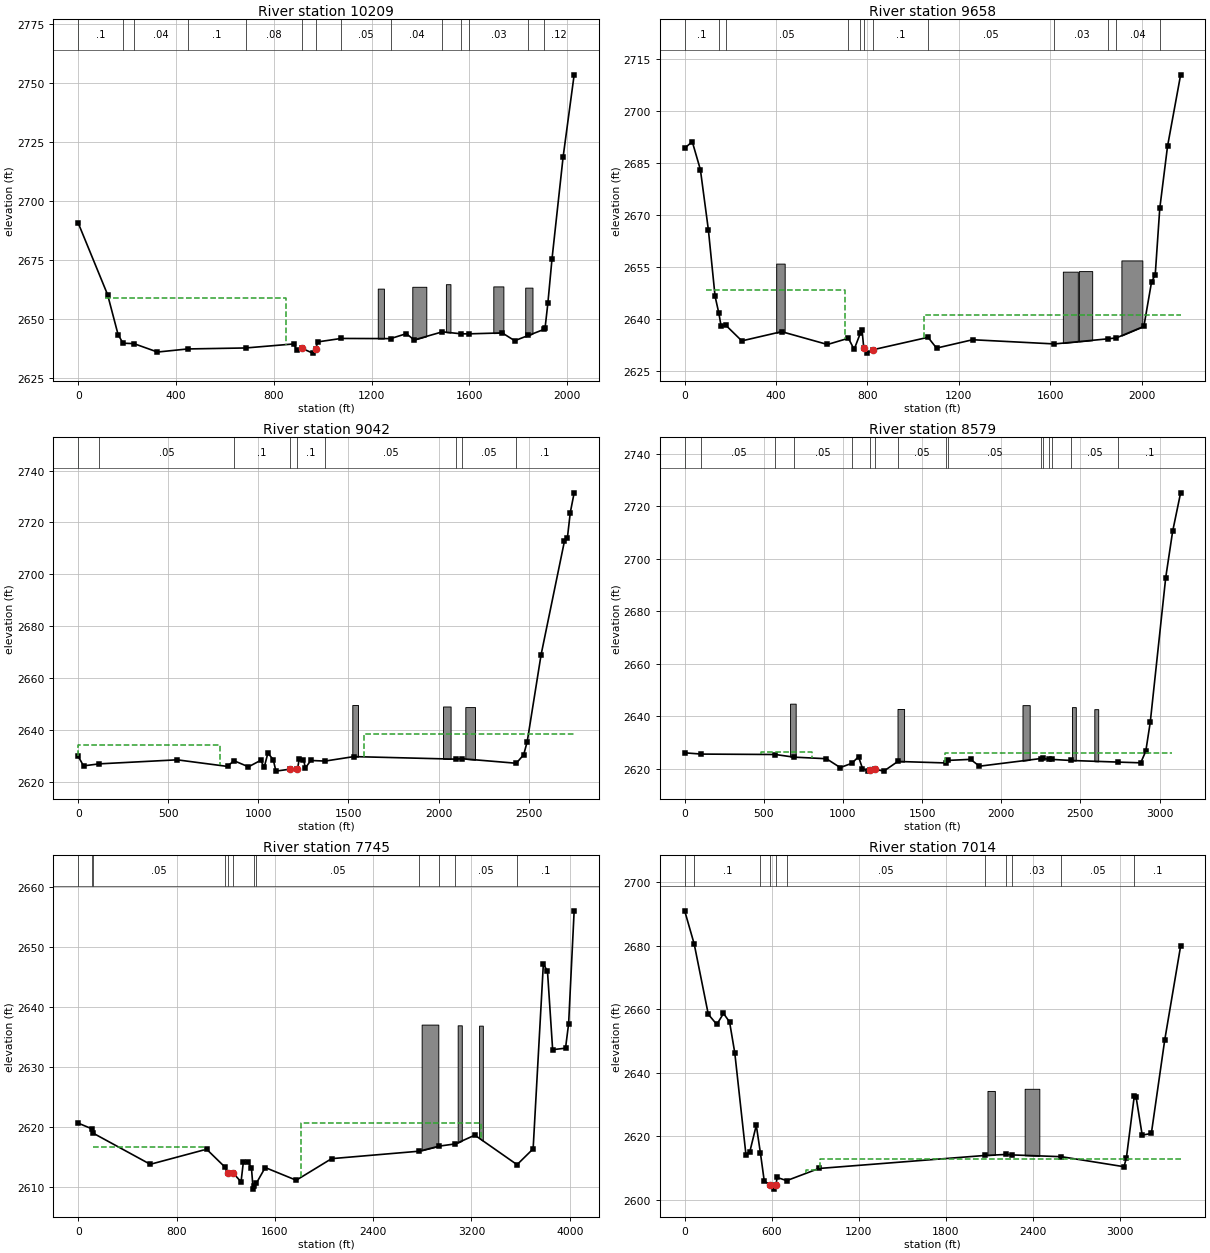
Type RM Length L Ch R = 1 ,10209   ,274.2,551.4,568.4
XS GIS Cut Line= 4
      2303588.85      517354.453     2303626.778      517895.729
     2303510.848      518868.369     2303151.882      519224.841
#Sta/Elev= 30
       0 2690.85   120.1 2660.51   163.1 2643.57   183.2 2639.94   227.9 2639.75
   324.2 2636.19   447.8  2637.5   685.1 2637.92     881 2639.62   894.5 2636.98
   915.3 2637.73     959 2635.73   971.7 2637.54   979.1 2640.48  1075.3 2641.95
  1277.2 2641.88  1341.6 2643.97  1373.9 2641.33  1489.3 2644.76    1567  2643.9
  1598.1  2643.9  1733.9  2644.3  1784.8 2640.99  1841.2 2643.24  1903.6 2645.75
  1909.3 2646.57  1920.6 2656.99  1937.4 2675.61  1982.8  2718.8    2028 2753.65
#Mann= 14 ,-1,0
       0      .1       0   183.2    .016       0   227.9     .04       0
   447.8      .1       0   685.1     .08       0   915.3    .045       0
   971.7      .1       0  1075.3     .05       0  1277.2     .04       0
  1489.3    .016       0    1567     .04       0  1598.1     .03       0
  1841.2     .04       0  1903.6     .12       0
#XS Ineff= 1 ,-1
  107.57  847.682659.272
Permanent Ineff=
       F
#Block Obstruct= 5 ,-1
 1224.92 1250.05 2663.06 1366.13 1423.43 2663.84  1503.6 1522.13 2664.94
 1697.39 1738.58    2664 1827.91 1857.61 2663.48
Bank Sta=915.3,971.7
XS Rating Curve= 0 ,0
Exp/Cntr=0.3,0.1

Type RM Length L Ch R = 1 ,9658    ,714.7,615.8,529.2
XS GIS Cut Line= 4
     2303585.412      517273.297     2303441.027      517777.524
     2302589.107      518493.122      2302451.85      519008.606
#Sta/Elev= 30
       0 2689.31    33.2 2691.19    68.8  2683.1   103.9 2665.67     133 2646.61
   149.7 2641.68   159.4 2637.99   178.8 2638.34     250 2633.75   424.3 2636.41
   624.9 2632.71   716.7 2634.51   741.6 2631.28     769    2636   776.4 2636.83
   783.9 2631.56   797.6 2630.22   825.1 2631.21    1065 2634.78  1102.3 2631.67
  1260.2 2634.08  1618.5 2632.87  1853.6 2634.35  1889.6 2634.62  2009.7 2637.95
  2043.2 2650.71  2059.4 2652.82  2079.2 2671.92  2113.2 2689.85  2170.5 2710.46
#Mann= 12 ,-1,0
       0      .1       0   149.7    .016       0   178.8     .05       0
   716.7     .08       0     769      .1       0   783.9    .045       0
   825.1      .1       0    1065     .05       0  1618.5     .03       0
  1853.6    .016       0  1889.6     .04       0  2079.2      .1       0
#XS Ineff= 2 ,-1
   94.66  701.38 2648.54 1045.61  2170.5 2641.22
Permanent Ineff=
       F       F
#Block Obstruct= 4 ,-1
  400.52  437.64 2656.03 1655.09 1720.55 2653.71 1725.22 1783.47 2653.87
 1911.37 2002.93 2656.95
Bank Sta=783.9,825.1
XS Rating Curve= 0 ,0
Exp/Cntr=0.3,0.1

Type RM Length L Ch R = 1 ,9042    ,431.7,463,454.1
XS GIS Cut Line= 3
     2303413.628      516866.639     2301978.464       518809.31
     2302032.427      519142.282
#Sta/Elev= 30
       0 2629.99    29.4 2626.32   117.3 2627.09   549.1 2628.64   828.7  2626.1
   863.8 2628.32   944.9 2625.95  1012.7 2628.44  1032.5 2625.81  1052.6 2631.21
  1082.3 2628.76  1097.3 2624.29  1176.8 2625.06  1216.6 2624.99    1227 2629.04
  1249.9 2628.67  1261.4 2625.59  1291.2 2628.39    1370 2628.16  1530.2 2629.88
  2096.9 2628.89    2128 2629.08  2431.4 2627.32  2472.5 2630.61  2492.2 2635.69
  2569.1  2669.1  2698.8 2712.83    2715 2714.04  2731.2 2723.83  2752.6 2731.41
#Mann= 9 ,-1,0
       0     .04       0   117.3     .05       0   863.8      .1       0
  1176.8    .045       0  1216.6      .1       0    1370     .05       0
  2096.9    .016       0    2128     .05       0  2431.4      .1       0
#XS Ineff= 2 , 0
          786.712634.441  1585.2         2638.44
Permanent Ineff=
       F       F
#Block Obstruct= 3 ,-1
 1521.29 1553.06 2649.74 2024.91 2066.82 2649.17 2148.56 2202.43 2648.94
Bank Sta=1176.8,1216.6
XS Rating Curve= 0 ,0
Exp/Cntr=0.3,0.1

Type RM Length L Ch R = 1 ,8579    ,816.2,834.6,810.2
XS GIS Cut Line= 5
2303378.57394614 516859.194227032302615.33130961517319.520905863
2301956.96436725517901.7341380822301629.87539186518521.177656077
2301696.37003484 519180.01942589
#Sta/Elev= 30
       0 2626.02   105.6 2625.54   572.7 2625.38   689.5 2624.38   895.5 2623.77
   982.6  2620.4  1055.7 2622.02  1098.4 2624.52  1123.3 2620.04  1157.2 2619.04
  1167.9  2619.6  1199.9 2619.74  1258.6 2619.07  1346.7 2622.73  1648.4 2622.16
  1664.4 2623.13  1805.9 2623.53  1862.1 2620.92    2249 2623.83  2264.7 2623.88
  2298.8 2623.55  2322.9  2623.5  2442.3  2623.1    2740 2622.48  2880.8 2622.21
  2912.9 2626.67  2941.1  2637.7  3038.8 2692.88  3082.6 2710.53  3132.9 2725.19
#Mann= 16 ,-1,0
       0     .04       0   105.6     .05       0   572.7     .04       0
   689.5     .05       0  1055.7     .08       0  1167.9    .045       0
  1199.9      .1       0  1346.7     .05       0  1648.4    .016       0
  1664.4     .05       0    2249     .03       0  2264.7     .04       0
  2298.8    .016       0  2322.9     .03       0  2442.3     .05       0
    2740      .1       0
#XS Ineff= 2 ,-1
  484.84  807.44 2626.47 1641.99 3080.572626.129
Permanent Ineff=
       F       F
#Block Obstruct= 5 ,-1
  665.75  701.16 2644.77 1344.48 1385.99 2642.75 2133.98 2179.46 2644.21
 2446.44 2470.69 2643.45 2587.72 2612.29 2642.67
Bank Sta=1167.9,1199.9
XS Rating Curve= 0 ,0
Exp/Cntr(USF)=0,0
Exp/Cntr=0.3,0.1

Type RM Length L Ch R = 1 ,7745    ,730.2,730.7,448.4
XS GIS Cut Line= 4
      2303293.08      516385.218      2302596.92      516479.153
2301571.73413375517099.441354572     2300932.732      519136.109
#Sta/Elev= 30
       0 2620.69   109.9 2619.75     118 2619.06   586.2 2613.84  1044.6 2616.35
  1193.2 2613.39  1217.6 2612.44  1257.9 2612.45  1324.9 2610.92  1343.8 2614.23
  1381.2 2614.19  1409.4 2613.27  1423.3 2609.71  1432.6 2610.27  1450.2 2610.72
  1521.5  2613.3    1774 2611.19  2061.8 2614.78  2774.5 2616.02  2935.6 2616.86
  3069.7 2617.24  3227.3 2618.69  3570.7 2613.78  3701.5 2616.41  3784.8 2647.19
  3818.4 2645.93  3860.3 2632.91  3965.1 2633.16  3990.3 2637.24  4035.3 2656.01
#Mann= 12 ,-1,0
       0     .04       0   109.9    .016       0     118     .05       0
  1193.2     .08       0  1217.6    .045       0  1257.9     .08       0
  1432.6    .045       0  1450.2     .05       0  2774.5    .016       0
  2935.6    .016       0  3069.7     .05       0  3570.7      .1       0
#XS Ineff= 3 ,-1
  119.75 1025.62 2616.79 1815.83 3278.832620.634 3382.99  3829.4 2615.74
Permanent Ineff=
       F       F       F
#Block Obstruct= 3 ,-1
  2794.4 2930.07 2637.08 3087.64 3120.96 2636.96 3261.62  3292.1 2636.91
Bank Sta=1217.6,1257.9
XS Rating Curve= 0 ,0
Exp/Cntr=0.3,0.1

Type RM Length L Ch R = 1 ,7014    ,341,393.6,304.5
Node Name=C
XS GIS Cut Line= 2
     2301730.978      515961.747     2300712.994      519225.793
#Sta/Elev= 30
       0 2690.93    65.7 2680.48   162.8 2658.39   221.5  2655.2   267.6 2658.67
   309.5 2655.98   345.3 2646.29   422.6 2614.16   448.9 2615.14   493.6 2623.49
   522.4 2614.71   548.3 2606.04   586.3 2604.68     615 2603.41     629 2604.63
   637.4 2607.09   703.3 2606.08   924.8  2609.9  2068.2 2613.99  2218.4 2614.32
  2256.7 2614.17  2597.2 2613.61  3028.8 2610.46  3045.5 2613.33  3099.4 2632.58
  3112.5 2632.25  3154.2 2620.39  3217.3 2620.92  3309.5 2650.29  3419.1 2679.85
#Mann= 11 ,-1,0
       0     .12       0    65.7      .1       0   522.4     .08       0
   586.3    .045       0     629     .08       0   703.3     .05       0
  2068.2     .03       0  2218.4    .016       0  2256.7     .03       0
  2597.2     .05       0  3099.4      .1       0
#XS Ineff= 2 ,-1
   835.3  921.73 2609.52  932.43  3419.1 2612.88
Permanent Ineff=
       F       F
#Block Obstruct= 2 ,-1
 2087.53 2138.34 2634.29 2343.98 2444.95 2634.96
Bank Sta=586.3,629
XS Rating Curve= 0 ,0
Exp/Cntr=0.3,0.1

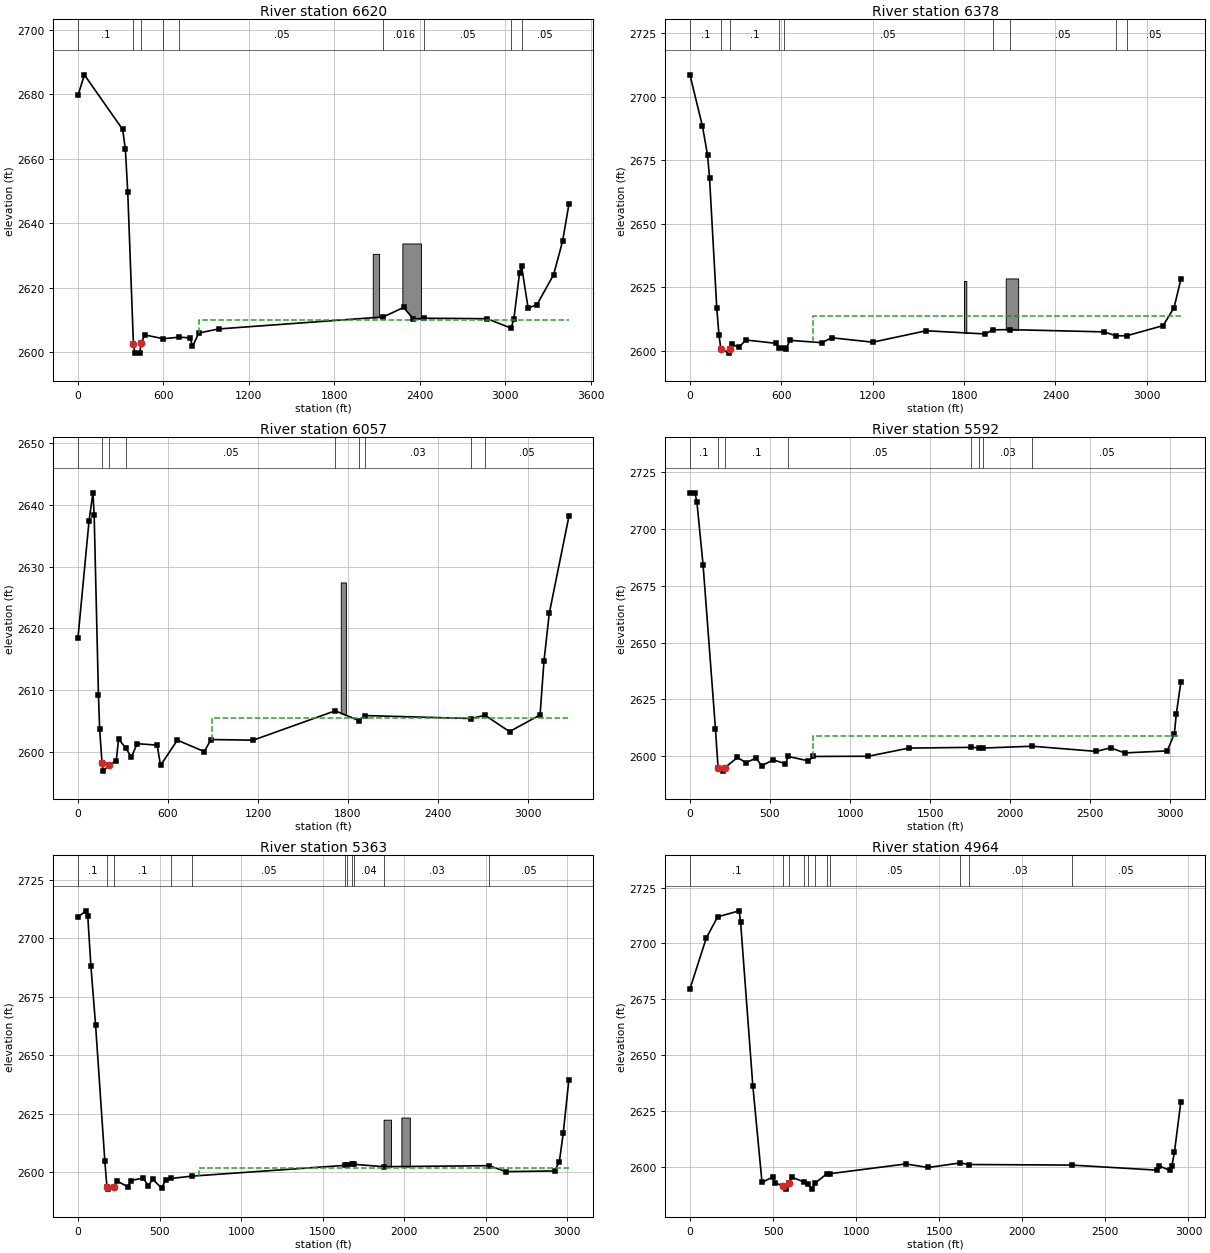
Type RM Length L Ch R = 1 ,6620    ,242,242.6,247.7
XS GIS Cut Line= 2
     2301419.376      515901.919     2300443.807      519207.974
#Sta/Elev= 30
       0 2679.59    45.1 2685.99   313.7 2669.07   332.9 2662.96   349.6 2649.54
   389.5 2602.52   399.6 2599.78   433.5 2599.79   444.1    2603   470.5 2605.41
   599.8 2604.23   712.4 2604.73   787.5 2604.49   804.1 2601.91   848.9 2606.01
   987.6 2607.27  2143.5 2610.99  2286.8 2613.94  2354.8 2610.34  2431.7 2610.59
  2872.7 2610.44  3041.1 2607.52  3060.4 2610.33  3100.3 2624.54  3114.6 2626.82
  3160.5 2613.74    3223 2614.81  3339.8 2624.09  3402.6 2634.46    3447 2645.87
#Mann= 9 ,-1,0
       0      .1       0   389.5    .045       0   444.1      .1       0
   599.8     .08       0   712.4     .05       0  2143.5    .016       0
  2431.7     .05       0  3041.1      .1       0  3114.6     .05       0
#XS Ineff= 2 , 0
                           849.9         2609.89
Permanent Ineff=
       F       F
#Block Obstruct= 2 ,-1
 2069.72 2114.17 2630.53 2277.66 2408.17 2633.75
Bank Sta=389.5,444.1
XS Rating Curve= 0 ,0
Exp/Cntr=0.3,0.1

Type RM Length L Ch R = 1 ,6378    ,320.9,321.2,282
XS GIS Cut Line= 3
2301138.21041463516010.7775387432300601.53563885517744.175377747
2300283.84884629519116.705695107
#Sta/Elev= 30
       0 2708.62    82.1 2688.42   115.6 2677.04   128.6 2668.17   176.4 2616.61
   190.9 2605.99   203.42600.575   257.9 2598.99  265.87 2600.57   274.7 2602.66
   320.8 2601.21   366.8 2604.17   567.8 2602.83   584.6 2600.88   615.5 2601.07
   630.6 2600.44   655.7 2604.03   865.1 2603.11   932.1 2605.03  1200.1  2603.3
  1551.1  2607.8  1938.8 2606.54    1988 2608.17  2104.4 2608.25  2718.9 2607.36
  2797.1 2605.83  2866.8 2605.81  3106.9 2609.83  3178.7 2616.92  3223.4 2628.08
#Mann= 9 ,-1,0
       0      .1       0   203.4    .045       0  265.87      .1       0
   584.6     .08       0   615.5     .05       0    1988    .016       0
  2104.4     .05       0  2797.1      .1       0  2866.8     .05       0
#XS Ineff= 2 , 0
                          807.23         2613.46
Permanent Ineff=
       F       F
#Block Obstruct= 2 ,-1
 1799.05 1814.58 2627.42 2073.55 2155.01 2628.41
Bank Sta=203.4,265.87
XS Rating Curve= 0 ,0
Exp/Cntr(USF)=0,0
Exp/Cntr=0.3,0.1

Type RM Length L Ch R = 1 ,6057    ,481.1,464.1,274.2
XS GIS Cut Line= 2
     2300801.158      515959.254     2300165.257      519169.639
#Sta/Elev= 30
       0 2618.44    73.9 2637.42    99.8 2641.94     108 2638.34   136.5 2609.26
   144.7 2603.65   160.7 2598.16   169.1 2596.91   204.5 2597.83   254.8 2598.59
   271.1 2602.09     320 2600.61   356.4 2599.14   393.9 2601.35     528 2601.12
   550.4 2597.83   662.6 2601.92     842 2600.07   886.8 2602.02  1168.2 2601.92
  1714.8 2606.67  1873.6 2605.08  1915.3  2605.9  2619.6 2605.42  2713.6 2605.94
  2876.8 2603.31  3080.6    2606  3106.5 2614.67  3141.8 2622.43  3272.8 2638.12
#Mann= 9 ,-1,0
       0      .1       0   160.7    .045       0   204.5      .1       0
     320     .05       0  1714.8     .03       0  1873.6    .016       0
  1915.3     .03       0  2619.6     .04       0  2713.6     .05       0
#XS Ineff= 2 , 0
                          891.57         2605.51
Permanent Ineff=
       F       F
#Block Obstruct= 1 ,-1
 1752.09 1786.05 2627.44
Bank Sta=160.7,204.5
XS Rating Curve= 0 ,0
Exp/Cntr=0.3,0.1

Type RM Length L Ch R = 1 ,5592    ,234.2,229.8,180.5
XS GIS Cut Line= 3
2300240.66811721516044.7052544532300478.16212718 516649.23546165
2300012.42712061519021.091223561
#Sta/Elev= 30
       0 2715.85    30.8 2716.02    43.5 2711.99    82.2 2684.19   159.5 2611.96
   175.82594.768   206.8 2593.35   219.1 2594.93     297 2599.36   348.7  2597.1
   414.3 2599.08   447.5 2595.69   520.5 2598.31   596.3 2596.62   615.1  2599.8
   739.1 2597.88   771.7 2599.81  1114.2 2599.91  1366.9  2603.5  1757.8 2603.83
  1803.4 2603.66  1831.6 2603.52  2136.7 2604.33  2538.8 2602.05  2627.4 2603.63
  2716.2 2601.38  2981.8 2602.26    3026 2609.89  3038.2 2618.54  3066.7  2632.6
#Mann= 8 ,-1,0
       0      .1       0   175.8    .045       0   219.1      .1       0
   615.1     .05       0  1757.8    .016       0  1803.4     .04       0
  1831.6     .03       0  2136.7     .05       0
#XS Ineff= 2 , 0
                          771.08         2609.02
Permanent Ineff=
       F       F
Bank Sta=175.8,219.1
XS Rating Curve= 0 ,0
Exp/Cntr(USF)=0,0
Exp/Cntr=0.3,0.1

Type RM Length L Ch R = 1 ,5363    ,372.8,398.4,339.1
XS GIS Cut Line= 3
     2300008.443      516173.6362300407.63111041516812.556963279
2299936.87743483 519019.45013716
#Sta/Elev= 30
       0 2709.28    52.3 2711.82    59.9 2709.71    79.6 2688.01   107.9 2663.07
   164.9 2604.63  177.35  2593.9   183.4 2592.78     223 2593.74   240.4 2596.22
     306 2593.76   324.9 2596.47   400.4 2597.52     432 2594.08     457 2597.12
   513.6 2593.13   537.1 2596.82   570.2 2597.34   697.5 2598.33  1637.4 2602.95
  1650.1 2602.96  1682.4 2603.58  1693.9 2603.38  1874.7 2602.37  2520.9 2602.81
  2623.1 2600.27  2921.7 2600.56  2951.3 2604.51  2974.9 2616.61  3009.9 2639.67
#Mann= 11 ,-1,0
       0      .1       0  177.35    .045       0     223      .1       0
   570.2     .04       0   697.5     .05       0  1637.4     .03       0
  1650.1     .05       0  1682.4    .016       0  1693.9     .04       0
  1874.7     .03       0  2520.9     .05       0
#XS Ineff= 2 , 0
                          743.35         2601.75
Permanent Ineff=
       F       F
#Block Obstruct= 2 ,-1
 1873.85 1919.47 2622.48 1982.94 2034.63 2623.39
Bank Sta=177.35,223
XS Rating Curve= 0 ,0
Exp/Cntr=0.3,0.1

Type RM Length L Ch R = 1 ,4964    ,183.4,220.9,259.1
XS GIS Cut Line= 4
2299774.93311064516143.4040637912299805.77648856516433.331816222
2300200.57172591517133.4764949662299793.43913739518947.067116557
#Sta/Elev= 30
       0 2679.63    98.3 2702.39   166.7 2711.89   296.4 2714.58     305 2709.37
   378.6 2636.15   433.7 2593.09     498 2595.48   510.5    2593   557.7 2591.53
   580.7 2590.22   597.8 2592.99   612.8 2595.39   686.3 2593.33   709.3 2592.44
   736.2 2590.08   752.5 2592.74   824.7 2596.98   845.2 2597.01    1298 2601.33
  1433.6 2599.76  1624.4 2601.78    1678 2601.09  2296.2 2600.84  2808.7 2598.58
    2821 2600.57  2886.6  2598.5    2900 2600.49  2915.2  2606.5  2954.1 2629.23
#Mann= 11 ,-1,0
       0      .1       0   557.7    .045       0   597.8      .1       0
   686.3     .06       0   709.3    .045       0   752.5     .06       0
   824.7    .016       0   845.2     .05       0  1624.4    .016       0
    1678     .03       0  2296.2     .05       0
Bank Sta=557.7,597.8
XS Rating Curve= 0 ,0
Exp/Cntr(USF)=0,0
Exp/Cntr=0.3,0.1

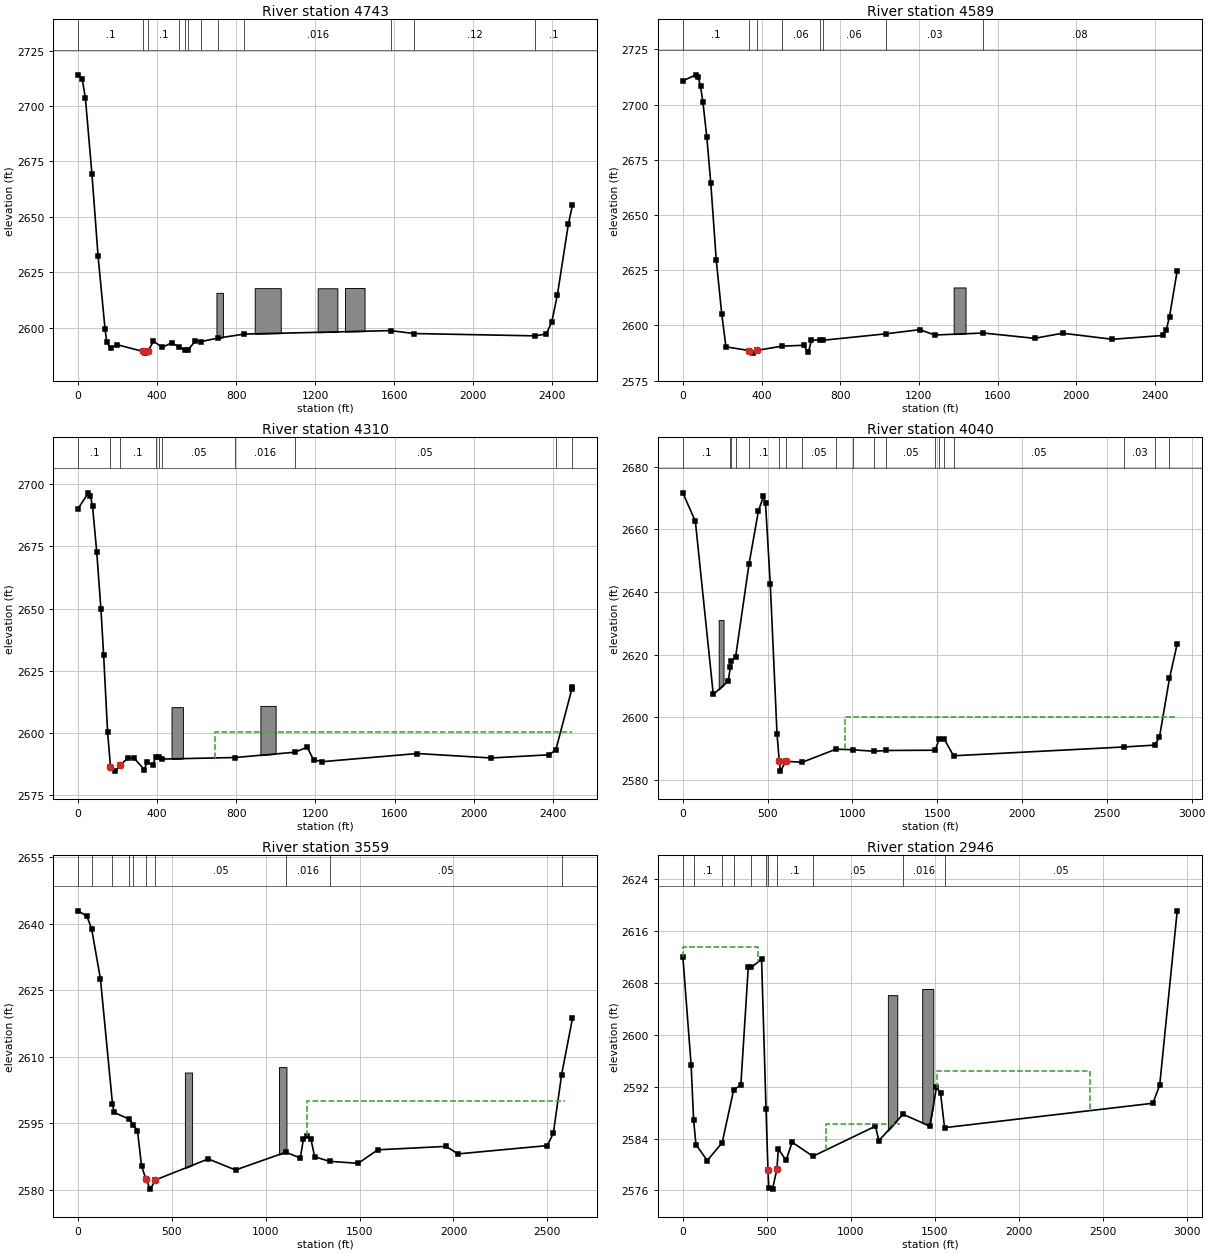
Type RM Length L Ch R = 1 ,4743    ,111.6,154.3,167.2
XS GIS Cut Line= 3
     2299736.726      516440.367     2299806.525      517604.512
     2299551.358      518916.647
#Sta/Elev= 30
       0 2714.05    20.8 2712.26    36.9 2703.41    69.7 2669.53     101 2632.19
   136.3 2599.36   145.1 2593.38   165.1 2590.82   197.2 2592.35   329.4 2589.28
   337.4 2588.54   353.4  2589.3   381.5 2593.93   425.6 2591.14   473.7 2593.23
   509.7 2591.36   541.8  2589.8   553.8 2589.75   593.9 2594.04   621.9 2593.76
   709.1 2595.33   842.3 2597.14  1581.6  2598.7  1700.7 2597.38  2315.1 2596.33
  2369.7 2597.18  2397.5 2602.38  2426.1 2614.59  2482.2 2646.75    2503 2655.37
#Mann= 12 ,-1,0
       0      .1       0   329.4    .045       0   353.4      .1       0
   509.7     .05       0   541.8    .045       0   553.8     .05       0
   621.9     .04       0   709.1     .05       0   842.3    .016       0
  1581.6     .05       0  1700.7     .12       0  2315.1      .1       0
#Block Obstruct= 4 ,-1
  700.24  733.11 2615.73  894.04 1025.77 2617.84 1212.72 1312.46 2617.79
 1350.91 1450.12 2617.92
Bank Sta=329.4,353.4
XS Rating Curve= 0 ,0
Exp/Cntr=0.3,0.1

Type RM Length L Ch R = 1 ,4589    ,254.8,279.1,266.6
XS GIS Cut Line= 5
2299673.76683107516383.2730138612299673.76683107516585.636416383
 2299593.8207955516787.9998189042299656.27863579517552.483783985
2299386.46076576  518851.6068619
#Sta/Elev= 30
       0 2710.76    65.9  2713.5    77.9  2712.7    89.9 2708.29   101.9 2701.21
   121.9 2685.23   141.9 2664.56   169.9 2629.51   197.9 2605.04   219.1  2590.3
   335.8 2588.62   354.3 2587.44  378.62 2588.73   505.4 2590.61   613.8 2590.98
   637.8 2587.79   653.9 2593.22   697.8 2593.49   710.1 2593.24  1031.7 2596.18
    1204 2598.06  1281.7 2595.65  1528.1 2596.55  1788.2 2594.14  1931.2 2596.46
  2184.5 2593.71  2441.9 2595.45  2458.2 2598.02  2474.6 2603.96  2513.8 2624.77
#Mann= 8 ,-1,0
       0      .1       0   335.8    .045       0  378.62     .08       0
   505.4     .06       0   697.8    .016       0   710.1     .06       0
  1031.7     .03       0  1528.1     .08       0
#Block Obstruct= 1 ,-1
 1376.94 1437.55 2617.19
Bank Sta=335.8,378.62
XS Rating Curve= 0 ,0
Exp/Cntr(USF)=0,0
Exp/Cntr=0.3,0.1

Type RM Length L Ch R = 1 ,4310    ,275.6,269.7,204.8
XS GIS Cut Line= 3
     2299482.459      516368.076     2299352.833      516751.969
     2299050.372      518824.961
#Sta/Elev= 30
       0 2690.17    51.8 2696.47    61.9 2695.35    72.9 2691.06      94  2672.8
   115.2 2649.84   128.9 2631.37   148.9 2600.53   163.6 2586.49   186.9 2584.73
   212.3 2587.05   250.3 2589.99     284 2589.88   334.7 2585.33   347.4 2588.28
   376.9 2587.29     394 2590.43   410.5 2590.46   422.6 2589.57   794.9  2590.2
  1094.7 2592.31  1158.3 2594.34  1190.6 2589.28  1235.8 2588.53  1716.1  2591.8
    2088 2590.01  2379.1 2591.28  2415.5 2593.14  2496.3 2617.55  2500.1 2618.47
#Mann= 10 ,-1,0
       0      .1       0   163.6    .045       0   212.3      .1       0
     394     .05       0   410.5    .016       0   422.6     .05       0
   794.9    .016       0  1094.7     .05       0  2415.5      .1       0
  2496.3     .12       0
#XS Ineff= 2 , 0
                          691.91         2600.54
Permanent Ineff=
       F       F
#Block Obstruct= 2 ,-1
   472.3  529.81 2610.41  921.68  998.77 2610.92
Bank Sta=163.6,212.3
XS Rating Curve= 0 ,0
Exp/Cntr=0.3,0.1

Type RM Length L Ch R = 1 ,4040    ,491.8,481.1,413.6
Node Name=B
XS GIS Cut Line= 4
 2298971.5124667515986.0587415132299156.50175971516391.604649446
 2299154.3248232517440.5753669032299010.51484062518853.502815484
#Sta/Elev= 30
       0 2671.67    73.8 2662.54   179.3 2607.36   267.2 2611.58   280.6 2616.25
   284.8 2617.87   310.8 2619.23   390.3 2649.03   445.7 2665.92   475.3  2670.5
   487.3 2668.41   515.5 2642.56   555.2 2594.76  568.49 2585.98   575.3 2582.88
   607.3 2586.03   703.3 2585.69   902.7 2589.89  1003.3 2589.69  1127.3 2589.21
  1199.3 2589.47  1487.3 2589.55  1510.9 2593.03    1541 2593.12  1595.9 2587.78
  2602.9 2590.59  2781.8 2591.18  2810.1 2593.66  2869.3 2612.47  2914.9 2623.48
#Mann= 19 ,-1,0
       0      .1       0   280.6     .04       0   284.8    .016       0
   310.8     .04       0   390.3      .1       0  568.49    .045       0
   607.3      .1       0   703.3     .05       0   902.7     .03       0
  1003.3     .05       0  1127.3     .03       0  1199.3     .05       0
  1487.3     .03       0  1510.9    .016       0    1541     .03       0
  1595.9     .05       0  2602.9     .03       0  2781.8      .1       0
  2869.3     .12       0
#XS Ineff= 2 , 0
                          955.25            2600
Permanent Ineff=
       F       F
#Block Obstruct= 1 ,-1
  211.44  239.76 2631.09
Bank Sta=568.49,607.3
XS Rating Curve= 0 ,0
Exp/Cntr(USF)=0,0
Exp/Cntr=0.3,0.1

Type RM Length L Ch R = 1 ,3559    ,623.9,613,510.1
XS GIS Cut Line= 5
2298550.28469112516290.3717573982298798.31166112516932.268501992
2298936.80459436517302.2148066562298960.99071695517433.722498824
2298956.10027219518850.837205919
#Sta/Elev= 30
       0 2642.97    46.9 2641.73    71.6 2638.97   118.8 2627.63     183 2599.43
   191.7 2597.48   273.2 2595.94   294.6 2594.67   316.1 2593.39   337.7 2585.48
   361.12582.407   384.7 2580.19   411.9 2582.26   693.3    2587   838.6 2584.51
  1106.5 2588.51  1183.8 2587.21  1200.1 2591.44  1220.3 2592.25  1240.3 2591.49
  1260.3 2587.48  1339.9 2586.46  1492.2 2586.01  1596.3 2589.06  1960.3 2589.83
  2024.3 2588.14  2500.3 2590.01  2532.1 2592.84  2576.2 2606.03    2634 2618.74
#Mann= 10 ,-1,0
       0     .12       0    71.6      .1       0     183     .04       0
   273.2    .016       0   294.6      .1       0   361.1    .045       0
   411.9     .05       0  1106.5    .016       0  1339.9     .05       0
  2576.2      .1       0
#XS Ineff= 1 ,-1
 1218.44 2595.092600.017
Permanent Ineff=
       F
#Block Obstruct= 2 ,-1
  568.81   607.2 2606.49    1070    1110 2607.72
Bank Sta=361.1,411.9
XS Rating Curve= 0 ,0
Exp/Cntr=0.3,0.1

Type RM Length L Ch R = 1 ,2946    ,305,290.4,260.2
BEGIN DESCRIPTION:
xs 4
END DESCRIPTION:
XS GIS Cut Line= 4
     2297747.612      516526.992     2298531.744      517282.243
2298886.67753726517364.0130509092298931.78131387 518853.84024689
#Sta/Elev= 30
       0 2612.03    49.3 2595.28    64.2  2586.8    78.1 2583.06   145.2  2580.6
     234 2583.35     303 2591.56   345.1 2592.21   389.5 2610.42   406.8  2610.4
   468.7 2611.66   495.1 2588.55   506.7 2579.18  511.66 2576.29  533.86 2576.19
   560.2  2579.3   568.2  2582.4   614.4 2580.62   650.6 2583.43   774.2 2581.26
  1146.6  2585.9  1167.1 2583.67  1310.8 2587.74  1470.1 2585.91  1510.1 2591.88
  1534.1 2591.05  1558.1 2585.67  2798.7 2589.44  2839.2 2592.25  2943.4 2619.13
#Mann= 11 ,-1,0
       0     .12       0    64.2      .1       0     234     .04       0
     303      .1       0   406.8    .016       0   495.1      .1       0
   506.7    .045       0   560.2      .1       0   774.2     .05       0
  1310.8    .016       0  1558.1     .05       0
#XS Ineff= 3 ,-1
       0     445 2613.51   851.7 1292.432586.256 1510.75 2427.042594.411
Permanent Ineff=
       F       F       F
#Block Obstruct= 2 ,-1
  1220.6 1276.69 2606.12    1425    1491 2607.07
Bank Sta=506.7,560.2
XS Rating Curve= 0 ,0
Exp/Cntr=0.5,0.3

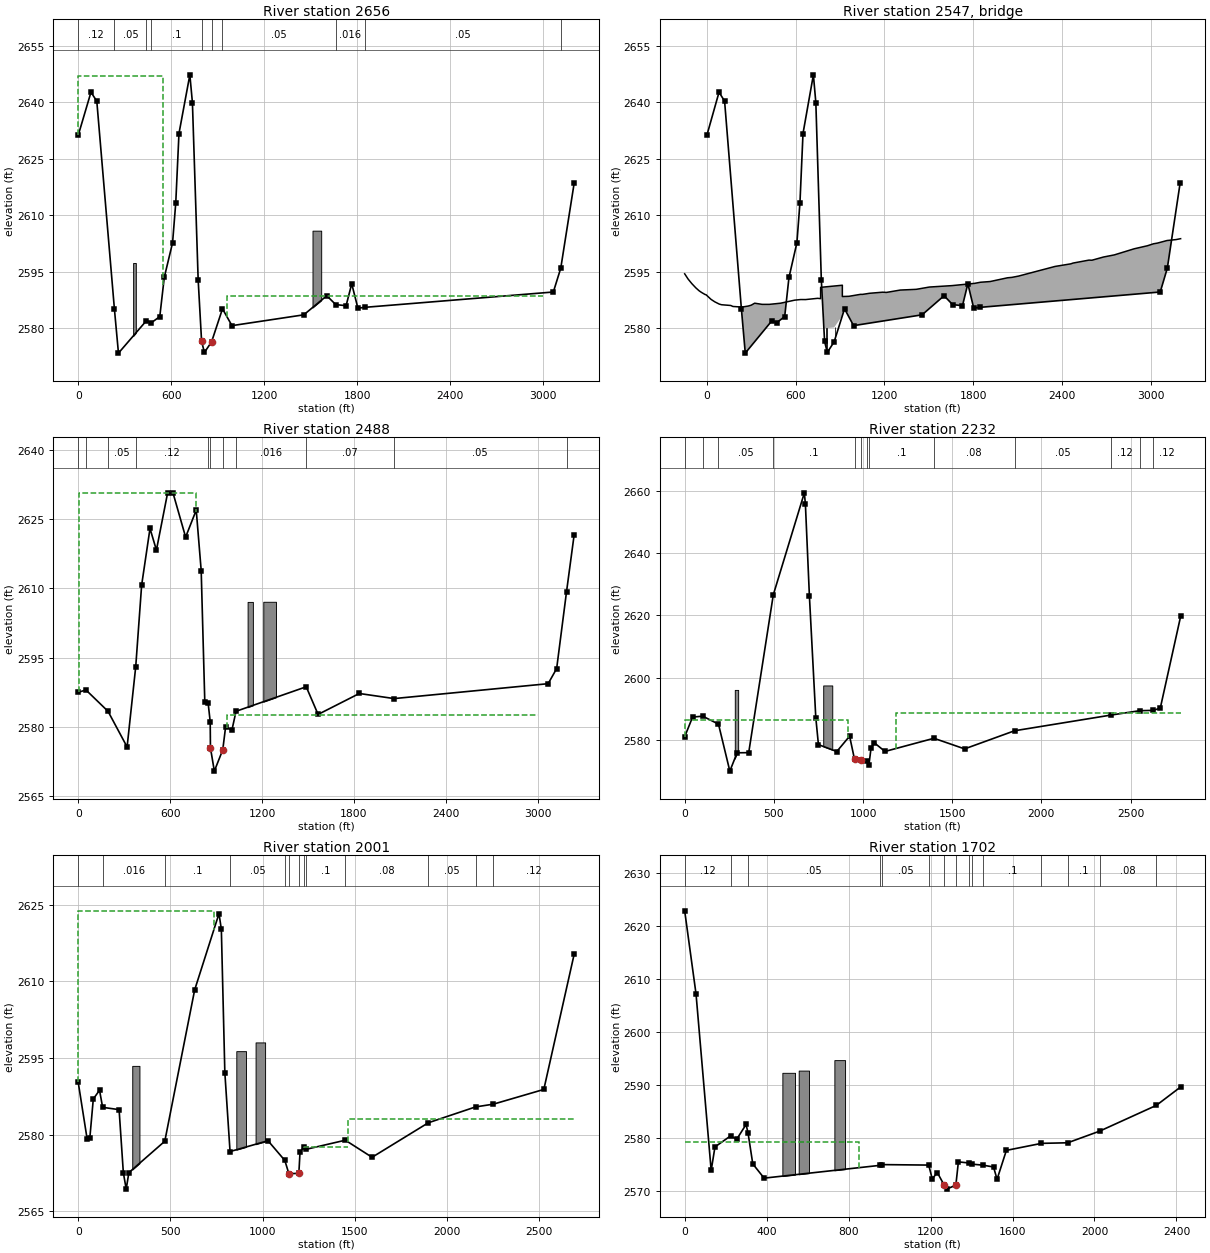
Type RM Length L Ch R = 1 ,2656    ,171.4,167.8,167.5
BEGIN DESCRIPTION:
xs 3 Merged DS Survey NOR012BU
END DESCRIPTION:
XS GIS Cut Line= 4
     2297255.731      516814.456     2297555.894      517036.189
2298857.99906454517370.0506241152298919.70528038518851.355707176
#Sta/Elev= 30
       0 2631.19    82.3 2642.65   119.9 2640.27   233.5  2585.1   259.7 2573.36
     440 2581.97   472.6 2581.45   526.3 2583.06   555.2 2593.45   608.8 2602.67
   629.5 2613.32   650.1 2631.68   720.3 2647.26   736.9 2639.88     774 2592.79
  796.04  2576.5814.3012 2573.54   860.7 2576.37   930.9 2585.13   992.1 2580.66
  1455.4 2583.53    1604  2588.6  1661.8 2586.24  1728.5 2585.96  1764.8 2591.78
  1804.6 2585.29  1849.3 2585.52  3065.7 2589.59  3113.7 2595.94    3200 2618.48
#Mann= 10 ,-1,0
       0     .12       0   233.5     .05       0     440    .016       0
   472.6      .1       0  796.04    .045       0   860.7      .1       0
   930.9     .05       0  1661.8    .016       0  1849.3     .05       0
  3113.7      .1       0
#XS Ineff= 3 ,-1
       0     550 2647.05     550     700  2586.7     960    3000  2588.4
Permanent Ineff=
       F       F       F
#Block Obstruct= 2 ,-1
  354.32   371.7  2597.3 1511.68 1567.84 2605.88
Bank Sta=796.04,860.7
XS Rating Curve= 0 ,0
Exp/Cntr=0.5,0.3

Type RM Length L Ch R = 3 ,2547    ,,,
BEGIN DESCRIPTION:
Potomac Highlands Trail (WV 28/92).
Merged Survey NOR008-012: 3' concrete railing height (same width as clearance from aerial imagery), 8' deck thickness. 2' long pier walls with rounded noses. Slightly haunched spans (pier losses expected to dominate).
From photographs: shallow flows with cobbled channel below.
END DESCRIPTION:
Bridge Culvert--1,0,-1,-1, 0
Deck Dist Width WeirC Skew NumUp NumDn MinLoCord MaxHiCord MaxSubmerge Is_Ogee
88.31786,45,2.6,0, 60, 60, , , 0.98, 0, 0,0,,
    -150 -126.94 -101.75  -74.05  -52.01  -35.47  -12.34   -5.45   28.63    54.1
   83.96    99.4  161.67  176.01  221.86  246.46  279.36  299.46  323.44  373.47
  422.44  498.82  594.28  634.59  667.27  748.88  769.27  769.28  916.18  916.19
  961.07  1038.6 1052.32  1099.8 1188.15 1214.06 1307.91 1415.66 1504.83 1658.59
 1809.32 1850.05 1915.23 2033.52 2061.88 2106.69 2354.31  2461.1 2476.56 2583.56
 2603.75 2681.76 2754.65 2889.72 2978.813020.3553045.8493111.4713172.8923203.508
 2594.42 2593.03 2591.82 2590.67  2589.9 2589.46 2588.93 2588.86 2587.62 2586.97
 2586.38 2586.21 2586.01 2585.75 2585.63 2585.65 2585.86 2586.09 2586.62 2586.31
 2586.31 2586.62 2587.43 2587.59 2587.58 2587.91 2587.83 2590.83 2591.39 2588.39
 2588.45 2588.97 2588.96 2589.25 2589.54 2589.48 2590.11  2590.3 2590.91 2591.29
 2591.88 2592.18 2592.37 2593.37 2593.47 2593.81 2596.38 2597.07 2597.28 2598.06
 2598.03 2598.88 2599.44 2601.07 2601.87  2602.4 2602.57 2603.26 2603.51 2603.75
                                                                                
                                                                                
                                                         2579.83 2580.39
                                                                                
                                                                                
                                                                                
     -75  -51.94  -26.75     .95   22.99   39.53   62.66   69.56  103.63   129.1
  158.96   174.4  236.67  251.01  296.86  321.46  354.36  374.46  398.44  448.47
  497.44  573.82  669.28  709.59  742.27  823.88  844.27  844.28  991.18  991.19
 1036.07  1113.6 1127.32  1174.8 1263.15 1289.06 1382.91 1490.66 1579.83 1733.59
 1884.32 1925.05 1990.23 2108.52 2136.88 2181.69 2429.31  2536.1 2551.56 2658.56
 2678.75 2756.76 2829.65 2964.72 3053.81 3095.36 3120.85 3186.47 3247.89 3278.51
 2594.42 2593.03 2591.82 2590.67  2589.9 2589.46 2588.93 2588.86 2587.62 2586.97
 2586.38 2586.21 2586.01 2585.75 2585.63 2585.65 2585.86 2586.09 2586.62 2586.31
 2586.31 2586.62 2587.43 2587.59 2587.58 2587.91 2587.83 2590.83 2591.39 2588.39
 2588.45 2588.97 2588.96 2589.25 2589.54 2589.48 2590.11  2590.3 2590.91 2591.29
 2591.88 2592.18 2592.37 2593.37 2593.47 2593.81 2596.38 2597.07 2597.28 2598.06
 2598.03 2598.88 2599.44 2601.07 2601.87  2602.4 2602.57 2603.26 2603.51 2603.75
                                                                                
                                                                                
                                                         2579.83 2580.39
                                                                                
                                                                                
                                                                                
Pier Skew, UpSta & Num, DnSta & Num=  ,809.3, 2 ,886.9, 2 , 0 , 0 , 0 ,,
       2       2
    2570    2585
       2       2
    2570    2585
Pier Skew, UpSta & Num, DnSta & Num=  ,866.37, 2 ,943.66, 2 , 0 , 0 , 0 ,,
       2       2
    2570    2585
       2       2
    2570    2585
BR Coef=-1 ,-1 , 0 ,, 0 ,,,0.8,-1,1.33,0,
WSPro=,,,, 1 ,,,, 0 ,,,, 0 ,,,,-1 ,-1 ,-1 , 0 , 0 , 0 , 0 , 0
BR U #Sta/Elev= 30
       0 2631.19    82.3 2642.65   119.9 2640.27   233.5  2585.1   259.7 2573.36
     440 2581.97   472.6 2581.45   526.3 2583.06   555.2 2593.45   608.8 2602.67
   629.5 2613.32   650.1 2631.68   720.3 2647.26   736.9 2639.88     774 2592.79
  796.04  2576.5 814.301 2573.54   860.7 2576.37   930.9 2585.13   992.1 2580.66
  1455.4 2583.53    1604  2588.6  1661.8 2586.24  1728.5 2585.96  1764.8 2591.78
  1804.6 2585.29  1849.3 2585.52  3065.7 2589.59  3113.7 2595.94    3200 2618.48
BR U #Mann= 10
       0     .12   233.5     .05     440    .016   472.6      .1  796.04     .04
   860.7      .1   930.9     .05  1661.8    .016  1849.3     .05  3113.7      .1
BR D #Sta/Elev= 30
       0 2587.48      50 2588.03   194.5  2583.4   319.2 2575.68   375.6 2593.08
   414.1 2610.69   468.7 2622.96   510.6 2618.27     583 2630.55   619.7 2630.56
   701.3 2621.09   770.6 2626.94   802.9 2613.86   826.6 2585.31   848.2 2585.21
   861.8 2581.14   863.32575.514  888.77 2570.45   943.82575.075   962.4 2580.04
  1003.2 2579.29  1030.5  2583.4  1488.7  2588.7  1566.2 2582.72  1835.4 2587.25
  2062.4 2586.15  3068.2 2589.37  3123.7 2592.64  3188.1 2609.24    3238 2621.59
BR D #Mann= 11
       0     .04      50    .016   194.5     .05   375.6     .12   848.2    .016
   863.3     .04   943.8      .1  1030.5    .016  1488.7     .07  2062.4     .05
  3188.1      .1
BC Design=,, 0 ,, 0 ,,,,,,
BC HTab HWMax=0
BC HTab TWMax=0
BC HTab MaxFlow=0
BC Use User HTab Curves=0
BC User HTab FreeFlow(D)= 0

Type RM Length L Ch R = 1 ,2488    ,249.1,256.1,268.6
BEGIN DESCRIPTION:
xs 2 Merged US Survey NOR008BD
END DESCRIPTION:
XS GIS Cut Line= 4
     2297120.534      516914.199     2297426.637      517193.144
2298827.81119851517474.1987619182298907.30924689518866.717707176
#Sta/Elev= 30
       0 2587.48      50 2588.03   194.5  2583.4   319.2 2575.68   375.6 2593.08
   414.1 2610.69   468.7 2622.96   510.6 2618.27     583 2630.55   619.7 2630.56
   701.3 2621.09   770.6 2626.94   802.9 2613.86   826.6 2585.31   848.2 2585.21
   861.8 2581.14   863.32575.514888.7701 2570.45   943.82575.075   962.4 2580.04
  1003.2 2579.29  1030.5  2583.4  1488.7  2588.7  1566.2 2582.72  1835.4 2587.25
  2062.4 2586.15  3068.2 2589.37  3123.7 2592.64  3188.1 2609.24    3238 2621.59
#Mann= 11 ,-1,0
       0     .04       0      50    .016       0   194.5     .05       0
   375.6     .12       0   848.2    .016       0   863.3    .045       0
   943.8      .1       0  1030.5    .016       0  1488.7     .07       0
  2062.4     .05       0  3188.1      .1       0
#XS Ineff= 3 ,-1
    2.82  766.892630.674  766.89  839.52  2581.4 971.667    3000  2582.5
Permanent Ineff=
       F       F       F
#Block Obstruct= 2 ,-1
 1105.93 1140.35 2607.07 1208.36 1291.14  2607.1
Bank Sta=863.3,943.8
XS Rating Curve= 0 ,0
Exp/Cntr=0.5,0.3

Type RM Length L Ch R = 1 ,2232    ,226.5,231.1,233.7
XS GIS Cut Line= 4
2297088.88096551516877.9568971282297571.31446298517433.873642565
2298187.93476108517673.4929293912298900.40277391518858.809668223
#Sta/Elev= 30
       0 2581.12    44.3 2587.43     101 2587.72   189.6 2585.17   253.2  2570.1
   293.8 2575.98     359 2576.02   496.8 2626.62     671 2659.33   676.9 2655.63
   699.3 2626.24   735.1 2587.26   749.9  2578.6   852.9 2576.39   924.7 2581.31
   952.32573.862   990.2 2573.67  1023.6 2573.31  1033.1 2572.16  1045.2 2577.64
  1063.8 2579.15  1123.2 2576.41  1397.6 2580.63  1569.5 2577.23  1849.4 2583.04
  2388.6 2588.06  2551.8 2589.48  2627.6 2589.58  2666.7 2590.32  2780.6  2619.7
#Mann= 13 ,-1,0
       0     .12       0     101    .016       0   189.6     .05       0
   496.8      .1       0   952.3    .045       0   990.2      .1       0
  1023.6    .016       0  1033.1      .1       0  1397.6     .08       0
  1849.4     .05       0  2388.6     .12       0  2551.8      .1       0
  2627.6     .12       0
#XS Ineff= 2 , 0
          917.75 2586.51 1182.44         2588.78
Permanent Ineff=
       F       F
#Block Obstruct= 2 ,-1
  280.93  299.82 2596.14  776.74  827.45 2597.57
Bank Sta=952.3,990.2
XS Rating Curve= 0 ,0
Exp/Cntr(USF)=0,0
Exp/Cntr=0.3,0.1

Type RM Length L Ch R = 1 ,2001    ,206,298.5,391
XS GIS Cut Line= 4
     2297036.363      516837.291     2297609.403      517688.572
     2297990.803      517850.605     2298692.611       518883.66
#Sta/Elev= 30
       0 2590.26    48.8 2579.07    63.2 2579.45    81.8 2586.99   115.6 2588.71
   132.4 2585.36   221.7 2584.91   244.7  2572.6   260.2 2569.36   274.7 2572.59
   469.5 2578.73   631.5 2608.33   763.5 2623.26   776.2  2620.2   795.2 2592.14
   823.4 2576.71  1029.2 2578.83  1120.5 2574.97  1142.2  2572.4  1196.5 2572.43
    1203 2576.65    1224 2577.57  1236.2 2577.15  1448.5 2578.93  1593.6 2575.59
  1898.6 2582.34  2154.7 2585.44  2251.3 2585.98    2525 2588.86  2689.5  2615.3
#Mann= 13 ,-1,0
       0     .12       0   132.4    .016       0   469.5      .1       0
   823.4     .05       0  1120.5      .1       0  1142.2    .045       0
  1196.5     .08       0    1224    .016       0  1236.2      .1       0
  1448.5     .08       0  1898.6     .05       0  2154.7     .08       0
  2251.3     .12       0
#XS Ineff= 3 ,-1
       0  735.15  2623.8    1227    1463 2577.55    1463  2689.5 2583.14
Permanent Ineff=
       F       F       F
#Block Obstruct= 3 ,-1
  292.99  332.06 2593.47  857.37  910.06 2596.35  961.84  1013.5 2598.06
Bank Sta=1142.2,1196.5
XS Rating Curve= 0 ,0
Exp/Cntr=0.3,0.1

Type RM Length L Ch R = 1 ,1702    ,302.8,262.4,229.1
XS GIS Cut Line= 4
2296922.65005575516801.1491919332297501.88083577517806.717348119
2297557.74573334518038.997711682 2298266.3478551518774.062153339
#Sta/Elev= 30
       0 2622.93    55.4  2607.2   129.3  2573.8   147.8 2578.26   223.7 2580.33
   253.9 2579.71   299.6  2582.5   309.3 2580.88   332.4 2575.04   387.7 2572.35
     951 2574.76   964.8 2574.91  1190.9 2574.82  1208.3 2572.21  1232.9 2573.41
  1267.2 2570.98  1278.2 2570.27  1323.4 2571.02  1335.8 2575.43  1386.6 2575.22
  1402.6    2575  1456.4  2574.8  1507.3 2574.46  1524.6 2572.13    1570  2577.6
  1741.3 2578.93  1869.4 2579.04    2025 2581.24    2302 2586.12  2420.4  2589.6
#Mann= 15 ,-1,0
       0     .12       0   223.7    .016       0   309.3     .05       0
     951     .04       0   964.8     .05       0  1190.9     .08       0
  1267.2    .045       0  1323.4     .05       0  1386.6    .016       0
  1402.6     .05       0  1456.4      .1       0  1741.3     .05       0
  1869.4      .1       0    2025     .08       0    2302      .1       0
#XS Ineff= 2 , 0
          849.84  2579.2
Permanent Ineff=
       F       F
#Block Obstruct= 3 ,-1
  476.77   538.5 2592.28  556.41  606.79  2592.7  730.57  782.78 2594.68
Bank Sta=1267.2,1323.4
XS Rating Curve= 0 ,0
Exp/Cntr(USF)=0,0
Exp/Cntr=0.3,0.1