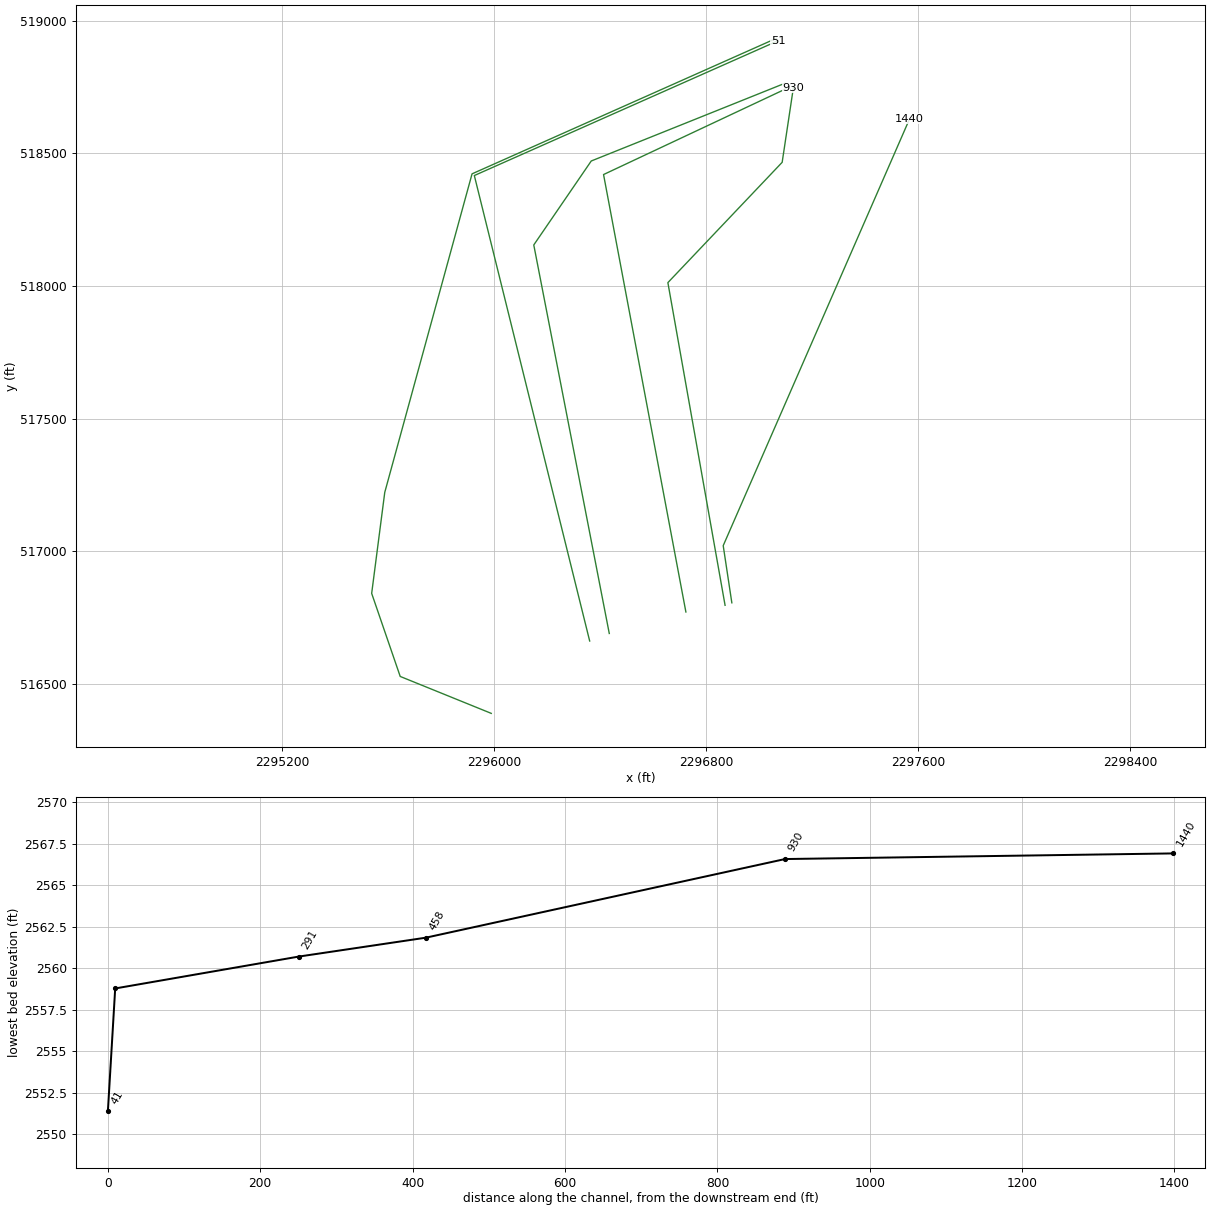
HEC-RAS study NRTHFRK.prj: NRTHFRK

--- NRTHFRK.g01 (geometry) --- (continued)

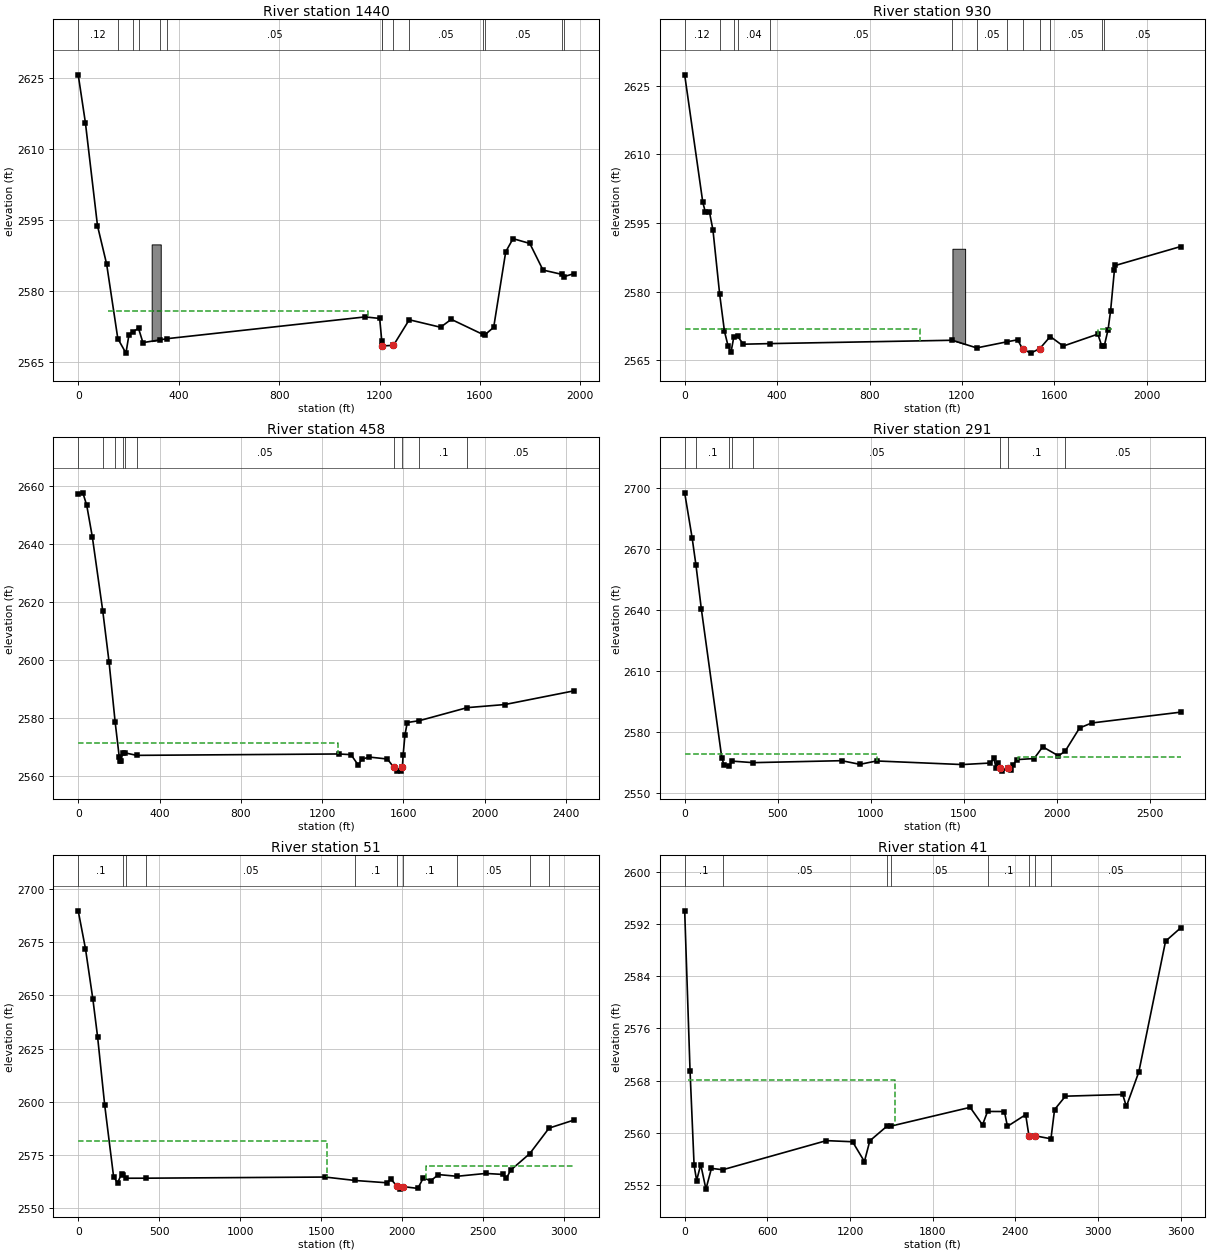
Type RM Length L Ch R = 1 ,1440    ,538.6,509.8,448.1
XS GIS Cut Line= 3
     2296895.996      516805.223     2296863.446      517020.801
     2297567.025      518630.856
#Sta/Elev= 30
       0 2625.64    28.7 2615.51    76.8 2593.79   113.2  2585.7   157.7 2569.99
   190.1 2566.92   202.2 2570.83     218 2571.43   240.1 2572.16   257.7 2569.14
   327.6 2569.73   353.8 2569.97  1142.3 2574.56  1200.6 2574.24  1208.8 2569.58
  1211.6 2568.43  1255.6 2568.57  1318.3 2573.96  1443.1 2572.38  1485.6 2574.05
  1610.2  2570.9  1619.7  2570.8  1654.6 2572.36  1702.6 2588.31  1731.7 2591.07
  1798.5 2590.06    1851 2584.45  1925.2 2583.55  1935.2 2583.07  1975.1  2583.7
#Mann= 14 ,-1,0
       0     .12       0   157.7     .04       0     218    .016       0
   240.1     .04       0   327.6     .03       0   353.8     .05       0
  1208.8      .1       0  1211.6    .045       0  1255.6      .1       0
  1318.3     .05       0  1610.2    .045       0  1619.7     .05       0
  1925.2    .016       0  1935.2     .05       0
#XS Ineff= 1 ,-1
  120.19 1153.34 2575.86
Permanent Ineff=
       F
#Block Obstruct= 1 ,-1
  292.55  328.65 2589.86
Bank Sta=1211.6,1255.6
XS Rating Curve= 0 ,0
Exp/Cntr=0.3,0.1

Type RM Length L Ch R = 1 ,930     ,186.7,471.6,529.4
Node Name=A
XS GIS Cut Line= 4
     2296870.483      516795.837     2296654.655      518012.638
     2297085.912       518466.33     2297128.289      518747.988
#Sta/Elev= 30
       0 2627.35    78.5 2599.48    89.4 2597.41     107 2597.44   122.3  2593.5
   151.5 2579.41   172.2 2571.34   188.2 2568.08   200.4 2566.74   212.6 2570.09
   228.9 2570.34   253.2 2568.53   369.2 2568.66  1158.4 2569.39  1264.1 2567.72
  1396.6 2569.07    1441 2569.49  1462.8 2567.49  1497.6 2566.58  1537.2 2567.57
  1582.4 2570.21  1638.6 2568.12  1788.4 2570.73  1805.9 2568.05    1816 2568.12
  1832.6 2571.71  1843.6 2575.86  1860.2 2584.79  1864.6 2585.73  2146.6 2589.85
#Mann= 13 ,-1,0
       0     .12       0   151.5     .04       0   212.6    .016       0
   228.9     .04       0   369.2     .05       0  1158.4     .04       0
  1264.1     .05       0  1396.6     .08       0  1462.8    .045       0
  1537.2      .1       0  1582.4     .05       0  1805.9    .045       0
    1816     .05       0
#XS Ineff= 2 ,-1
       0 1016.672571.859 1789.79 1849.032571.913
Permanent Ineff=
       F       F
#Block Obstruct= 1 ,-1
 1158.98 1213.92 2589.37
Bank Sta=1462.8,1537.2
XS Rating Curve= 0 ,0
Exp/Cntr=0.3,0.1

Type RM Length L Ch R = 1 ,458     ,382.6,167,143
XS GIS Cut Line= 3
2296722.60783165516770.613233367 2296411.9079889518420.205181989
2297100.57258881518743.717389389
#Sta/Elev= 30
       0 2657.35      23 2657.71      42 2653.36    69.4 2642.55   120.5 2617.14
   151.6 2599.52   181.7 2578.73   202.1 2566.57   206.1  2565.2   210.2 2565.17
   218.3 2568.02   229.2 2568.15   287.5 2567.27  1281.9 2567.75  1341.8 2567.52
  1377.8 2563.88  1394.3 2565.92  1431.3 2566.69  1520.8 2566.01  1552.5 2563.13
  1569.6 2561.84  1590.1 2561.94  1594.72563.273  1598.2 2567.35  1607.3 2574.36
  1618.5 2578.58  1678.6 2579.23  1913.1 2583.71  2098.7 2584.78  2439.5 2589.51
#Mann= 10 ,-1,0
       0     .12       0   120.5      .1       0   181.7     .04       0
   218.3    .016       0   229.2     .04       0   287.5     .05       0
  1552.5    .045       0  1594.7      .1       0  1678.6      .1       0
  1913.1     .05       0
#XS Ineff= 2 , 0
         1277.93 2571.58
Permanent Ineff=
       F       F
Bank Sta=1552.5,1594.7
XS Rating Curve= 0 ,0
Exp/Cntr(USF)=0,0
Exp/Cntr=0.3,0.1

Type RM Length L Ch R = 1 ,291     ,367.1,240.7,211.3
XS GIS Cut Line= 4
     2296433.502      516689.538     2296148.613      518154.728
     2296365.488      518471.316     2297095.883      518764.237
#Sta/Elev= 30
       0 2697.62    40.4 2675.24    60.8 2661.89    89.3  2640.6   199.3 2567.26
   211.5 2563.67   240.1 2563.46   255.8 2565.62   367.1 2564.87   843.1 2565.84
   940.9 2564.04  1030.6  2565.7  1491.1 2563.93  1641.1 2564.69  1660.5 2566.95
  1672.5 2562.16    1684 2564.52  1691.5 2562.22  1703.9  2560.7  1734.7 2562.13
  1752.6 2561.11  1762.3 2563.81  1786.5 2566.38  1876.4 2566.89  1922.9 2572.65
  2007.4 2568.22  2043.4 2570.54  2120.6 2581.92  2185.3 2584.38  2663.3 2589.71
#Mann= 8 ,-1,0
       0     .12       0    60.8      .1       0   240.1    .016       0
   255.8     .04       0   367.1     .05       0  1691.5    .045       0
  1734.7      .1       0  2043.4     .05       0
#XS Ineff= 2 , 0
         1031.81 2568.89  1790.3         2567.54
Permanent Ineff=
       F       F
Bank Sta=1691.5,1734.7
XS Rating Curve= 0 ,0
Exp/Cntr=0.3,0.1

Type RM Length L Ch R = 1 ,51      ,9.4,9.6,9.7
XS GIS Cut Line= 3
     2296359.579      516661.101      2295924.26      518416.474
     2297070.955      518925.008
#Sta/Elev= 30
       0 2689.84    44.8 2671.99    90.7 2648.15   119.6 2630.55   163.7 2598.26
   218.5 2564.66   243.2 2561.71     268 2566.05   276.2 2565.55   296.8 2563.91
   416.3 2563.93  1525.2 2564.47  1710.1 2562.85  1904.7 2561.78    1931 2563.46
  1969.7 2560.12  1987.8 2558.78    2003    2560  2097.2 2559.12  2132.3 2564.16
  2175.8 2562.63  2224.7 2565.63  2339.5 2564.83  2517.3 2566.17  2622.3  2565.7
  2644.2 2563.81  2670.5 2567.68  2788.6 2575.49  2907.8 2587.51  3062.9 2591.34
#Mann= 10 ,-1,0
       0      .1       0   276.2    .016       0   296.8     .04       0
   416.3     .05       0  1710.1      .1       0  1969.7    .045       0
    2003      .1       0  2339.5     .05       0  2788.6     .08       0
  2907.8     .05       0
#XS Ineff= 2 , 0
         1534.88 2581.24 2149.49          2569.9
Permanent Ineff=
       F       F
Bank Sta=1969.7,2003
XS Rating Curve= 0 ,0
Exp/Cntr=0.3,0.1

Type RM Length L Ch R = 1 ,41      ,,,
XS GIS Cut Line= 6
2295988.18415163516388.2427445312295644.60297738516527.487965432
2295536.91113868516840.7213949642295586.29321253517221.719394224
2295915.70079605518422.8602812512297064.02697636518933.875146601
#Sta/Elev= 30
       0 2594.02    38.9 2569.53    68.3 2555.04    86.7  2552.7   116.5 2555.14
   154.3 2551.38   194.2 2554.56   276.2 2554.35  1028.6 2558.81  1218.5 2558.64
  1304.6 2555.61  1343.8 2558.78  1467.3 2561.01    1500 2561.05  2071.9 2563.91
  2161.8 2561.22  2198.4 2563.28  2320.7 2563.27  2342.8    2561  2475.2 2562.79
  2499.42559.447  2541.82559.555  2658.5 2559.09  2684.8 2563.57  2763.6 2565.62
  3179.5 2565.88  3205.8 2564.04  3296.3 2569.33  3490.4 2589.37  3599.7  2591.4
#Mann= 8 ,-1,0
       0      .1       0   276.2     .05       0  1467.3    .016       0
    1500     .05       0  2198.4      .1       0  2499.4    .045       0
  2541.8      .1       0  2658.5     .05       0
#XS Ineff= 1 ,-1
      25  1528.42568.093
Permanent Ineff=
       F
Bank Sta=2499.4,2541.8
XS Rating Curve= 0 ,0
Exp/Cntr=0.3,0.1
LCMann Table=0

Chan Stop Cuts=-1
Use User Specified Reach Order=0
Composite Channel Slope=5